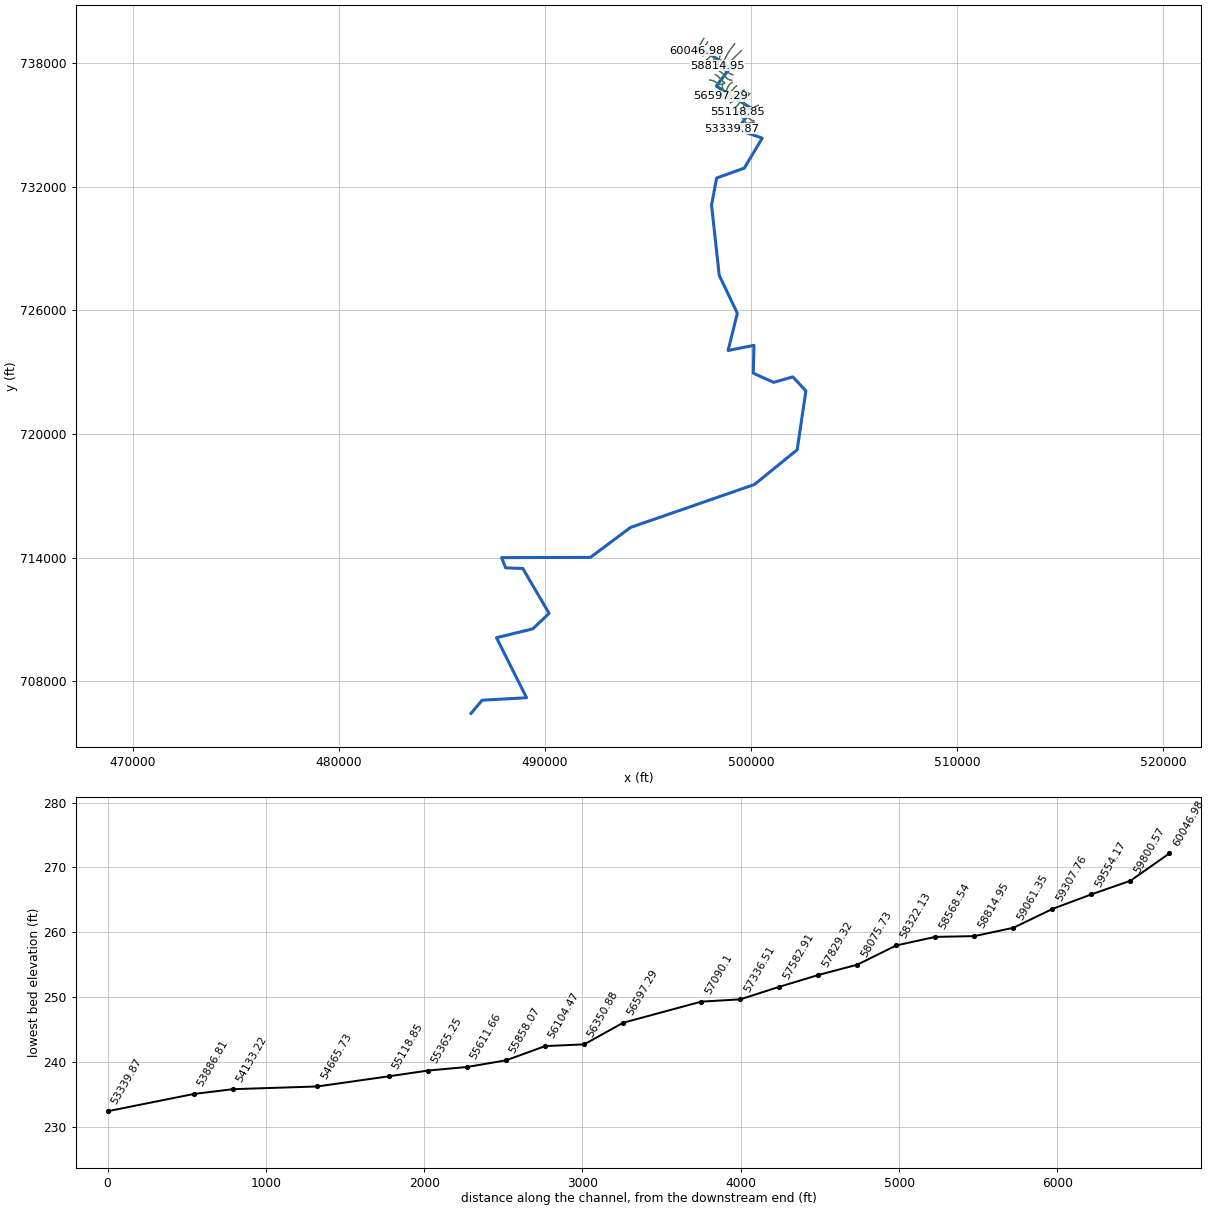
--- 978_ras.prj (project) ---

Proj Title=978
Current Plan=p01
Default Exp/Contr=0.3,0.1
English Units
Geom File=g01
Flow File=f01
Plan File=p01
Y Axis Title=Elevation
X Axis Title(PF)=Main Channel Distance
X Axis Title(XS)=Station
BEGIN DESCRIPTION:
RFD model 978 exported to HEC-RAS
END DESCRIPTION:

--- 978_ras.p01 (plan) ---

Plan Title=Plan 01
Program Version=4.10
Short Identifier=Plan 01
Geom File=g01
Flow File=f01
Subcritical Flow
Calc Critical at every XS
Secant Critical Depth

--- 978_ras.f01 (steady flow) ---

Flow Title=Flow 01
Program Version=5.01
Number of Profiles= 6
Profile Names=10yr,25yr,50yr,100yr,100plus,500yr
River Rch & RM=978,140,60046.98
 2568.38 4432.49 6301.93 8138.8811882.7615078.33
River Rch & RM=978,140,59800.57
 2572.46 4440.51 6314.24 8155.8311907.5215109.66
River Rch & RM=978,140,59554.17
 2574.27 4444.06  6319.7 8163.35 11918.515123.57
River Rch & RM=978,140,59307.76
 2576.79 4449.07 6327.44 8174.0711934.1415143.56
River Rch & RM=978,140,59061.35
 2577.54 4450.58 6329.77 8177.3111938.8815149.65
River Rch & RM=978,140,58814.95
 2579.95 4455.36 6337.16 8187.5411953.8115168.76
River Rch & RM=978,140,58568.54
 2581.78 4459.02 6342.84 8195.4211965.3115183.52
River Rch & RM=978,140,58322.13
 3731.47 6553.46 9427.6912300.6217958.9121984.26
River Rch & RM=978,140,58075.73
  3735.7 6561.81 9440.5912318.4917984.9922015.78
River Rch & RM=978,140,57829.32
 3738.62 6567.59 9449.5112330.8318003.0122037.53
River Rch & RM=978,140,57582.91
 3740.14 6570.57 9454.1212337.2118012.3322048.78
River Rch & RM=978,140,57336.51
 3741.24 6572.77  9457.512341.8918019.1622057.03
River Rch & RM=978,140, 57090.1
 3831.38 6749.35 9728.9612716.5218566.1222711.52
River Rch & RM=978,140,56597.29
  3832.9 6752.41 9733.7312723.1718575.8322723.38
River Rch & RM=978,140,56350.88
  3835.3 6757.22 9741.2112733.5818591.03 22741.9
River Rch & RM=978,140,56104.47
 3837.03 6760.67 9746.5812741.0718601.9722755.23
River Rch & RM=978,140,55858.07
 3839.49 6765.62  9754.312751.85 18617.722774.48
River Rch & RM=978,140,55611.66
 3840.63 6767.91 9757.8712756.8318624.9722783.37
River Rch & RM=978,140,55365.25
 3842.99 6772.65 9765.2712767.1718640.0722801.87
River Rch & RM=978,140,55118.85
 3860.93 6808.35 9820.6212844.0918752.3722937.88
River Rch & RM=978,140,54665.73
 3871.16 6828.96  9852.812889.0618818.03 23018.3
River Rch & RM=978,140,54133.22
 3876.35 6839.59 9869.5412912.6318852.4323061.04
River Rch & RM=978,140,53886.81
  3877.4 6841.77 9872.9812917.4818859.5223069.88
River Rch & RM=978,140,53339.87
 3931.07 6948.8310039.2713148.9319197.4423479.51
River Rch & RM=978,140,52654.78
 3933.62 6954.0810047.5513160.6119214.4923500.72
River Rch & RM=978,140,52161.96
 3943.78 6975.1410080.9213207.81 19283.423586.96
River Rch & RM=978,140,51669.15
 3944.66 6976.9410083.7813211.8319289.2823594.26
River Rch & RM=978,140,51176.34
 3952.12 6992.2210107.8413245.7119338.7423655.56
River Rch & RM=978,140,50929.93
 3953.54  6995.210112.5913252.4519348.5823667.96
River Rch & RM=978,140,50683.52
  3954.2 6996.58 10114.813255.6119353.1823673.79
River Rch & RM=978,140,50437.12
  3954.7 6997.6310116.4713257.9719356.6423678.17
River Rch & RM=978,140,50190.71
 3955.44 6999.1910118.9613261.5219361.8223684.73
River Rch & RM=978,140, 49944.3
 3955.69 6999.7110119.7913262.7119363.5523686.92
River Rch & RM=978,140, 49697.9
 3956.51 7001.4510122.5713266.6519369.3123694.21
River Rch & RM=978,140,49451.49
 3957.57 7003.6810126.1413271.7519376.7623703.68
River Rch & RM=978,140,49205.08
 4037.52 7168.5810386.9113640.0219914.4324372.72
River Rch & RM=978,140,48958.68
 4037.93 7169.4310388.2813641.9719917.2824376.32
River Rch & RM=978,140,48362.02
 4047.33 7189.0710419.5413686.37 19982.124457.73
River Rch & RM=978,140,48285.62
 4047.65 7189.7510420.6313687.9219984.3724460.61
River Rch & RM=978,140,48080.51
 4049.16 7192.9710425.79 13695.319995.1324474.29
River Rch & RM=978,140,47848.45
  4050.2 7195.1710429.3213700.34 20002.524483.64
River Rch & RM=978,140,47616.38
 4072.57 7242.0610504.1213806.7120157.7924679.08
River Rch & RM=978,140,47384.32
 4073.69 7244.4310507.9213812.1320165.7124689.12
River Rch & RM=978,140,47152.25
 4075.98  7249.310515.7413823.3220182.0524709.92
River Rch & RM=978,140,46920.18
 4076.91 7251.2910518.9613827.9320188.7824718.52
River Rch & RM=978,140,46688.12
 4082.23 7262.7110537.3813854.3820227.3924767.97
River Rch & RM=978,140,46456.05
 4085.95 7270.6710550.2213872.7920254.2724802.35
River Rch & RM=978,140,46241.78
 4086.26 7271.3310551.2913874.3220256.5124805.21
River Rch & RM=978,140,46097.63
 4087.26 7273.4810554.76 13879.320263.7824814.52
River Rch & RM=978,140,45749.86
 4924.41 8908.0313067.9817351.2625332.8430710.68
River Rch & RM=978,140,45445.74
 4926.28 8911.9913074.3317360.3625346.1330727.14
River Rch & RM=978,140,45207.37
 4927.73 8915.0913079.3517367.5825356.67 30740.3
River Rch & RM=978,140,44969.01
 4935.34 8931.4913105.9517405.96 25412.730810.69
River Rch & RM=978,140,44730.64
 4945.45 8953.0813140.8317456.1225485.9330902.03
River Rch & RM=978,140,44492.27
 4947.18  8956.813146.8317464.7625498.5530917.79
River Rch & RM=978,140, 44253.9
 4948.92 8960.5113152.8417473.3925511.1630933.55
River Rch & RM=978,140,44015.53
 4951.63 8966.35 13162.317487.0325531.0630958.49
River Rch & RM=978,140,43777.16
  4951.9 8966.9413163.2617488.4425533.1230961.12
River Rch & RM=978,140,43538.79
 4963.94  8993.2 13206.117550.5225623.7731075.88
River Rch & RM=978,140,43300.42
 4977.17 9022.4113254.0717620.3725725.7531206.18
River Rch & RM=978,140,43062.05
  4995.5 9063.5613322.1817720.1625871.4331394.37
River Rch & RM=978,140,42834.03
 4995.77 9064.1513323.1417721.5625873.4831396.98
River Rch & RM=978,140,42642.01
 4998.01 9069.11 13331.317733.4525890.8431419.17
River Rch & RM=978,140,42286.44
 4998.53 9070.2613333.1917736.2225894.8931424.39
River Rch & RM=978,140,42037.34
 5008.26 9092.4413370.1617790.6725974.3831528.06
River Rch & RM=978,140,41788.23
 5018.63 9115.9813409.3317848.2826058.4931637.46
River Rch & RM=978,140,41539.13
 5021.63 9122.9713421.1117865.7926084.0531671.29
River Rch & RM=978,140,41290.02
 5022.26 9124.4513423.6117869.4926089.4531678.44
River Rch & RM=978,140,41040.92
 5024.27 9129.1613431.5417881.2726106.65 31701.2
River Rch & RM=978,140,40791.81
 5024.86 9130.5813433.9617884.9126111.9631708.35
River Rch & RM=978,140,40542.71
 5027.93 9137.7213445.9817902.7526138.02 31742.8
River Rch & RM=978,140, 40293.6
 5038.19 9162.4513488.2517966.1426230.5631867.48
River Rch & RM=978,140,39795.39
 5038.86 9164.0913491.0717970.3926236.7731875.91
River Rch & RM=978,140,39297.18
 5062.06  9219.813586.1618112.9126444.8632155.71
River Rch & RM=978,140,39048.07
 5066.55 9231.4413606.65 18144.326490.68 32219.7
River Rch & RM=978,140,38798.97
 5067.16    923313609.3818148.4626496.75 32228.1
River Rch & RM=978,140,37802.55
  5074.4 9250.9813640.5218195.6226565.6132322.36
River Rch & RM=978,140,37055.23
 5078.82 9262.2313660.1918225.6126609.3932382.99
River Rch & RM=978,140,36806.13
 5079.18 9263.1613661.8418228.1326613.0832388.15
River Rch & RM=978,140,36557.02
 5079.31 9263.5113662.4518229.0826614.4632390.08
River Rch & RM=978,140,35558.61
 5089.99 9291.5613712.1118305.4226725.92 32546.6
River Rch & RM=978,140,34560.21
 5130.03 9387.4613875.7618550.82 27084.233027.84
River Rch & RM=978,140,33790.69
 5131.58 9391.3313882.4918561.0427099.1233048.32
River Rch & RM=978,140,33434.46
 5132.35  9393.2 13885.718565.8827106.1933057.91
River Rch & RM=978,140,33256.99
 5773.9310757.1316089.5521741.23 31742.238759.74
River Rch & RM=978,140,32902.06
 5795.98 10806.716172.0421862.9231919.8638986.59
River Rch & RM=978,140, 32797.9
 5796.1310807.0616172.6621863.8531921.2138988.39
River Rch & RM=978,140,32674.51
 5796.3910807.67 16173.7 21865.431923.4938991.39
River Rch & RM=978,140,32162.66
 5798.4310812.4616181.8321877.5831941.2739014.76
River Rch & RM=978,140,31692.29
 5799.9510815.9716187.7521886.4131954.1639031.54
River Rch & RM=978,140,30986.72
 5804.3510826.34 16205.421912.8831992.8139082.46
River Rch & RM=978,140,30516.35
 5819.0810859.4416260.4721994.1432111.4439233.86
River Rch & RM=978,140, 29575.6
 5827.4710878.7216292.9322042.4332181.9539325.31
River Rch & RM=978,140,29105.22
 5831.9410889.0816310.41 22068.532220.0239374.89
River Rch & RM=978,140,28634.85
 5835.6310897.7516325.1522090.5932252.2639417.27
River Rch & RM=978,140,28305.05
 5984.5311219.0316849.2322852.12 33364.140789.14
River Rch & RM=978,140,28159.19
  5985.811222.2216854.8322860.7133376.6340806.21
River Rch & RM=978,140,27919.07
 5985.9411222.5716855.43 22861.633377.9440807.98
River Rch & RM=978,140,27478.02
 5989.4911231.0416869.9522883.5133409.9240850.37
River Rch & RM=978,140,27036.96
 5990.6111233.7816874.6822890.7133420.4440864.49
River Rch & RM=978,140,26816.44
 5991.8311236.7416879.8222898.5133431.8340879.79
River Rch & RM=978,140,26595.91
 5992.2911237.8816881.7922901.5133436.2140885.68
River Rch & RM=978,140,25018.84
 6095.1211484.2317304.8223540.8834369.6942125.09
River Rch & RM=978,140,24573.96
 6095.4111484.9717306.13 23542.934372.6442129.16
River Rch & RM=978,140,23966.81
 6096.8411488.6517312.6623552.9934387.3742149.51
River Rch & RM=978,140,23447.43
  6123.9 11554.817427.3523727.6134642.3142491.97
River Rch & RM=978,140,21987.97
 6133.0211578.6217469.8123793.5334738.5542625.76
River Rch & RM=978,140,21746.26
 6133.8811580.8817473.8423799.7934747.69 42638.5
River Rch & RM=978,140,21504.55
 6134.3911582.2117476.2223803.4834753.0942646.02
River Rch & RM=978,140,21262.84
 6140.7911599.1917506.69   2385134822.4642743.19
River Rch & RM=978,140,21021.13
 6142.55 11603.917515.1623864.2434841.7942770.37
River Rch & RM=978,140,20779.42
 6143.75 11607.117520.9223873.2534854.9442788.86
River Rch & RM=978,140,20537.71
 6144.38 11608.817523.9823878.0334861.9342798.69
River Rch & RM=978,140,   20296
 6144.83   1161017526.1423881.4134866.8742805.62
River Rch & RM=978,140,20054.29
 6145.47 11611.7 17529.2 23886.234873.8542815.44
River Rch & RM=978,140,19812.58
 6154.0611634.9617571.2923952.2134970.2242951.72
River Rch & RM=978,140,19570.87
 6154.3811635.8517572.8923954.7234973.8942956.92
River Rch & RM=978,140,19329.16
  6156.911642.7517585.4423974.4635002.7142997.88
River Rch & RM=978,140,19087.45
 6157.4411644.2217588.0923978.6435008.8143006.53
River Rch & RM=978,140,18845.74
 6157.9311645.5817590.5723982.5335014.4943014.61
River Rch & RM=978,140,18604.03
  6158.411646.8517592.8723986.1435019.77 43022.1
River Rch & RM=978,140,18362.32
  6159.511649.8617598.3523994.7735032.3643039.98
River Rch & RM=978,140,18120.61
 6163.28 11660.117616.86 24023.835074.7543099.93
River Rch & RM=978,140, 17878.9
 6163.6311661.0617618.6224026.58 35078.8 43105.7
River Rch & RM=978,140,17682.36
 6170.2111678.8717650.8324077.0935152.5543209.95
River Rch & RM=978,140,17405.48
 6170.7611680.3917653.62 24081.535158.9943219.16
River Rch & RM=978,140,16814.73
  6384.312224.8518616.8525571.03 37333.746210.58
River Rch & RM=978,140,12319.54
14954.1530390.59 48151.868495.35100003.2116366.1
River Rch & RM=978,140,11166.39
14997.5430495.1848334.6168777.41  100415116860.8
River Rch & RM=978,140,11088.01
 14997.830495.8148335.7368779.16100417.6116863.9
River Rch & RM=978,140,10568.11
15003.69 30510.248361.0768818.48  100475116933.6
River Rch & RM=978,140,9835.345
15004.3230511.7448363.7768822.66100481.1116941.1
River Rch & RM=978,140,8858.331
15028.8430571.2948468.2868984.41100717.2117226.3
River Rch & RM=978,140,3729.003
15204.8530974.8849155.8670024.11102235.2118972.6
River Rch & RM=978,140,3517.535
15215.4631000.6349201.02   70094102337.2119095.6
River Rch & RM=978,140,437.4813
15708.0932082.3751000.3872761.81106232.2123369.1
River Rch & RM=978,140,       0
15708.3632083.0351001.5272763.57106234.8123372.2
Boundary for River Rch & Prof#=978,140,1
Up Type= 0
Dn Type= 2
Boundary for River Rch & Prof#=978,140,2
Up Type= 0
Dn Type= 2
Boundary for River Rch & Prof#=978,140,2
Up Type= 0
Dn Type= 2
Boundary for River Rch & Prof#=978,140,2
Up Type= 0
Dn Type= 2
Boundary for River Rch & Prof#=978,140,2
Up Type= 0
Dn Type= 2
Boundary for River Rch & Prof#=978,140,2
Up Type= 0
Dn Type= 2

--- 978_ras.g01 (geometry) ---

Geom Title=978
Program Version=4.10

River Reach=978,140
Reach XY= 30
497453.977383674738741.545261963499016.251113798737799.410278768
498317.522106886736877.753300321500071.379432442735760.045333069
 499327.10916912734775.598631278500544.980967134734352.308911649
499674.421095909732895.079810227 498328.41511228732412.644246573
498085.447867695731097.844987991498456.766064581727692.927041833
499336.196987152725849.534393667498886.405429776724044.669791969
500142.466499773724292.735108989500108.419978853722945.630766769
501096.033142031722498.630251279502029.862740696722765.012015328
502662.207868993722082.764807719502239.267326741719227.406349206
500163.799899425717541.392237355494155.918246984715459.689969291
 492204.45443579714005.953948108487895.811471247713994.014431127
488092.069553764713497.760758657 488925.84415585713468.826089966
490198.225462312 711291.29163412489411.135184556710536.238049814
487648.681065198710108.512420404489108.608802377707194.477271028
486950.971012265707075.569296103486413.281115346706436.196586881

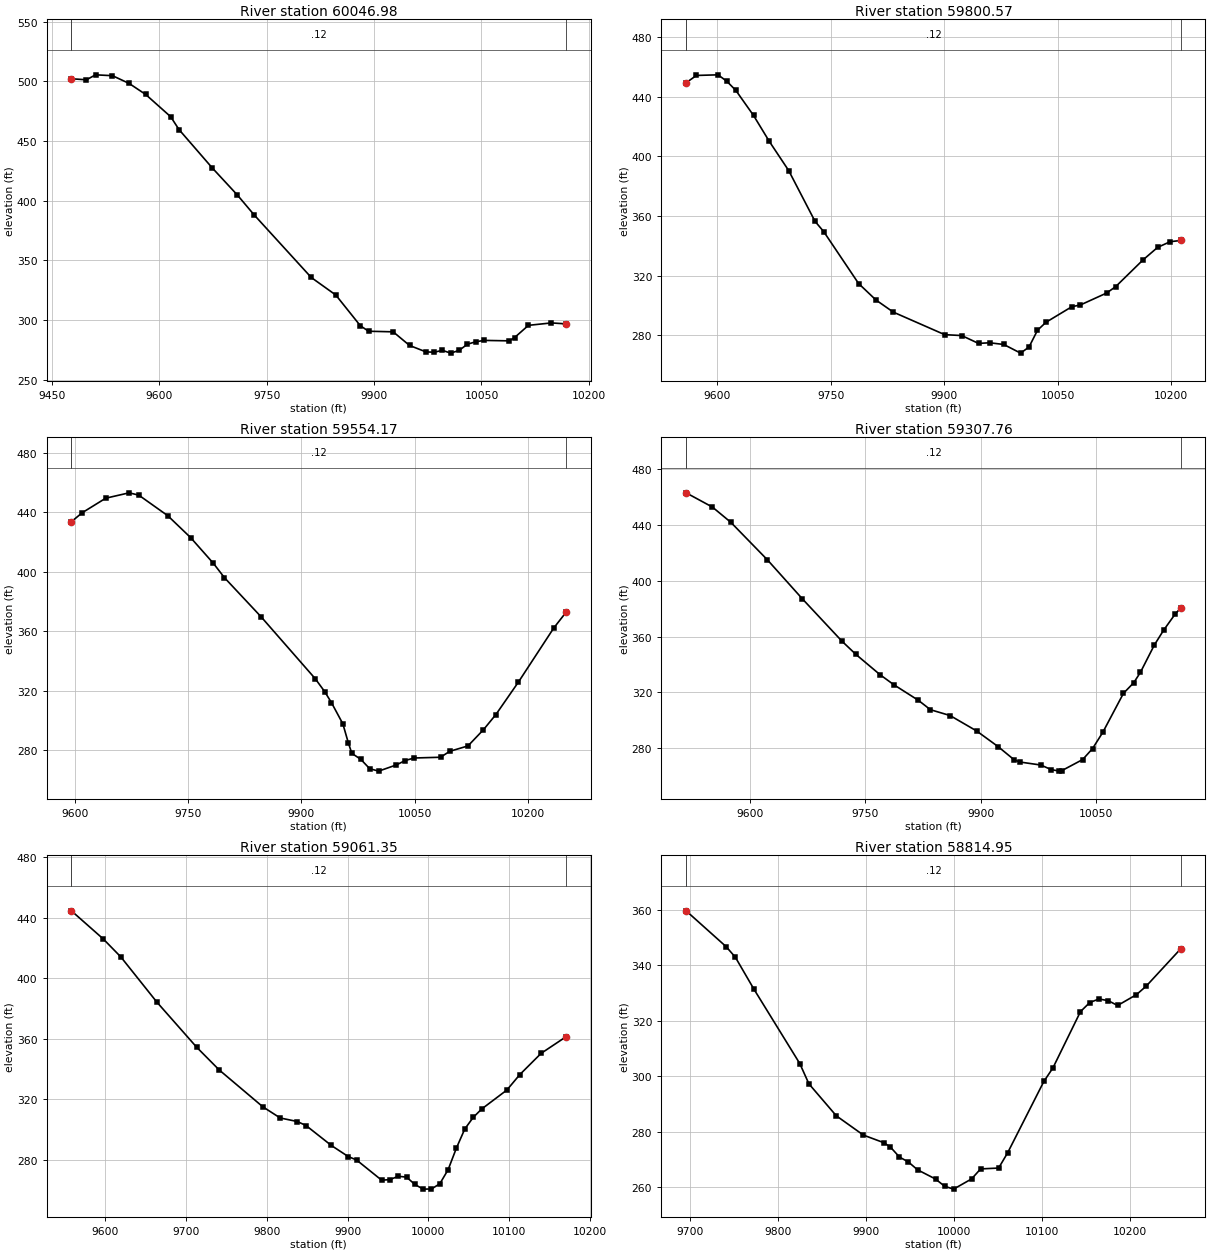
Type RM Length L Ch R = 1 ,60046.98,246.406800,246.406800,246.406800
XS GIS Cut Line= 6
497716.198832699739193.498142923497686.406073522739146.171446546
 497586.55318974738977.689468103497455.346454959738741.899724681
497381.854418472738620.517344538497366.595146839738598.166137999
#Sta/Elev= 30
9477.388502.08759498.409501.19839511.063505.36989534.673504.65419557.922 498.188
 9581.17488.88989616.043470.24849627.667 459.4859674.165427.30249709.038404.7171
9732.236388.22139812.297 335.5579846.609 320.8359880.921 295.0789892.358290.5095
 9926.67290.01669949.545278.5999 9972.42273.21599983.857272.9174 9995.41274.4834
10007.05272.167310018.74274.468110030.43279.666810042.13281.711610053.82282.8356
10088.89282.448310096.22285.203310115.52295.445510147.58297.482810167.96296.6828
#Mann= 3 , 0 , 0
9477.388    0.12       09477.388    0.12       010167.96    0.12       0
#XS Ineff= 2 , 0
       0                               0
Bank Sta=9477.388,10167.96
Exp/Cntr=0.3,0.1

Type RM Length L Ch R = 1 ,59800.57,246.406800,246.406800,246.406800
XS GIS Cut Line= 6
497892.123339684739021.064201551497788.079540275738847.203291344
497745.193474745738770.384955321497657.126851088738594.876336421
497621.976270834738533.157559519497566.556632042738455.035763058
#Sta/Elev= 30
9558.597449.52729572.261454.43739600.859454.85069612.577 450.4469624.296444.4198
9647.733427.56989668.559410.15359694.195390.56159728.985356.48949740.581349.5026
9786.649314.67779809.554303.6394 9832.46295.49929900.391 280.3549922.919279.7487
9945.164274.47239959.793274.90759978.532273.761610000.78267.946410011.94272.0626
10023.11283.290610034.27288.640310068.45299.098310079.96300.322310114.48308.2958
10126.44312.584410162.59330.540210181.89338.955710198.45342.783710212.42 343.598
#Mann= 3 , 0 , 0
9558.597    0.12       09558.597    0.12       010212.42    0.12       0
#XS Ineff= 2 , 0
       0                               0
Bank Sta=9558.597,10212.42
Exp/Cntr=0.3,0.1

Type RM Length L Ch R = 1 ,59554.17,246.406800,246.406800,246.406800
XS GIS Cut Line= 6
498151.526432114738766.807995874498072.283586474738661.749812333
497991.269472107738575.758839677497917.705521725738516.901728971
497748.119083624738408.940416527497662.596299909738341.160156892
#Sta/Elev= 30
9595.694 433.6779610.042439.71429641.131449.48449672.063453.09729684.841451.5482
9723.174437.72119753.341423.02659783.443405.73289798.237395.98419846.701369.6783
9918.268328.06769930.722319.41639939.805311.90249954.863297.65759961.985285.0741
9966.713277.82079978.564273.79049990.415267.469110002.23265.846510025.63 270.021
10037.33  272.9810049.03274.676110084.13275.185310096.13279.150710120.41282.8116
10140.89293.7249 10157.3303.898310187.13325.772410233.97362.209210250.05372.6637
#Mann= 3 , 0 , 0
9595.694    0.12       09595.694    0.12       010250.05    0.12       0
#XS Ineff= 2 , 0
       0                               0
Bank Sta=9595.694,10250.05
Exp/Cntr=0.3,0.1

Type RM Length L Ch R = 1 ,59307.76,246.406800,246.406800,246.406800
XS GIS Cut Line= 6
498276.913989707738643.908286644498185.906924622738503.122834909
498098.326445569738387.675292316498055.482376844738339.909741875
498009.528673236738294.536921012497859.503197853738160.145676854
#Sta/Elev= 30
9517.133462.96359551.312452.75729575.172441.88339622.891414.89559668.103387.0868
9719.435356.81419737.666347.27459769.225332.65269786.921325.55329819.019314.3003
9834.712307.5754 9860.19303.41549894.573 292.4079922.679281.12049943.582271.6656
9950.785 270.1289978.109267.95739991.623264.680210002.39 263.59110005.11263.8549
10032.43271.858710045.31279.711610058.72291.440110085.52319.331610098.92326.9617
10107.54334.342210125.72354.005710137.58364.4393 10152.6 376.02110159.89380.4825
#Mann= 3 , 0 , 0
9517.133    0.12       09517.133    0.12       010159.89    0.12       0
#XS Ineff= 2 , 0
       0                               0
Bank Sta=9517.133,10159.89
Exp/Cntr=0.3,0.1

Type RM Length L Ch R = 1 ,59061.35,246.406800,246.406800,246.406800
XS GIS Cut Line= 6
 498352.70926117738569.616889614498309.894445998738484.765943736
498246.269580001738338.422963066498223.988885965738271.792505572
498170.484187545 738065.49231703498144.474350858737996.630617785
#Sta/Elev= 30
9558.459444.52219597.765 425.9979619.636414.04999664.237384.1837  9713.4354.4221
9741.198339.45529795.284315.05379816.732307.6843 9837.82305.35539848.658302.7064
9879.997289.52649900.784282.23379911.149279.9442 9942.22266.58579952.492266.9801
9962.764269.18449973.035268.61469983.307263.75959993.579260.686710003.85260.7885
10014.14264.236410024.43273.535310034.71287.863710045.04300.420310055.44308.0496
10065.85313.572510097.07326.137110113.15336.373510139.45350.380710170.19361.3111
#Mann= 3 , 0 , 0
9558.459    0.12       09558.459    0.12       010170.19    0.12       0
#XS Ineff= 2 , 0
       0                               0
Bank Sta=9558.459,10170.19
Exp/Cntr=0.3,0.1

Type RM Length L Ch R = 1 ,58814.95,246.406800,246.406800,246.406800
XS GIS Cut Line= 6
498517.973575081 738407.63162955498486.921372279738317.686214332
498467.019564849738246.096848964498411.624403559 738000.75908683
498383.429081262737916.179933543498360.955449251737869.851356881
#Sta/Elev= 30
9695.613359.56599741.006346.69189751.528342.87639772.573331.40249824.716304.6064
9835.096 297.2949866.219285.79129896.954278.85529920.358276.0918 9927.69274.5331
9937.935270.95419948.181269.14829958.426266.37139978.916263.03989989.162 260.454
9999.406259.404710019.86263.080410030.09266.678810050.55266.987610060.78272.4641
10101.96298.169310112.26303.043810143.55323.300310154.01326.539110164.46327.8462
10175.02327.233310185.71325.498310207.12329.405710218.14332.445610257.35345.8893
#Mann= 3 , 0 , 0
9695.613    0.12       09695.613    0.12       010257.35    0.12       0
#XS Ineff= 2 , 0
       0                               0
Bank Sta=9695.613,10257.35
Exp/Cntr=0.3,0.1

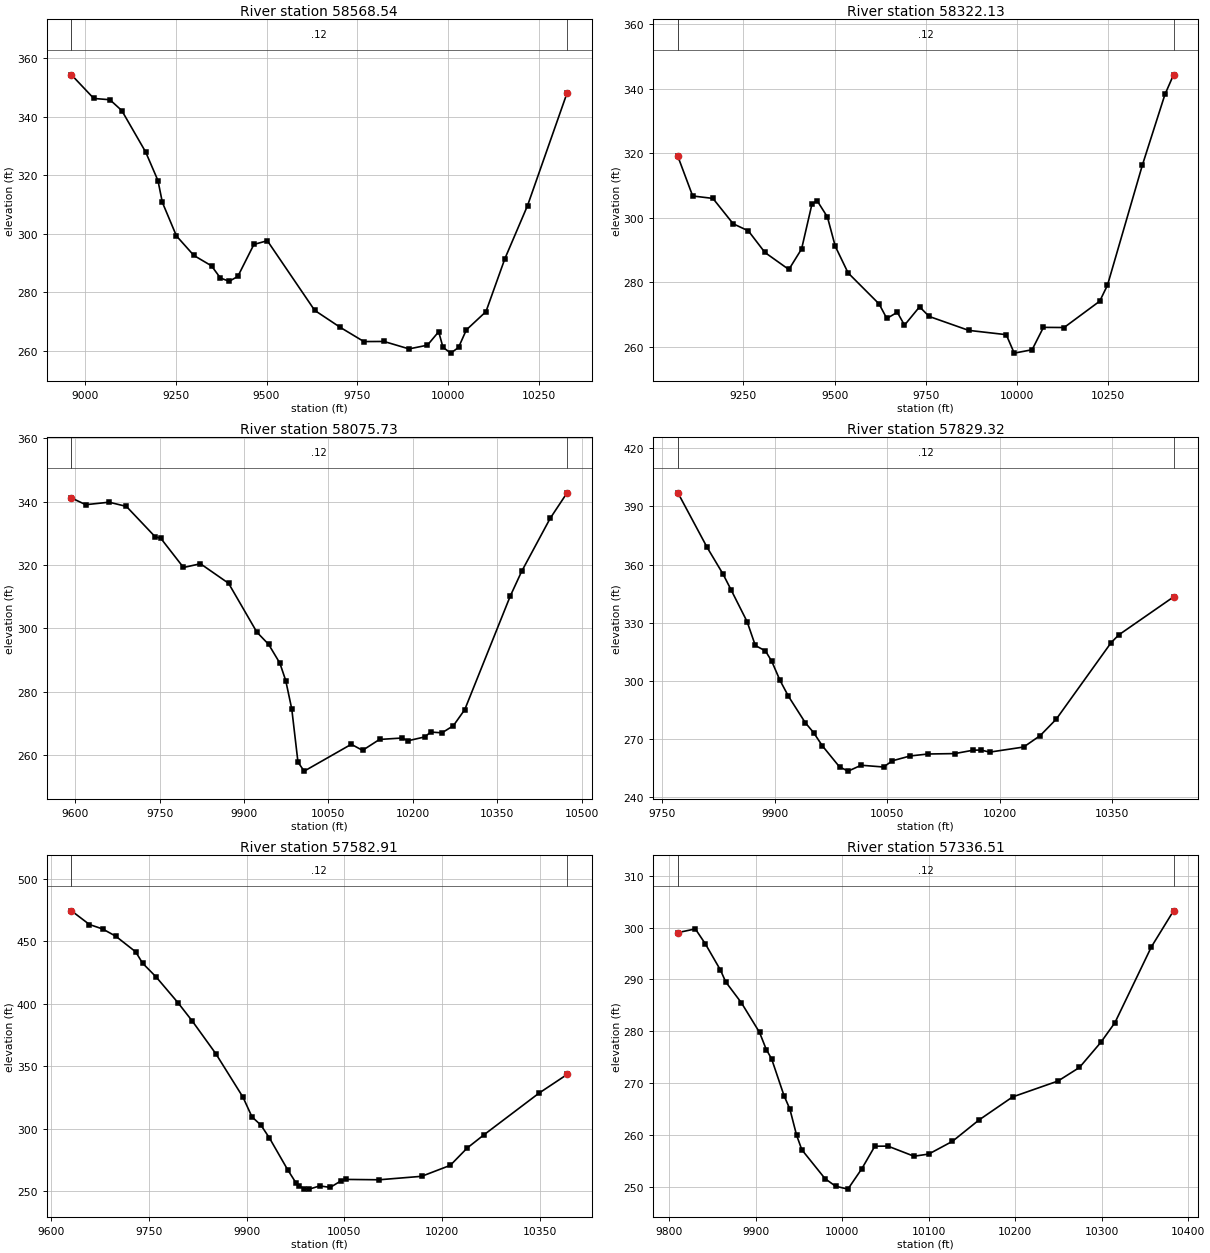
Type RM Length L Ch R = 1 ,58568.54,246.406800,246.406800,246.406800
XS GIS Cut Line= 6
499210.575688688 738932.84923516499013.964350385738674.977372922
498883.755694192 738479.39368698498756.472464798738246.109796259
498608.199575992737894.918579468498508.105633673 737776.49213417
#Sta/Elev= 30
8963.622354.35989025.096346.2833 9069.29345.85499102.047342.1478 9167.66327.9963
9201.526318.22059213.568310.79399252.326299.31799300.081292.66919348.733289.1008
9373.059284.96139397.296283.82399421.091285.4897 9465.27296.41179502.186 297.691
9632.393273.89679702.423268.11089767.721263.23169822.957263.27199891.756260.7299
9942.395261.99899973.364266.59219985.135261.286610006.52259.284810027.94261.2192
10049.35267.211110103.38273.463310155.44291.567110217.68309.681810326.42348.1794
#Mann= 3 , 0 , 0
8963.622    0.12       08963.622    0.12       010326.42    0.12       0
#XS Ineff= 2 , 0
       09873.745                       0
Bank Sta=8963.622,10326.42
Exp/Cntr=0.3,0.1

Type RM Length L Ch R = 1 ,58322.13,246.406800,246.406800,246.406800
XS GIS Cut Line= 6
499534.184862591738600.250917518499120.723678624738195.830125466
498796.389374939737826.576359852498758.780590707737799.607932475
498681.136025557737761.942328073498532.124761714737719.719649696
#Sta/Elev= 30
 9070.46319.02459110.942306.75959166.425306.00349221.908298.1271 9263.52295.9282
9308.919289.21659374.486283.93599409.351290.30649437.666304.20559451.823305.3101
9480.138300.2409 9501.54291.17319536.767282.87859621.711273.2433 9642.81268.7422
9671.713270.6504 9691.32266.64749732.646272.34539758.953269.36049867.148265.0384
9970.112263.70369991.973257.972610040.95259.0219   10072265.969710128.66265.9219
10226.23274.099210247.54279.070310343.07316.323410404.99338.284910428.52344.3716
#Mann= 3 , 0 , 0
 9070.46    0.12       0 9070.46    0.12       010428.52    0.12       0
#XS Ineff= 2 , 0
       09883.417                       0
Bank Sta=9070.46,10428.52
Exp/Cntr=0.3,0.1

Type RM Length L Ch R = 1 ,58075.73,246.406800,246.406800,246.406800
XS GIS Cut Line= 6
499399.378363264737759.889157523499174.646261669 737715.82899677
499054.152201408737720.876175026498967.009982301737755.474031649
498899.624761032 737763.54505293498535.289756495737712.238752938
#Sta/Elev= 30
9593.399341.18579618.788339.06369660.363339.85039691.023338.52119742.019328.9641
9752.131328.46059792.452319.24929822.591320.43389872.596314.26049922.796298.8586
9943.777294.9803  9963.7289.06279974.103283.58549984.869274.57949995.878257.8175
10006.94254.9965 10090.6263.463510110.62261.549410140.73264.992510181.06265.4464
10191.16264.570510221.48265.804410231.58267.321310251.79267.0844   10272269.3317
10292.21274.406310373.05310.226710393.26318.0051 10443.9334.732710474.01342.8088
#Mann= 3 , 0 , 0
9593.399    0.12       09593.399    0.12       010474.01    0.12       0
#XS Ineff= 2 , 0
       0                               0
Bank Sta=9593.399,10474.01
Exp/Cntr=0.3,0.1

Type RM Length L Ch R = 1 ,57829.32,246.406800,246.406800,246.406800
XS GIS Cut Line= 6
499122.573249537737426.353814837 499041.01888439737452.417348445
498994.336980429737473.106451118498699.624465982737644.757115375
498622.070052425 737671.19990301  498522.3303058737683.683658945
#Sta/Elev= 30
9770.736397.02159809.739368.82569830.931355.07839841.562347.00989863.009330.5301
9873.947318.2486 9887.48315.42229895.823310.10799906.761300.3199    9918292.1101
9940.521278.41929951.781273.22239963.213266.51779986.197255.59939997.689253.4045
10015.09256.445810044.88255.529510056.75258.745810080.47261.2387 10104.2262.2404
10139.79262.452110164.43264.203310174.86264.289710186.42263.2131 10231.7265.8365
10253.78271.740210275.17 280.21810348.26319.670410358.46323.683810431.55343.3071
#Mann= 3 , 0 , 0
9770.736    0.12       09770.736    0.12       010431.55    0.12       0
#XS Ineff= 2 , 0
       0                               0
Bank Sta=9770.736,10431.55
Exp/Cntr=0.3,0.1

Type RM Length L Ch R = 1 ,57582.91,246.406800,246.406800,246.406800
XS GIS Cut Line= 6
499062.626182612737162.644517638498967.862819073 737173.99398499
498849.680216971737232.300094807498604.409279149737504.525956232
 498521.08793335737567.449113417498466.401980585 737594.61262249
#Sta/Elev= 30
9630.807474.4797 9658.47463.50529678.567459.97089698.737454.20679729.481441.6135
9740.022432.56619761.106421.36529794.231400.9971 9816.62386.0184 9852.61359.9772
9894.194325.2664 9908.01309.49329921.827302.79739934.733292.6485 9962.95267.0243
9975.826256.41789980.092 254.1449988.701251.94389995.968251.580310012.09 254.148
10028.26252.970410044.43258.109610052.44259.354810103.34259.074710168.62261.8465
10212.56270.6327 10238.6284.532510264.77295.280110349.17328.579210391.95343.3967
#Mann= 3 , 0 , 0
9630.807    0.12       09630.807    0.12       010391.95    0.12       0
#XS Ineff= 2 , 0
       0                               0
Bank Sta=9630.807,10391.95
Exp/Cntr=0.3,0.1

Type RM Length L Ch R = 1 ,57336.51,246.406800,246.406800,246.406800
XS GIS Cut Line= 6
498703.705375399737059.367324263498659.888096788737081.374945488
 498619.20639868737115.309763238498417.969246278737329.986653727
498346.285890937737385.792675329498272.098005564737428.316163176
#Sta/Elev= 30
9809.935299.01759830.084299.73099841.645296.86079859.116291.81529865.254289.5276
9883.391285.50339904.339279.8101 9912.14276.51099918.228274.75159932.699267.6123
 9939.38265.0689 9947.17260.02759953.215257.22949980.053251.66919992.188250.2128
10006.51249.647510022.54253.557910037.64257.903810052.74257.926910082.93 255.981
10099.95256.395510127.31258.838410158.12262.957310196.99267.395810249.47270.4541
10274.27273.063510298.99277.897210315.26281.679110357.44296.274710383.06303.2112
#Mann= 3 , 0 , 0
9809.935    0.12       09809.935    0.12       010383.06    0.12       0
#XS Ineff= 2 , 0
       0                               0
Bank Sta=9809.935,10383.06
Exp/Cntr=0.3,0.1

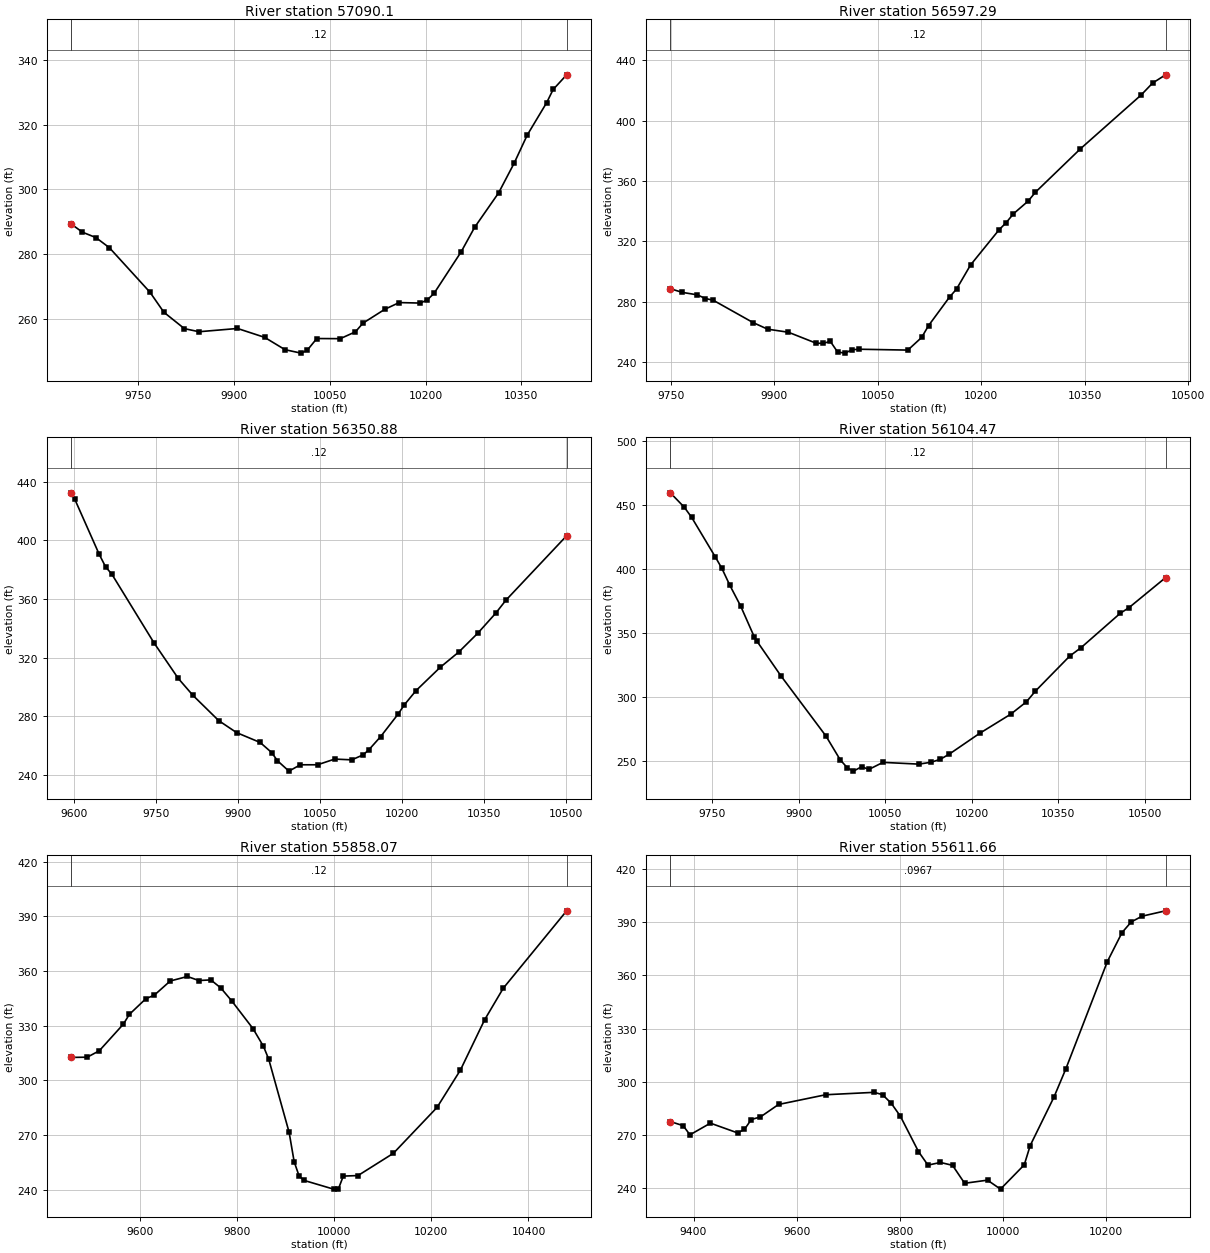
Type RM Length L Ch R = 1 , 57090.1,492.813700,492.813700,492.813700
XS GIS Cut Line= 6
498701.600355088737014.881579545498527.910725806736952.931675993
498475.039576763736951.429841832 498217.87876038737113.831694054
498098.882118675 737153.82313179497994.014705425737172.792330064
#Sta/Elev= 30
9645.405289.18379662.687286.70529683.731285.04099704.775281.92049768.386268.1468
9790.165261.95179822.305256.8691 9845.29255.91219905.524256.92079947.959254.1783
9979.933250.359210004.98249.292810014.47250.1147 10029.7253.805410066.49253.7662
 10090.2255.880810102.05258.5662 10136.4262.871510158.82264.932510191.87264.7794
10202.65265.728710213.44 267.79710255.95280.673610276.89288.195210314.42298.8418
10338.84308.057310359.28316.7337 10389.8 326.79110399.92330.854710421.07335.3911
#Mann= 3 , 0 , 0
9645.405    0.12       09645.405    0.12       010421.07    0.12       0
#XS Ineff= 2 , 0
       0                10155.77       0
Bank Sta=9645.405,10421.07
Exp/Cntr=0.3,0.1

Type RM Length L Ch R = 1 ,56597.29,246.406800,246.406800,246.406800
XS GIS Cut Line= 6
498701.554451825737012.081480512498626.182498321736973.875994376
498601.523371682736928.622700144498624.326457735 736759.60310094
498613.752516592 736643.46308774498495.582873599736379.261465045
#Sta/Elev= 30
9749.095288.68899766.594286.26379788.429284.63159799.707282.21049810.986281.1441
9869.102266.26129890.105261.9107 9920.28259.87449960.548  252.619970.797252.5451
9981.059253.81459991.594246.783210002.21246.041110012.66248.292710023.12248.6241
10093.45248.050210113.47 256.43510123.58264.3344 10153.9283.174710164.01288.4519
10184.41304.4561 10225.7327.723410236.02332.469610246.61338.356510267.87346.7476
10278.49352.641410343.75381.407610431.79417.060710448.31424.926610467.15430.3902
#Mann= 3 , 0 , 0
9749.095    0.12       09749.095    0.12       010467.15    0.12       0
#XS Ineff= 2 , 0
       0                               0
Bank Sta=9749.095,10467.15
Exp/Cntr=0.3,0.1

Type RM Length L Ch R = 1 ,56350.88,246.406800,246.406800,246.406800
XS GIS Cut Line= 6
499090.539654879737050.990628565499000.745479396737000.287942069
498921.652961869736919.334618309498878.443659761736839.808186837
498755.075937642736493.866913783498628.184562656736302.861816372
#Sta/Elev= 30
9595.861432.46239601.991428.09329646.708390.46569658.278382.02269669.878376.9056
9746.655330.23719791.152305.90339817.908294.38259865.074 277.144  9897.7268.9758
9940.815262.24599961.911255.35299972.413249.78739993.417242.702610014.33247.0297
10045.67247.026410077.01250.915810108.34250.393210129.25253.834110139.86257.3894
10161.08266.252110193.32 281.76210204.12287.798210225.72 297.59110269.96313.4955
10304.03323.953410338.62336.753410371.36350.373910389.94359.213410501.03403.1869
#Mann= 3 , 0 , 0
9595.861    0.12       09595.861    0.12       010501.03    0.12       0
#XS Ineff= 2 , 0
       0                               0
Bank Sta=9595.861,10501.03
Exp/Cntr=0.3,0.1

Type RM Length L Ch R = 1 ,56104.47,246.406800,246.406800,246.406800
XS GIS Cut Line= 6
499294.215168186736883.955966676499222.314320031736825.303303496
499162.222095228736765.896774911499110.212004094736704.483092633
498969.330374462736517.045086755  498719.7888808736250.083169488
#Sta/Elev= 30
9677.907459.75779702.203 448.4169714.847440.55379755.843409.64379767.186400.7452
9781.012 387.4929799.606371.42829823.197347.33819828.054343.79869869.506316.7959
9947.475269.82339972.301251.16689984.714244.93369995.141242.435510009.41245.9308
10021.69243.743210046.25249.272110108.59247.898210129.45249.381310145.35251.6062
10161.25255.7742 10213.6271.911410267.69286.950710294.73296.571610310.41304.9951
10369.83332.321310389.41338.875410457.05365.619410472.51370.135210535.76393.5375
#Mann= 3 , 0 , 0
9677.907    0.12       09677.907    0.12       010535.76    0.12       0
#XS Ineff= 2 , 0
       0                               0
Bank Sta=9677.907,10535.76
Exp/Cntr=0.3,0.1

Type RM Length L Ch R = 1 ,55858.07,246.406800,246.406800,246.406800
XS GIS Cut Line= 6
 499661.20330111 736684.41769884499372.919694036736498.714866698
499270.079427063736461.088637441 499104.85427019736436.319542304
499020.995704889736403.297251225498775.341840982736218.075834811
#Sta/Elev= 30
 9459.52312.58129492.014312.69919516.815316.22219566.418 330.8539578.699336.2045
9612.501344.76949630.221346.79949662.805354.5401 9698.14357.02279721.633354.8039
9746.388355.14379766.793350.73879789.374 343.6239833.118328.39519854.684 318.655
9865.467311.62849907.493271.40079917.828255.31279928.066247.41629938.304245.0298
9998.837240.246710008.87240.356610018.92247.407110049.21247.696610122.01259.9211
10211.83285.116710259.95305.634510309.68333.203610348.12350.572810478.54393.0786
#Mann= 3 , 0 , 0
 9459.52    0.12       0 9459.52    0.12       010478.54    0.12       0
#XS Ineff= 2 , 0
       0                               0
Bank Sta=9459.52,10478.54
Exp/Cntr=0.3,0.1

Type RM Length L Ch R = 1 ,55611.66,246.406800,246.406800,246.406800
XS GIS Cut Line= 6
499783.793549393736609.466148079499538.529292643736399.126084387
499462.393546492736340.487181857499404.053578645736300.176543102
499318.928866923736247.801830173498997.915477216736061.503367156
#Sta/Elev= 30
9354.986 277.4089379.842275.08159393.067269.91969432.744276.51089485.646 270.987
9498.872272.99899512.097278.56269529.893 280.039    9565287.0704 9656.62292.5775
9750.417293.92959766.805292.63019783.853287.70719801.445280.45219836.628260.4358
9854.991252.78279879.225254.28969902.707252.6675 9926.19 242.5189970.604244.2861
9995.823239.211810041.93252.946710053.45263.838310099.53291.206510122.58307.1572
10203.23367.858610231.79384.279210249.63390.270410270.61393.521310316.23396.5467
#Mann= 3 , 0 , 0
9354.986  0.0967       09354.986  0.0967       010316.23  0.0967       0
#XS Ineff= 2 , 0
       0                               0
Bank Sta=9354.986,10316.23
Exp/Cntr=0.3,0.1

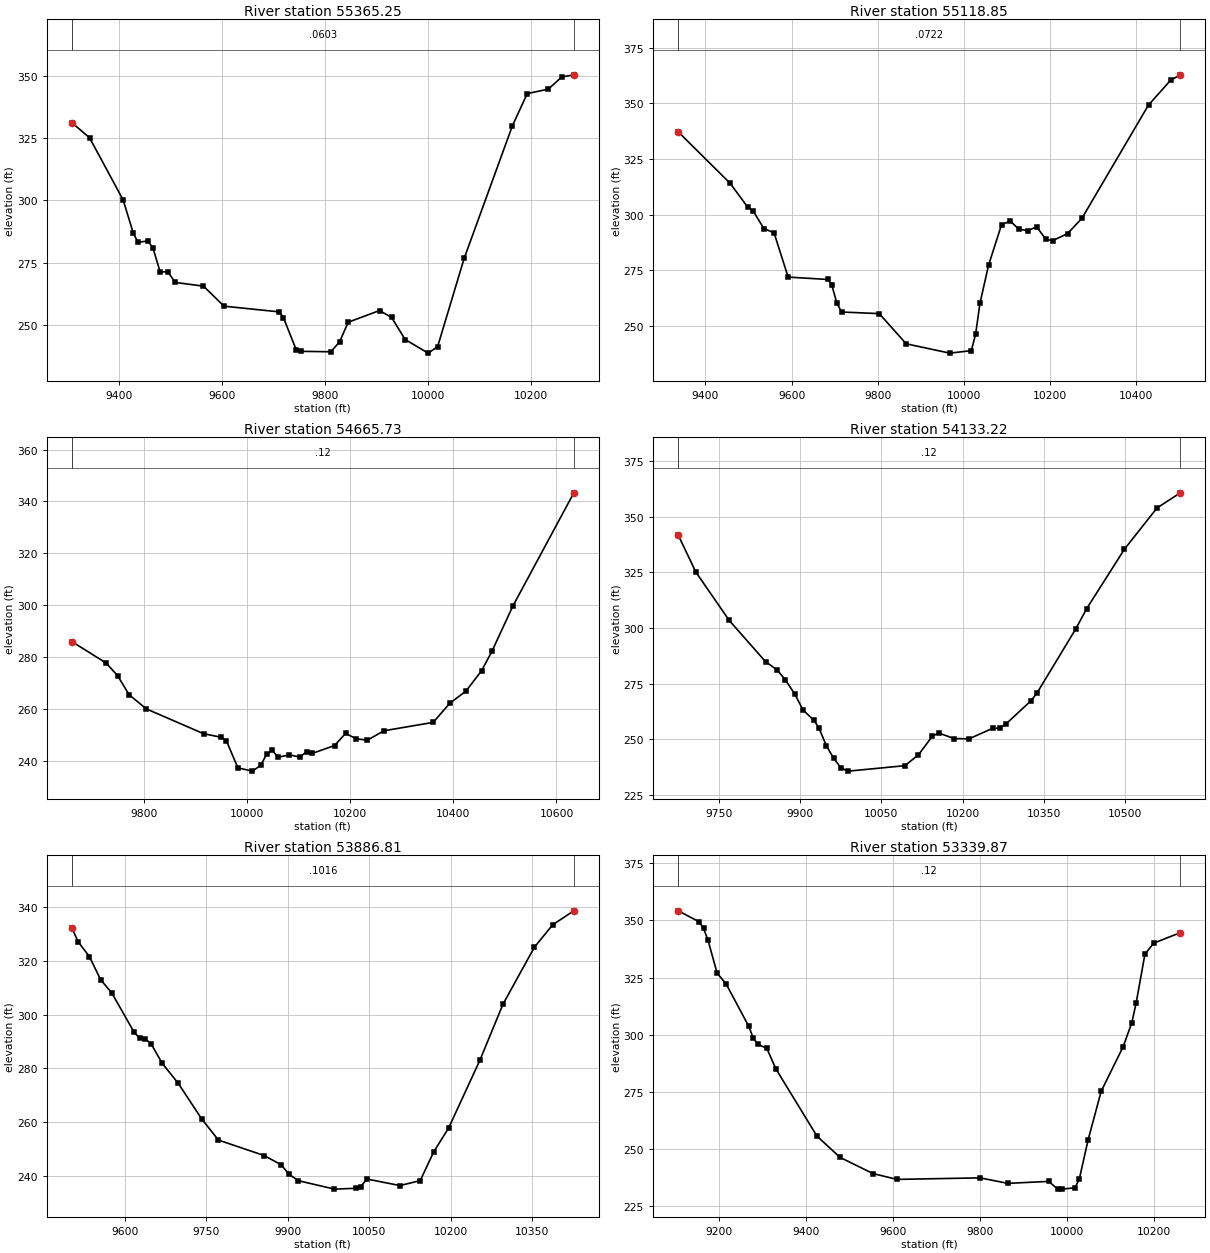
Type RM Length L Ch R = 1 ,55365.25,246.406800,246.406800,246.406800
XS GIS Cut Line= 6
499866.570868184736558.856181151499730.852421135736422.712258995
499665.768170208736349.156405151499356.260363489735949.016973451
499273.291926056735864.083867878499226.448890388735826.044699088
#Sta/Elev= 30
 9308.39331.29259342.871325.21579408.332300.17299427.961286.82899437.119283.2079
9455.768283.70829465.905281.09759480.298271.17829494.691271.43179509.492267.0681
9564.369265.57249604.245257.53089711.788255.22869719.587252.97089744.643239.9615
9754.348239.38129811.826239.21049828.685243.15659845.545251.07259906.405255.7802
9929.842253.01769956.169244.1384   10001238.663510019.33241.270810071.03 276.814
10164.76330.063310193.44 342.922 10234.5344.748410260.62349.622410284.04350.4779
#Mann= 3 , 0 , 0
 9308.39  0.0603       0 9308.39  0.0603       010284.04  0.0603       0
#XS Ineff= 2 , 0
       0                               0
Bank Sta=9308.39,10284.04
Exp/Cntr=0.3,0.1

Type RM Length L Ch R = 1 ,55118.85,453.116400,453.116400,453.116400
XS GIS Cut Line= 6
499942.144515161736512.650531706499774.937764883  736320.4522921
499697.098139137736188.687218949499602.939647377735722.355125621
499526.780085355735652.548941895499362.528863966735607.960579008
#Sta/Elev= 30
9336.994337.16859457.496314.0367 9497.69303.4552 9510.39301.75839535.663293.7204
9559.325291.81199591.948271.93189685.224270.85399693.144268.42819704.585260.4954
 9715.79256.25069803.359255.52479865.917241.96279966.919237.781610016.93 238.887
10026.93246.373910036.93260.087610056.94277.295210086.99295.415110107.17297.1016
10127.36293.421810147.95292.788910168.56294.5223   10190288.827810205.77288.3343
10240.16291.453710273.57298.345510428.06349.239310479.06360.302210501.77362.7739
#Mann= 3 , 0 , 0
9336.994  0.0722       09336.994  0.0722       010501.77  0.0722       0
#XS Ineff= 2 , 0
       0                               0
Bank Sta=9336.994,10501.77
Exp/Cntr=0.3,0.1

Type RM Length L Ch R = 1 ,54665.73,532.510800,532.510800,532.510800
XS GIS Cut Line= 4
 500355.16926524735947.530491933499923.033403397735738.605302528
499660.537652612735643.963977426499448.041092455735611.821640581
#Sta/Elev= 30
9659.723286.07989726.556277.80689748.771272.90199770.985265.60399804.308260.1665
9915.382250.61959948.704249.26659959.811247.80619982.026237.463210010.15236.2064
10026.46238.472310037.56242.673410048.67244.257710059.78241.548110081.99242.4622
10102.05 241.62910115.31243.640610126.42243.042710169.51246.067710190.77250.7069
10212.03248.637210233.29248.129110265.18 251.73710360.86254.972410392.75262.2881
10424.35267.008310454.69274.849610474.92282.393110515.37299.745410633.66343.3326
#Mann= 3 , 0 , 0
9659.723    0.12       09659.723    0.12       010633.66    0.12       0
#XS Ineff= 2 , 0
       0                               0
Bank Sta=9659.723,10633.66
Exp/Cntr=0.3,0.1

Type RM Length L Ch R = 1 ,54133.22,246.406800,246.406800,246.406800
XS GIS Cut Line= 6
500137.072356441735195.110223885500039.540047139735215.571826383
499954.955515265735263.836102888499658.165966839735570.421318516
 499564.08447057735599.934594736499362.034031451735594.105267376
#Sta/Elev= 30
9674.643341.69649706.929325.21729768.896303.4075 9835.91284.91829857.219281.2369
9872.359276.82129889.825 270.4599905.353263.19189925.571258.52549934.367255.3059
9948.297247.1997 9961.87241.59069975.443237.16689989.015235.787610093.35238.2289
10118.52 243.07710144.36251.506310156.26252.874510184.09250.4289 10211.9250.2725
10255.44254.971910268.47255.097410280.82257.065110326.66 267.39710337.41270.7476
10409.23299.576110429.27308.640410499.32335.408710559.43353.876710602.48360.6717
#Mann= 3 , 0 , 0
9674.643    0.12       09674.643    0.12       010602.48    0.12       0
#XS Ineff= 2 , 0
       0                               0
Bank Sta=9674.643,10602.48
Exp/Cntr=0.3,0.1

Type RM Length L Ch R = 1 ,53886.81,546.940700,546.940700,546.940700
XS GIS Cut Line= 6
500076.394943476735123.783203334499813.513256341735056.052929029
499727.066390783735121.305514053499512.492812842735410.521218404
499450.425029546735461.609380201499358.924620748735507.041766211
#Sta/Elev= 30
9502.795332.42649514.562327.17519535.215321.69369555.868313.09269576.521308.1097
9617.827293.40519628.154291.21789638.481291.01849648.807289.1922 9669.46281.8621
 9698.32274.60599741.746261.27569772.726 253.3369857.279247.5384 9888.09 244.139
9902.909240.56729920.035238.18899986.422 235.05510026.23235.373110034.47236.0049
10046.45238.8106 10106.8236.3819 10144.2238.225110169.24 248.99410196.65257.8733
10254.11283.084210296.45303.889610354.48325.189410388.17333.548310427.03 338.723
#Mann= 3 , 0 , 0
9502.795  0.1016       09502.795  0.1016       010427.03  0.1016       0
#XS Ineff= 2 , 0
       0                               0
Bank Sta=9502.795,10427.03
Exp/Cntr=0.3,0.1

Type RM Length L Ch R = 1 ,53339.87,685.093400,685.093400,685.093400
XS GIS Cut Line= 6
500151.070691228735118.755670458499828.342574656735022.513482347
499742.333751142734989.304424793499673.289849728734957.074699447
499369.551873356734847.573591173499044.031040013734812.851368964
#Sta/Elev= 30
9105.051354.17899152.948349.41819163.344346.47669173.741341.21199194.533326.9227
9215.326322.16169267.308 303.6489277.704298.52889288.101295.77489308.893293.9813
9329.873284.96949424.376255.56129477.609246.24959553.194239.19639608.373236.6484
9799.783237.30949863.563234.90739957.825235.76959977.939232.41019987.995232.3829
10018.17232.976410028.22236.938310048.34253.982110078.51275.274810128.79294.6503
 10148.9305.206110158.96313.957210179.07335.209410199.19340.0206 10260.5344.6272
#Mann= 3 , 0 , 0
9105.051    0.12       09105.051    0.12       0 10260.5    0.12       0
#XS Ineff= 2 , 0
       0                               0
Bank Sta=9105.051,10260.5
Exp/Cntr=0.3,0.1