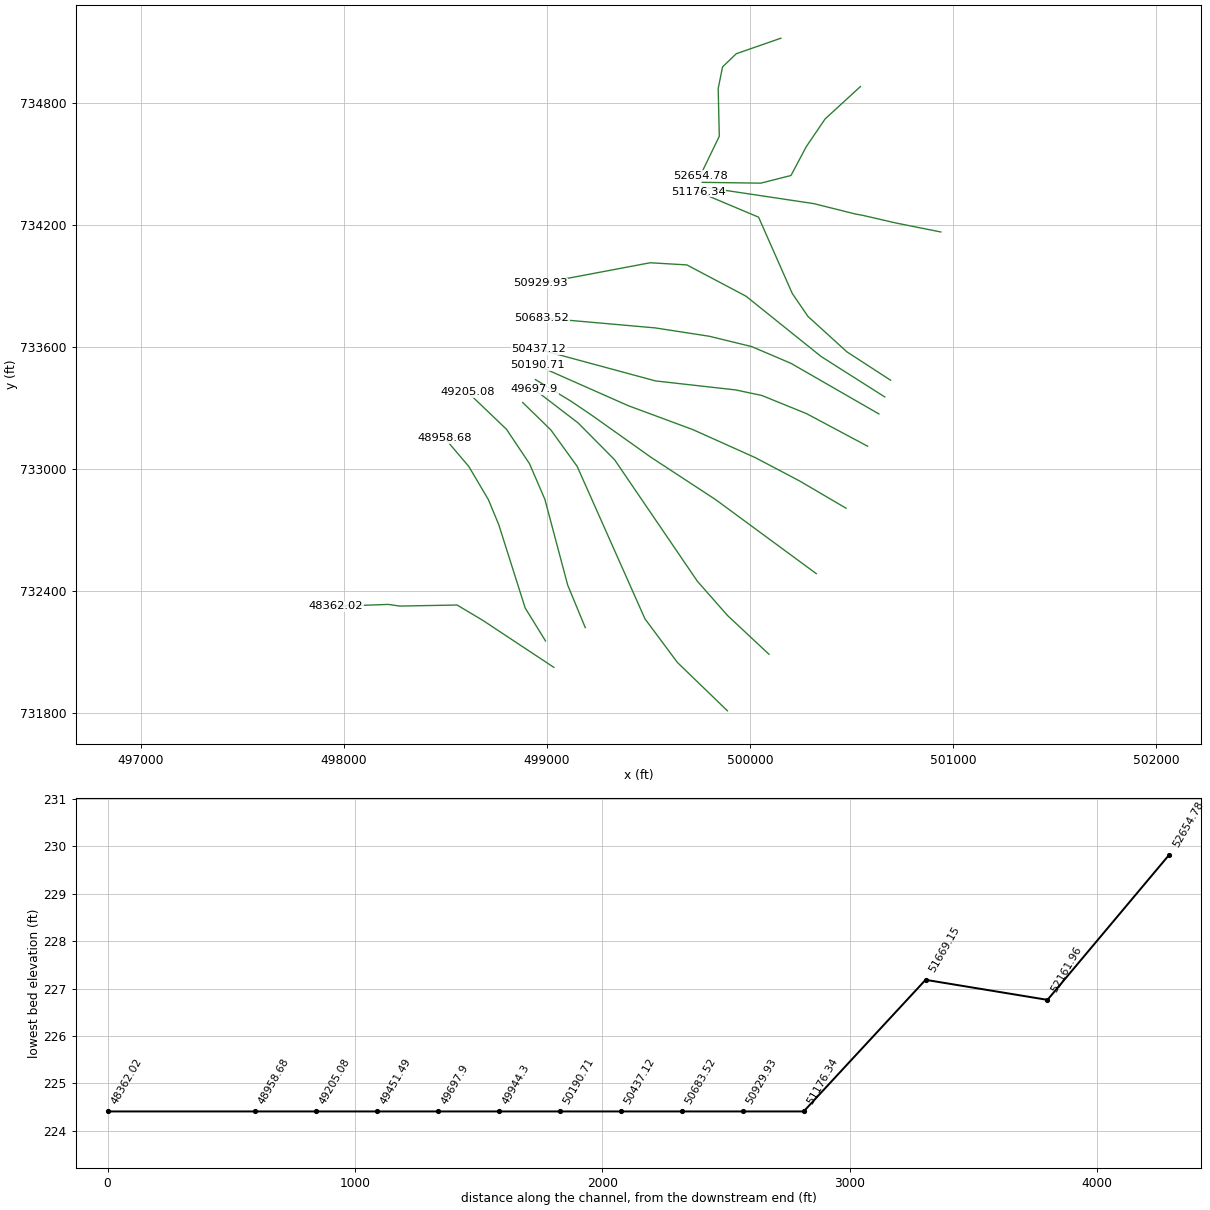
HEC-RAS study 978_ras.prj: 978

--- 978_ras.g01 (geometry) --- (continued)

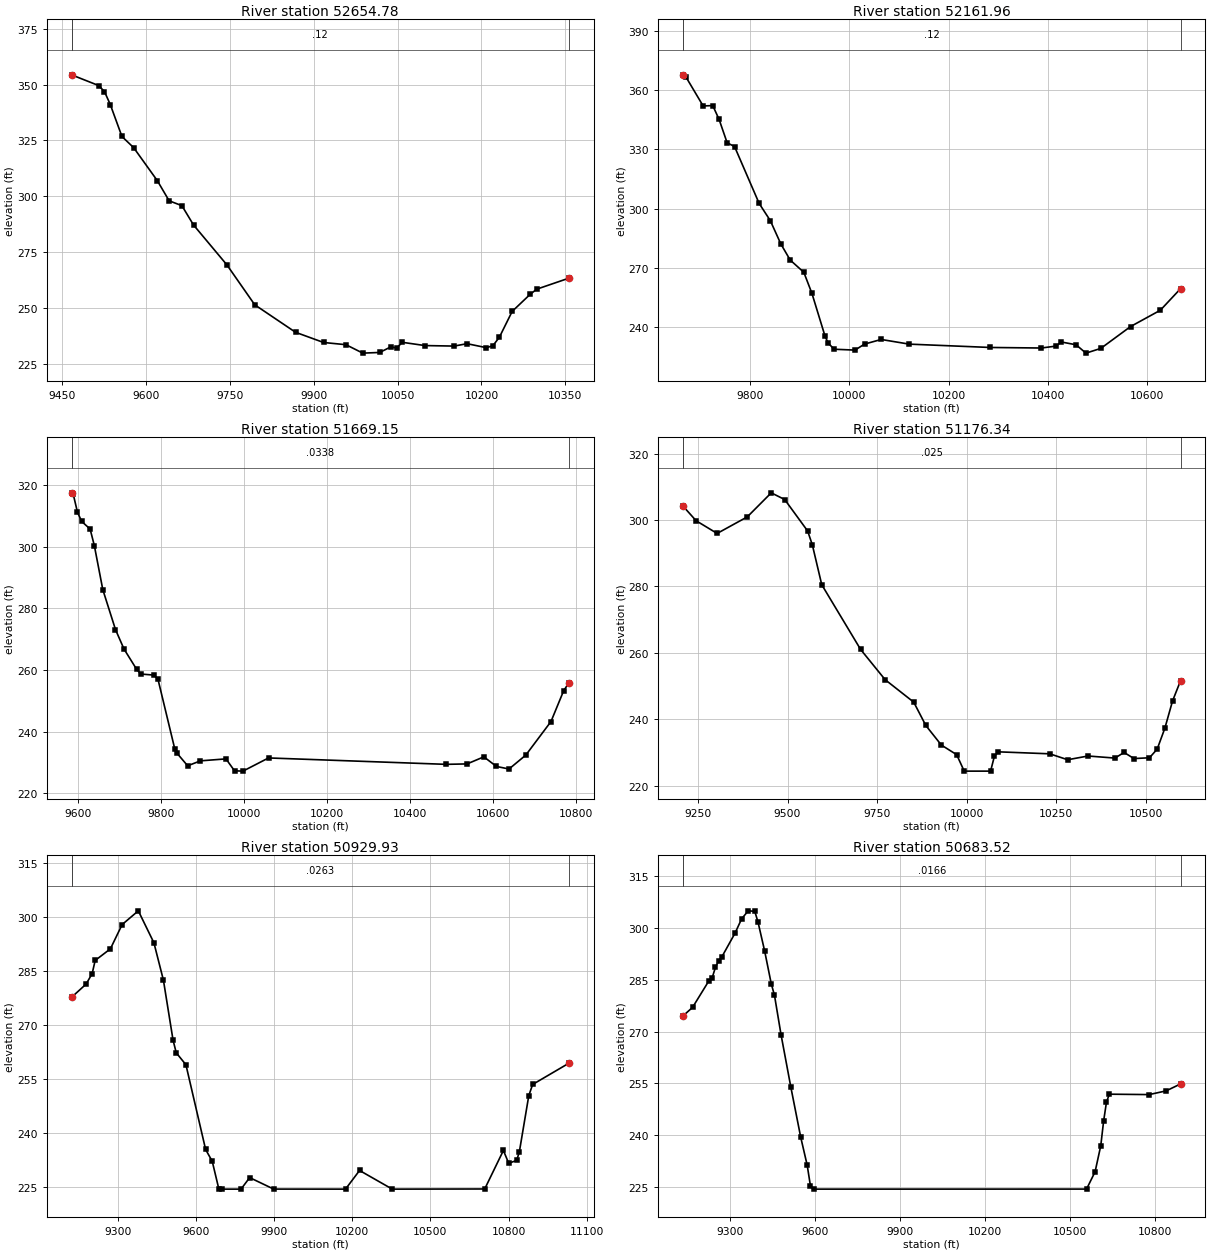
Type RM Length L Ch R = 1 ,52654.78,492.813600,492.813600,492.813600
XS GIS Cut Line= 6
500151.584335297735115.953976259499931.996807545735039.806623325
499864.294435322734975.054013833499842.863917083734868.884797066
499848.317899048734634.566112578499754.167257965734440.255215123
#Sta/Elev= 30
9466.357 354.3589514.882349.56339525.298346.84979535.715341.05599556.548326.7691
9577.555321.76249619.806307.02599641.035297.98889663.833 295.8149684.686287.1676
9744.481269.29119794.229251.4544 9867.27239.15149917.364234.59179957.413233.6017
9987.629229.827810017.89 230.12710038.07  232.6710048.16232.064310058.25234.6696
10098.81233.211310151.02232.979810174.18234.053710208.91 232.25610220.48233.1587
10232.06236.962110254.92248.4993 10287.1256.138610298.92258.445610356.54263.3816
#Mann= 3 , 0 , 0
9466.357    0.12       09466.357    0.12       010356.54    0.12       0
#XS Ineff= 2 , 0
       0                               0
Bank Sta=9466.357,10356.54
Exp/Cntr=0.3,0.1

Type RM Length L Ch R = 1 ,52161.96,492.813600,492.813600,492.813600
XS GIS Cut Line= 6
500543.146315813734878.572052971500369.296416849734719.563174084
500276.377728581734583.159486383500201.263115644 734441.83733049
500052.644822061734404.197522819499764.183283627 734408.20393306
#Sta/Elev= 30
9664.609 367.7569670.731  366.489705.012351.97939724.369352.18589737.206345.1393
9753.388333.33319768.337331.42219817.992302.59149840.494293.88299861.769282.0509
9880.634273.9113  9908.1267.71369924.511256.9919 9950.72235.50279957.022 231.935
9969.196228.735610011.37228.293410030.54231.3402 10064.1233.6835 10120.8231.3197
10284.34229.626910387.26 229.35210417.26230.339310427.26232.420710457.26230.9986
10477.27226.762610507.27229.161910567.27240.231710627.28248.4802 10668.1259.4137
#Mann= 3 , 0 , 0
9664.609    0.12       09664.609    0.12       0 10668.1    0.12       0
#XS Ineff= 2 , 0
       0                               0
Bank Sta=9664.609,10668.1
Exp/Cntr=0.3,0.1

Type RM Length L Ch R = 1 ,51669.15,492.813600,492.813600,492.813600
XS GIS Cut Line= 6
500939.046148896734164.420070454500719.512495577734208.189256251
500554.510530442734246.134171829500515.457047969734253.318202645
500313.528118581734303.666626021499762.180078477734386.168676645
#Sta/Elev= 30
9585.288317.47349589.402317.01639599.572311.17979609.742308.19949630.081305.7117
9640.251300.3323 9660.59286.09019691.201273.10029711.628266.81739742.269260.1836
9752.482 258.6889783.123258.34589793.336257.11879834.307 234.2339839.544232.9727
 9865.09 228.9149895.873230.52259957.439231.15779977.961227.28689998.307227.1853
10059.97231.461710487.77229.386110538.31 229.52610578.75231.821710609.08228.6999
10639.41227.876410679.85232.3912 10740.5243.277410770.83253.201810783.79255.8847
#Mann= 3 , 0 , 0
9585.288  0.0338       09585.288  0.0338       010783.79  0.0338       0
#XS Ineff= 2 , 0
       0                               0
Bank Sta=9585.288,10783.79
Exp/Cntr=0.3,0.1

Type RM Length L Ch R = 1 ,51176.34,246.406800,246.406800,246.406800
XS GIS Cut Line= 6
500691.713054121733436.477073461500476.741486907733575.684421271
500284.702113301733749.921361014500207.655216336733862.324613854
500041.749664396734237.098792106499744.151232332734362.130215123
#Sta/Elev= 30
9208.342304.16099244.647299.79199303.303295.96979387.649300.96519454.466 308.197
9492.087306.17469556.136296.70419569.266292.51959595.525280.53179704.093261.0399
9772.622 251.935 9852.46245.17189886.235238.14749929.597232.25999972.365229.3639
9993.429 224.40910067.11 224.40910077.64228.838710088.17  230.2210232.37229.6223
10282.37227.837910339.27 228.96210414.37228.337610440.02230.029710467.61228.1885
10510.93228.436610532.39231.028910553.85237.319910575.31245.529710597.68251.6156
#Mann= 3 , 0 , 0
9208.342   0.025       09208.342   0.025       010597.68   0.025       0
#XS Ineff= 2 , 0
       0                               0
Bank Sta=9208.342,10597.68
Exp/Cntr=0.3,0.1

Type RM Length L Ch R = 1 ,50929.93,246.406900,246.406900,246.406900
XS GIS Cut Line= 6
500663.020432234733354.311837912500349.985676795733552.653924659
499979.741824746733849.173344985499688.615823835734002.735492408
 499508.10230422 734013.32056658498967.367264439733911.660261832
#Sta/Elev= 30
9123.294277.74369179.085281.41339202.321284.32689213.939287.99329272.336291.2226
9317.331297.97049379.434301.79289439.271292.90269475.747282.50919512.551265.8865
9524.929262.31939562.063258.98959637.597 235.4349662.998 232.1449688.399224.4129
9701.364 224.409 9773.42 224.4099806.578227.61529898.641 224.42110174.19 224.409
10228.08229.597110353.53 224.40910708.11 224.45110779.77235.154210800.24231.5914
10830.95232.406310841.18234.860510877.18250.402310892.05253.519311031.26259.4321
#Mann= 3 , 0 , 0
9123.294  0.0263       09123.294  0.0263       011031.26  0.0263       0
#XS Ineff= 2 , 0
       0                               0
Bank Sta=9123.294,11031.26
Exp/Cntr=0.3,0.1

Type RM Length L Ch R = 1 ,50683.52,246.406800,246.406800,246.406800
XS GIS Cut Line= 6
 500633.93234241733271.014126137 500201.39123413733519.285084963
500007.801478297733601.618303746499799.087504119733652.385495126
499532.677463263733693.388838425498974.509887629733742.618179041
#Sta/Elev= 30
9135.865274.58689169.149277.02529226.669284.70059238.173285.55419249.677288.5682
9261.182290.51849272.732291.68969319.066298.53599342.233302.6553  9365.4304.9743
9388.567304.8325 9400.15301.65369423.317293.35589446.484 283.9349458.068280.4954
9481.235269.08899515.985253.83479550.625239.41739573.447231.31689584.857225.3519
9596.268 224.40910558.63224.422710588.72229.434910608.78 236.99210618.81244.1204
10628.84249.557810638.87251.895510779.29251.775510839.47252.857110890.11254.8608
#Mann= 3 , 0 , 0
9135.865  0.0166       09135.865  0.0166       010890.11  0.0166       0
#XS Ineff= 2 , 0
       0                               0
Bank Sta=9135.865,10890.11
Exp/Cntr=0.3,0.1

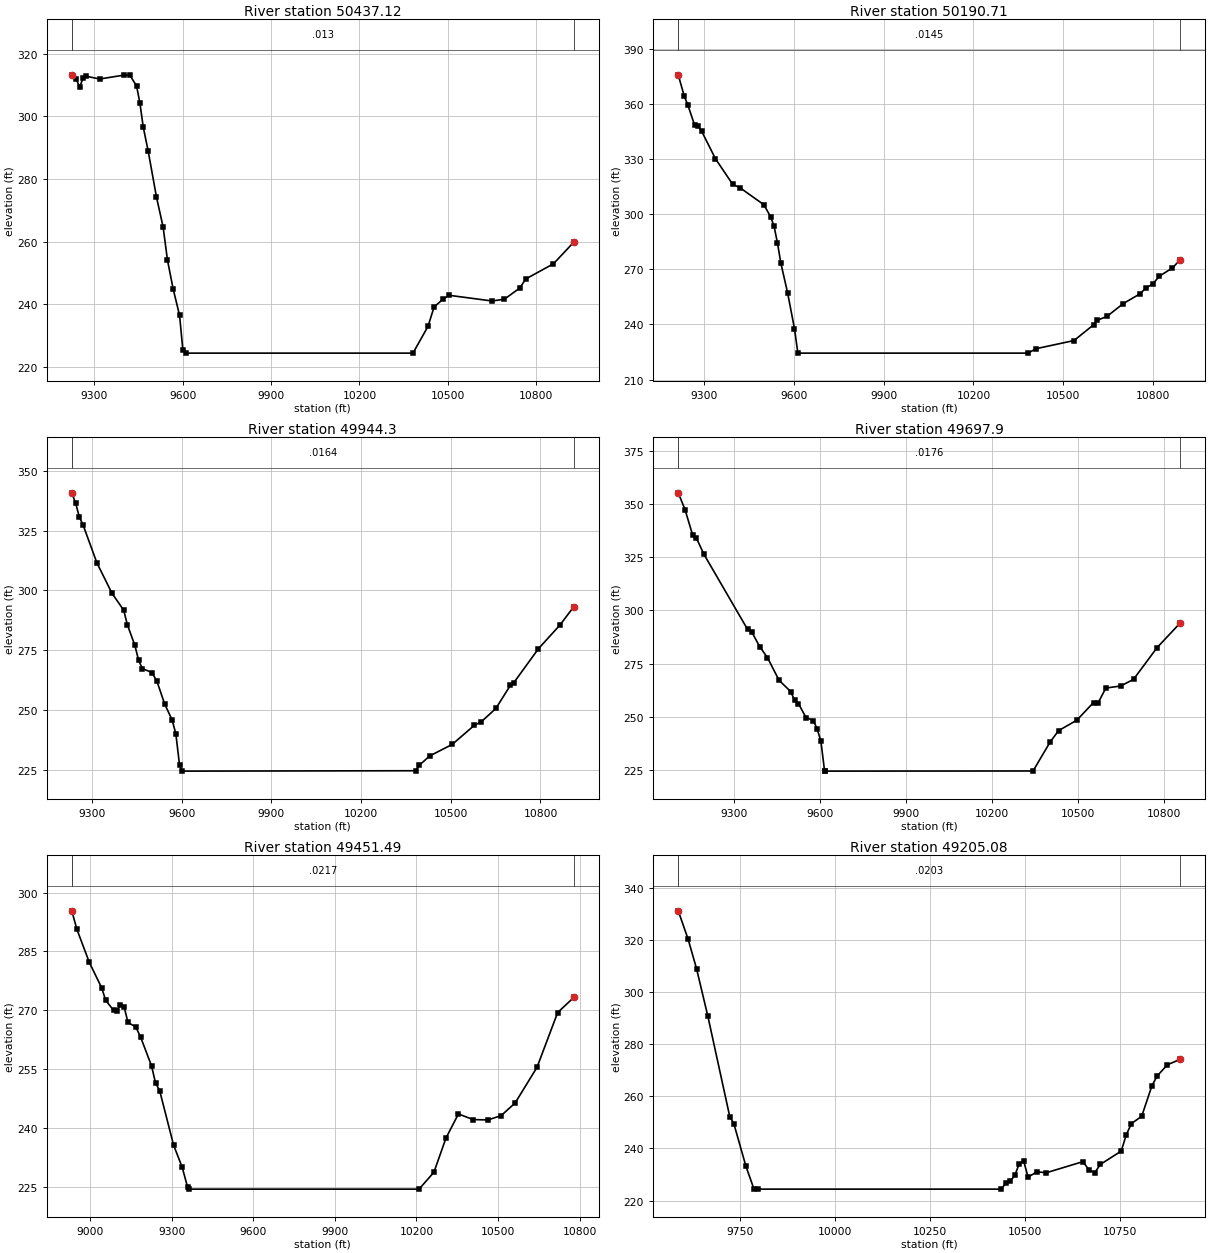
Type RM Length L Ch R = 1 ,50437.12,246.406800,246.406800,246.406800
XS GIS Cut Line= 6
500578.544835538733112.404447407500276.918608904733272.815944165
500057.739866555733361.566142693 499928.41932115  733388.9433081
 499534.75338161733432.938581094498958.816243092733588.299255183
#Sta/Elev= 30
9223.777313.20849239.193311.81469250.575309.22859261.957312.2003 9271.09312.7788
9318.867311.88089402.513313.14599421.114313.06449443.647309.65569454.914304.2976
9466.181296.61949483.337288.75639511.249274.20569533.782264.64369548.456254.1509
9567.542245.00639589.653236.43729600.708225.49999611.763 224.409 10381.7 224.409
10432.79232.953610453.33239.130810484.23241.690310504.82242.855110649.86241.0477
10691.61241.5904 10743.8245.143610764.68248.084110858.62252.9217 10927.7259.8381
#Mann= 3 , 0 , 0
9223.777   0.013       09223.777   0.013       0 10927.7   0.013       0
#XS Ineff= 2 , 0
       0                               0
Bank Sta=9223.777,10927.7
Exp/Cntr=0.3,0.1

Type RM Length L Ch R = 1 ,50190.71,246.406800,246.406800,246.406800
XS GIS Cut Line= 6
 500472.25428018 732808.02694793500243.016454041732942.116489768
500025.567808986733056.298274085499718.977348328733193.601873383
499400.237836182733311.361678258498950.697116778733509.785144358
#Sta/Elev= 30
9213.142375.88989233.132364.34769244.717359.70329267.887 348.5139279.472347.9458
9291.057345.31069337.398330.26179395.323 316.2589418.494314.55579499.231305.2107
9522.004 298.6439533.391293.52679544.777284.42039556.164273.40839578.937257.0668
9601.709237.74439613.096 224.40910382.48 224.40910409.45226.824510536.27231.2576
10602.09239.896710613.06242.267910645.97244.356610700.82251.370110755.67 256.583
10777.61 259.98610799.55262.024810821.49266.297510865.26270.765910891.57275.3339
#Mann= 3 , 0 , 0
9213.142  0.0145       09213.142  0.0145       010891.57  0.0145       0
#XS Ineff= 2 , 0
       0                10432.75       0
Bank Sta=9213.142,10891.57
Exp/Cntr=0.3,0.1

Type RM Length L Ch R = 1 , 49944.3,246.406800,246.406800,246.406800
XS GIS Cut Line= 6
500325.719504697732486.706084966499829.544818521732850.626026228
499512.204274744733057.825314298499219.167320311733265.388245851
    499117.37331733333.945415139498943.413540602733439.351025745
#Sta/Elev= 30
9231.934340.76999245.033336.39759257.252330.62299269.472327.42169315.941311.5095
9366.211298.82829405.649291.70799418.111 285.5329443.037277.00069455.499270.7619
9467.962 267.2979500.263265.6179 9517.02261.90589542.737252.47019567.662245.7894
9580.124239.99889592.587226.80769600.803 224.409 10382.2224.574510394.45 226.856
10429.04230.738110504.74235.588210578.27243.525510602.63 245.11610650.73250.6068
10698.95260.219410710.94261.421910793.32275.622110863.77285.300110911.58293.1687
#Mann= 3 , 0 , 0
9231.934  0.0164       09231.934  0.0164       010911.58  0.0164       0
#XS Ineff= 2 , 0
       0                10472.01       0
Bank Sta=9231.934,10911.58
Exp/Cntr=0.3,0.1

Type RM Length L Ch R = 1 , 49697.9,246.406800,246.406800,246.406800
XS GIS Cut Line= 6
500092.951517491 732090.66280844 499889.38548547732280.627623066
499740.500461847732449.204913676499332.890223682733045.865186825
499153.668630123733226.320055082498938.417150468733391.034604162
#Sta/Elev= 30
9103.894355.2606 9127.53347.4106 9154.07335.43629167.339333.96589193.998326.2739
9345.991291.0375 9360.48 289.8759388.354282.9035 9415.41277.77789455.993267.0871
9496.576261.81719510.104257.65689523.631256.13559549.885249.60689575.908248.1405
9588.919 244.158 9601.93238.48739614.768224.41219616.312 224.40910342.55224.4809
10401.77238.004710431.38243.4254 10495.4248.357310553.57256.668210570.12256.6334
10596.62263.470610648.49264.437310693.26267.560510775.56282.4863 10856.6294.1196
#Mann= 3 , 0 , 0
9103.894  0.0176       09103.894  0.0176       0 10856.6  0.0176       0
#XS Ineff= 2 , 0
       0                               0
Bank Sta=9103.894,10856.6
Exp/Cntr=0.3,0.1

Type RM Length L Ch R = 1 ,49451.49,246.406800,246.406800,246.406800
XS GIS Cut Line= 6
499888.241264109 731813.17842357499642.417079389732050.178840175
499482.443879992732264.553445488499148.677373797733013.122508898
499019.020954877733192.348457649498880.418074489733327.063669935
#Sta/Elev= 30
8933.064 295.3418951.799290.64638997.525282.20379042.962275.72369057.681272.5402
9086.735269.97929098.049269.88319111.836271.27329125.622270.82689139.768266.8873
9168.388265.74239186.222 263.1399226.418 255.8129240.904251.4747 9256.18249.5077
9307.379235.62039338.725230.0457 9359.13224.84539365.039 224.40910209.74 224.409
10264.36228.706110309.02237.4739 10354.6243.5789 10408.3242.135610462.71242.0413
10511.16243.132610562.71246.3418 10643.5255.466310719.35269.421410778.84273.2801
#Mann= 3 , 0 , 0
8933.064  0.0217       08933.064  0.0217       010778.84  0.0217       0
#XS Ineff= 2 , 0
       0 9710.42         10353.9       0
Bank Sta=8933.064,10778.84
Exp/Cntr=0.3,0.1

Type RM Length L Ch R = 1 ,49205.08,246.406800,246.406800,246.406800
XS GIS Cut Line= 6
499188.454558402732221.705535635499101.979711413732430.204449683
498989.680279046732851.347773477498913.872510552 733026.69430998
498800.507992387733195.661777645498609.407980591 733377.91741775
#Sta/Elev= 30
 9586.78331.16189612.924320.21989634.937308.99189664.695290.75669722.377252.2318
9733.101249.53389765.059233.11239786.184224.41499796.746 224.40910437.51 224.409
 10449.6226.946610461.08227.531210472.56229.682610484.04 234.01710495.83235.2373
10507.62229.0373 10531.2231.053510555.52230.6899 10652.2234.967710667.37231.8391
10682.86230.668910697.71233.875910752.72239.003710766.17245.312310779.63249.5744
10806.54252.326510833.45264.015510846.91267.725910874.01272.094810908.26274.2117
#Mann= 3 , 0 , 0
 9586.78  0.0203       0 9586.78  0.0203       010908.26  0.0203       0
#XS Ineff= 2 , 0
       09795.358        10351.76       0
Bank Sta=9586.78,10908.26
Exp/Cntr=0.3,0.1

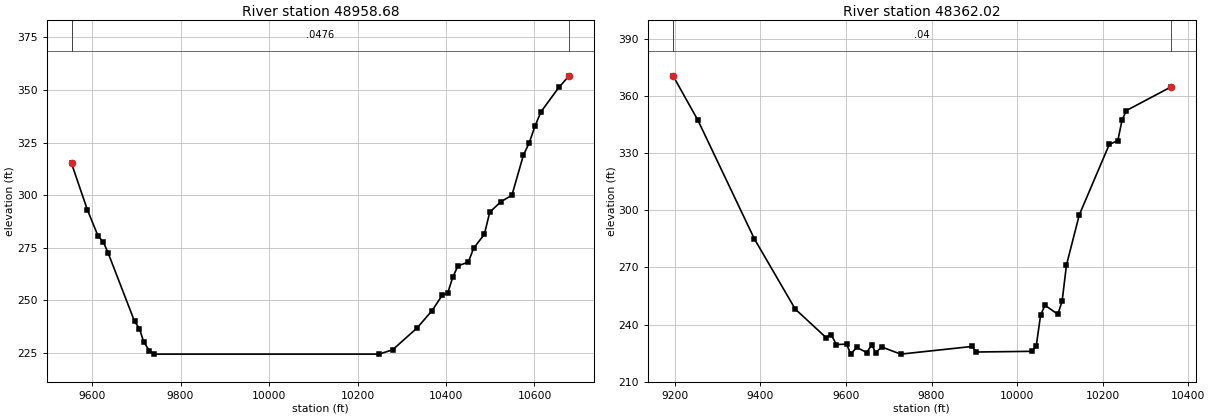
Type RM Length L Ch R = 1 ,48958.68,596.651200,596.651200,596.651200
XS GIS Cut Line= 6
498992.635524353732156.451957172498892.750308633732317.665860727
498762.524092644732727.342874736498711.611737043732849.881416634
498615.388865232733012.432462841498497.185385883733151.290173933
#Sta/Elev= 30
  9553.6315.04639589.375293.0216 9613.49280.57139625.483277.67239636.334272.4903
9695.932240.02429707.121236.49519716.365230.41139729.499225.99629740.688 224.409
10248.87 224.40910279.37226.476810334.88236.906910368.67245.143210391.94252.5732
10403.62253.3038 10415.3260.954710426.97266.364810450.34268.158310462.46274.7351
10486.68 281.38510498.89291.919210523.89296.830610549.01299.953910574.97319.0335
10587.96324.772910600.94332.694310614.51339.562910655.27351.263810678.26356.7096
#Mann= 3 , 0 , 0
  9553.6  0.0476       0  9553.6  0.0476       010678.26  0.0476       0
#XS Ineff= 2 , 0
       09843.326                       0
Bank Sta=9553.6,10678.26
Exp/Cntr=0.3,0.1

Type RM Length L Ch R = 1 ,48362.02,76.406100,76.406100,76.406100
XS GIS Cut Line= 6
499033.803088611 732026.46941569498684.342117548732257.038531944
498557.312109679732332.595413923 498275.39049378732327.400878295
498218.270363367732335.554897478497961.620279196732326.380691051
#Sta/Elev= 30
9195.848370.86869254.217347.36699385.778285.11449481.459248.10689553.359233.1561
9565.433 234.7189577.507229.43029601.656229.68249610.888224.43579625.395227.9285
9648.665225.2498  9660.3229.42919669.222225.14649683.571228.17169727.907 224.409
9894.659228.43949904.672225.520810034.76225.886910044.76228.6262 10054.9244.8974
10065.04250.133310095.32245.378110105.36252.421210115.37271.262810145.39297.6942
10215.43334.734810235.45336.798510245.45 347.66910255.46352.591610358.91364.9171
#Mann= 3 , 0 , 0
9195.848    0.04       09195.848    0.04       010358.91    0.04       0
#XS Ineff= 2 , 0
       09888.945                       0
Bank Sta=9195.848,10358.91
Exp/Cntr=0.3,0.1