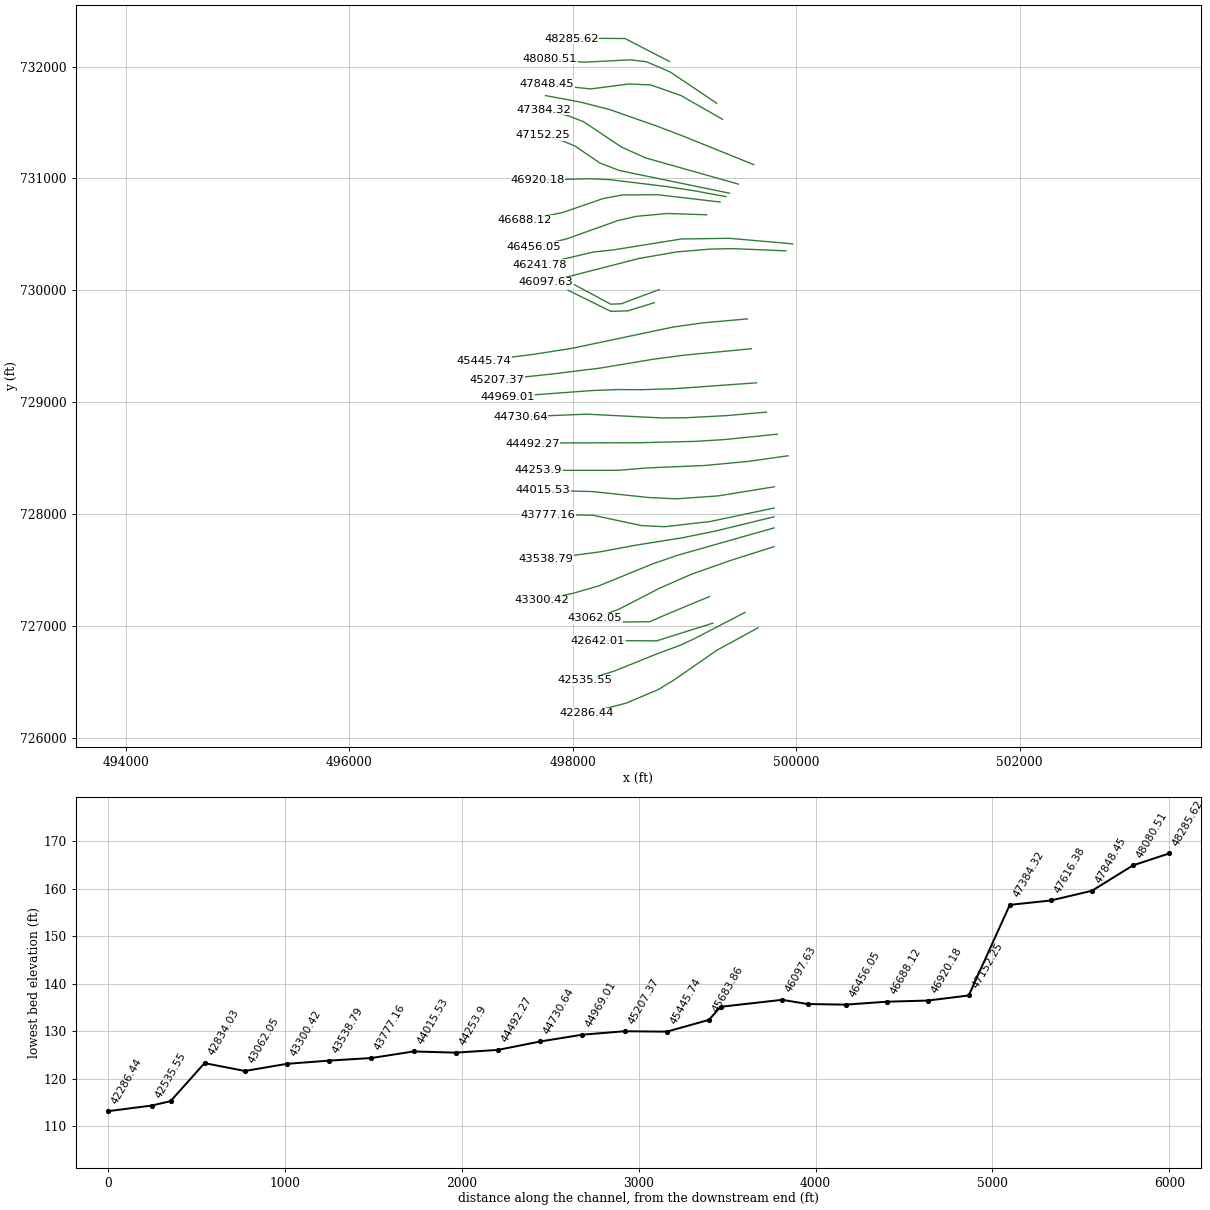
HEC-RAS study 978_ras.prj: 978

--- 978_ras.g01 (geometry) --- (continued)

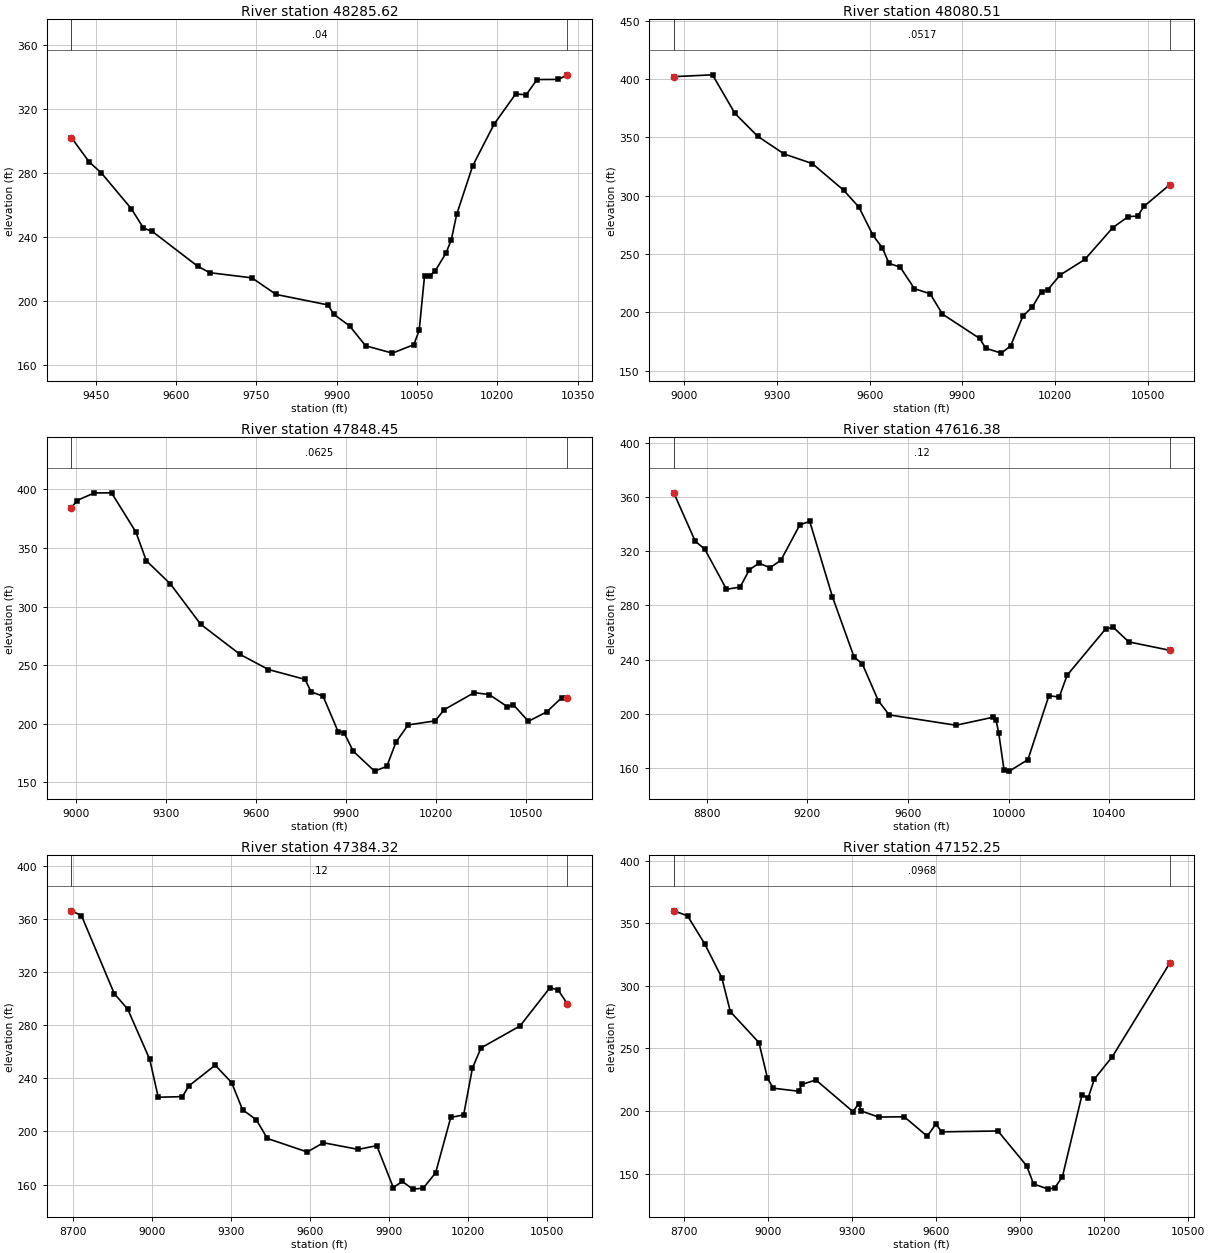
Type RM Length L Ch R = 1 ,48285.62,205.105300,205.105300,205.105300
XS GIS Cut Line= 4
498864.421123643732045.686284947498467.571338194732250.934939683
498196.481109629 732252.73620366497988.257451223732250.811662373
#Sta/Elev= 30
9404.913 302.1029438.037286.93979460.553280.15599516.845257.65769539.361245.5992
9555.795243.53329640.686221.73249663.202217.7243 9742.01 214.4749787.044204.1215
 9884.27197.53799894.271191.83289924.271184.44649954.272172.012410004.27167.4252
10044.27172.703910054.27181.670610064.27215.687410074.27215.696810084.27218.8966
10104.28229.960210114.28238.304810124.28254.158310154.28284.610210194.28310.6382
10234.28 329.38510254.28329.021310274.28338.472510314.28 338.57510331.03341.4298
#Mann= 3 , 0 , 0
9404.913    0.04       09404.913    0.04       010331.03    0.04       0
#XS Ineff= 2 , 0
       09868.176                       0
Bank Sta=9404.913,10331.03
Exp/Cntr=0.3,0.1

Type RM Length L Ch R = 1 ,48080.51,232.065600,232.065600,232.065600
XS GIS Cut Line= 6
499287.965807766731672.248177364498872.014779747731951.666873395
498660.089065731 732042.86085695498515.526856154732060.322962999
498093.945539176732039.327568352497792.612859008732071.213930472
#Sta/Elev= 30
8966.549402.13789091.884403.70419164.297370.65259237.955350.98959323.467335.8037
9414.646327.54959516.076304.69829565.543290.1261 9611.14265.92949641.626255.0883
9662.571241.97439699.133238.62219745.154220.17839795.584215.90699835.645198.4062
 9955.78177.53699975.804169.096110025.87 164.90910055.96171.033310096.07196.7805
10126.16 204.42810156.23217.752110176.25219.268110216.28231.9169 10296.3245.3098
10386.53272.545810436.84282.108310467.09282.440710487.26290.804510570.63309.3493
#Mann= 3 , 0 , 0
8966.549  0.0517       08966.549  0.0517       010570.63  0.0517       0
#XS Ineff= 2 , 0
       0                               0
Bank Sta=8966.549,10570.63
Exp/Cntr=0.3,0.1

Type RM Length L Ch R = 1 ,47848.45,232.065500,232.065500,232.065500
XS GIS Cut Line= 6
499340.245324582731528.755805597498965.812072277731742.233979896
498698.142238349731835.994187802498504.150745839731844.764181554
 498159.21418801731800.482555345497766.391816154731841.467650292
#Sta/Elev= 30
8983.548384.0903 9001.23390.42299059.219396.93329117.209397.06259198.394363.6099
9233.188 339.152 9313.81319.23059414.654284.87839546.282259.12119640.733246.2555
 9762.87237.84539782.933 227.2219822.971 223.4999873.021193.26849893.055192.2621
9923.285176.58729994.547159.559510035.47163.597910066.16184.3273 10106.5198.9569
10196.85202.446910226.85211.991910326.96 226.53110377.13  224.9210437.51214.5607
10457.64216.162310507.96202.123510568.54210.047810619.04222.238610637.83221.5655
#Mann= 3 , 0 , 0
8983.548  0.0625       08983.548  0.0625       010637.83  0.0625       0
#XS Ineff= 2 , 0
       0                               0
Bank Sta=8983.548,10637.83
Exp/Cntr=0.3,0.1

Type RM Length L Ch R = 1 ,47616.38,232.065600,232.065600,232.065600
XS GIS Cut Line= 6
 499619.73222968731123.590604484498976.815211207731382.513145342
498751.423671067731468.303877339498330.337937772731615.477634087
498066.707863122731682.885893673497754.932026903 731741.05806832
#Sta/Elev= 30
8669.701363.22358755.013327.45088793.101321.54938879.169291.92918933.124293.5352
8970.267306.4567 9008.66 311.1739051.824307.87689094.988313.28789170.524339.5835
9209.759342.13059300.016286.33989386.145241.71859418.244236.98269482.238209.5448
9525.243199.08439790.907191.4321 9939.25197.40929949.846195.36919960.442185.6807
9981.634158.256610002.84 157.519 10076.5166.053210159.66213.248310200.93212.2901
10231.83228.3408 10385.2262.6624 10415.8263.746110476.88253.047510639.44246.8452
#Mann= 3 , 0 , 0
8669.701    0.12       08669.701    0.12       010639.44    0.12       0
#XS Ineff= 2 , 0
       0                               0
Bank Sta=8669.701,10639.44
Exp/Cntr=0.3,0.1

Type RM Length L Ch R = 1 ,47384.32,232.065500,232.065500,232.065500
XS GIS Cut Line= 6
499481.676777273730949.323885873498648.762776434731184.487734109
498435.411165267731280.601144493498094.520112485731507.948978305
497957.331056535 731560.53150171497740.567701545731615.199217603
#Sta/Elev= 30
8694.293366.00718732.342362.41398856.614303.7319 8907.76292.02598991.207254.2496
9023.586225.73829115.447226.18279139.413 234.2349239.733249.82929302.008236.7669
9343.525216.31039395.687208.79919437.486194.72039589.019184.54169650.123191.5183
9782.121186.49219852.794189.28489915.349157.80969949.886162.39599988.808 156.592
10028.96157.281810076.15168.9279 10133.5210.587910182.34212.438510215.64247.6868
10248.24262.8421 10396.3279.384510509.99308.206110540.79306.419410575.94296.0365
#Mann= 3 , 0 , 0
8694.293    0.12       08694.293    0.12       010575.94    0.12       0
#XS Ineff= 2 , 0
       0                               0
Bank Sta=8694.293,10575.94
Exp/Cntr=0.3,0.1

Type RM Length L Ch R = 1 ,47152.25,232.065600,232.065600,232.065600
XS GIS Cut Line= 6
499403.007188588730867.995327353498416.803242058731070.799804941
498239.848931998731139.231357127498019.768550336731289.374633133
497911.530138969731334.221107006497728.170529622731384.229328606
#Sta/Elev= 30
8662.073359.85328711.197355.8839 8772.43333.54168833.662306.47368864.278279.2732
8966.332254.59768996.942 226.1379017.288218.16799108.847215.7064 9119.02221.1277
9169.886224.71869302.137199.46679322.483205.67959332.656199.92919393.695195.0886
9485.553195.31959567.609179.77069598.451 189.5289619.185183.28039820.239183.9662
9922.912156.13379947.581141.64119999.812137.520210023.34138.522510050.63147.4518
10120.43 212.64610142.64 210.42510164.59225.397210229.25 243.45810433.81317.9283
#Mann= 3 , 0 , 0
8662.073  0.0968       08662.073  0.0968       010433.81  0.0968       0
#XS Ineff= 2 , 0
       0                               0
Bank Sta=8662.073,10433.81
Exp/Cntr=0.3,0.1

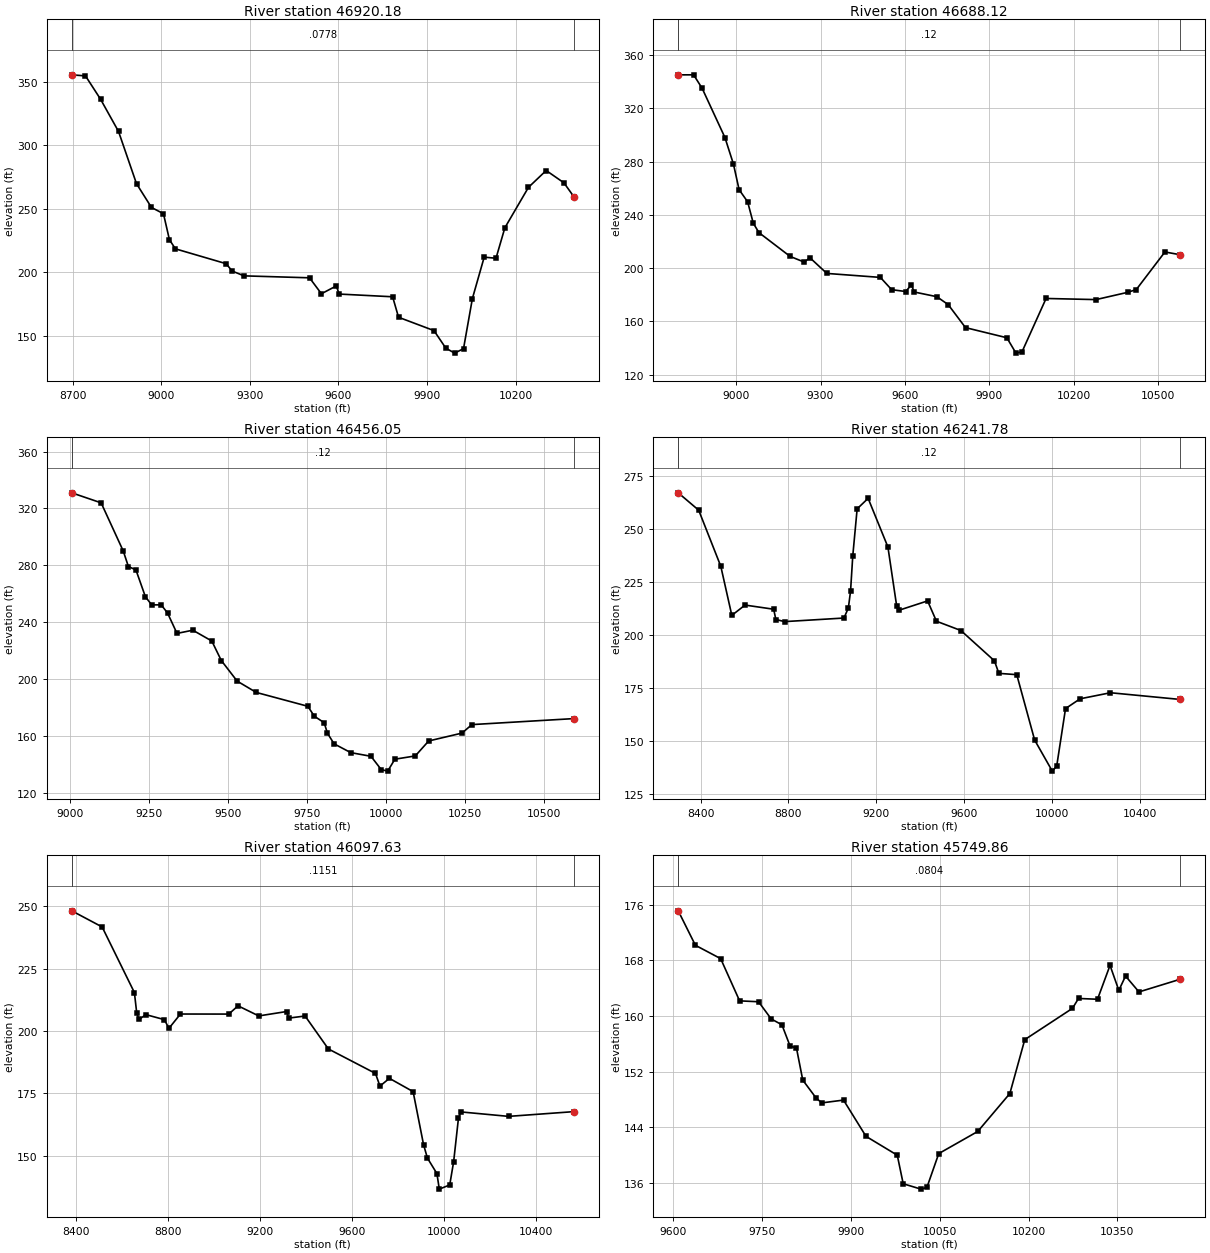
Type RM Length L Ch R = 1 ,46920.18,232.065500,232.065500,232.065500
XS GIS Cut Line= 6
499370.598991603730837.571305677499083.936426997 730890.22682409
498846.911420822730926.534445643498327.452223778730989.493982047
498151.633285075 730997.34010607497681.309501462730987.095201974
#Sta/Elev= 30
8696.611355.45058743.099354.59878794.068336.28648854.995310.88958915.922269.7824
8966.695251.06619007.241246.17139027.474225.70359047.707218.5215 9219.69206.8231
9239.887201.05779280.229 197.2579502.114195.71949542.388183.18099592.684189.2984
9602.743182.92859783.691180.79429803.736 164.6779923.843154.16539963.855140.3669
9993.864136.450210023.88139.963510053.89 179.35910093.91211.979610133.93211.1202
10163.94235.090310243.95266.923510303.96280.156510363.97270.489310397.66259.5675
#Mann= 3 , 0 , 0
8696.611  0.0778       08696.611  0.0778       010397.66  0.0778       0
#XS Ineff= 2 , 0
       0                               0
Bank Sta=8696.611,10397.66
Exp/Cntr=0.3,0.1

Type RM Length L Ch R = 1 ,46688.12,232.065600,232.065600,232.065600
XS GIS Cut Line= 6
499318.979777277730789.112451419498761.352171391730854.145755216
498448.670666963730852.808415413498275.650363356730821.782620594
497907.845581919730695.307056382497571.078056372730627.368730236
#Sta/Elev= 30
8794.541345.14848849.139345.16788879.483335.0375  8960.4298.1009 8990.65278.1456
9010.798258.92259041.019249.85479061.167233.73359081.315226.66759192.005208.8237
9242.206204.55029262.263207.83479322.434196.05079512.627193.06189552.636183.8454
9602.653182.45899622.701187.51279632.724 182.1049713.126178.57939753.607172.6136
9814.975155.3537 9961.87 147.752 9994.23136.206310015.78137.218410101.19 177.248
 10278.5176.398310391.15181.8589 10421.8183.977610523.37212.166610578.04210.0591
#Mann= 3 , 0 , 0
8794.541    0.12       08794.541    0.12       010578.04    0.12       0
#XS Ineff= 2 , 0
       0                               0
Bank Sta=8794.541,10578.04
Exp/Cntr=0.3,0.1

Type RM Length L Ch R = 1 ,46456.05,214.275900,214.275900,214.275900
XS GIS Cut Line= 6
499197.743143052730675.298468247498847.664241731730686.621415913
498569.049753368730661.412881136498397.081310987730621.406385839
497947.243007451730460.367063865497652.064621366730387.818995882
#Sta/Elev= 30
9005.784330.99779098.721323.96059168.792290.11019185.009279.25499208.832276.8895
9238.845258.02079258.845252.30819288.845252.34999308.845246.63579338.845 232.289
9388.882234.5462 9448.95226.96679479.024213.26389529.259198.80239589.713190.8471
9752.862181.12849773.557174.14439804.599169.59239814.982162.22129836.015154.7651
9888.677148.59569952.829146.00739985.235136.678110005.75135.5948 10028.4143.9702
10093.02146.260910135.47156.777810240.84162.296710272.25 168.26610594.89172.4752
#Mann= 3 , 0 , 0
9005.784    0.12       09005.784    0.12       010594.89    0.12       0
#XS Ineff= 2 , 0
       0                               0
Bank Sta=9005.784,10594.89
Exp/Cntr=0.3,0.1

Type RM Length L Ch R = 1 ,46241.78,144.147600,144.147600,144.147600
XS GIS Cut Line= 6
499967.573829087730415.301239523499401.807571511730464.786368303
498970.355707523730458.688834659498366.940405469730361.794141713
 498183.67790208730342.162605874497705.647146644730229.327526372
#Sta/Elev= 30
8298.115267.04958391.303258.85288491.963232.39418542.174209.21568602.429214.0822
8732.811212.11948742.837207.26448782.902206.27539053.054207.96529073.056212.7194
9083.058220.6712 9093.06237.19289113.063259.49759163.089264.44629253.217 241.487
9293.273213.5324  9303.3211.62799434.009216.04829474.284206.4561 9585.61 202.078
 9738.26187.7871 9758.64181.85499840.157181.23769921.553150.398310002.02135.7177
10022.07138.084310062.29 165.23310128.66 169.845 10266.9172.707910585.14169.5394
#Mann= 3 , 0 , 0
8298.115    0.12       08298.115    0.12       010585.14    0.12       0
#XS Ineff= 2 , 0
       0                               0
Bank Sta=8298.115,10585.14
Exp/Cntr=0.3,0.1

Type RM Length L Ch R = 1 ,46097.63,347.767100,347.767100,347.767100
XS GIS Cut Line= 6
499906.624119496730352.818203906499426.604658126730372.675356825
499229.004410084 730368.38969559498931.773609924730343.351094573
498593.918890451730285.005894912497759.281518111730070.682701293
#Sta/Elev= 30
8382.353248.18058514.269241.71668654.436215.41748664.442207.31388674.447 204.642
8704.463 206.5618784.489204.56158804.491201.06868854.494206.80749064.562206.7833
9104.649210.09799194.844206.04349315.422 207.8039325.478 205.1789396.031206.0096
9497.162192.80979701.876182.99349721.275177.90239762.345181.02339865.371175.6965
9910.743154.43959927.414149.07519968.778142.83179979.174136.603610024.47138.2861
10041.54147.649510062.32164.992510072.71167.5609 10280.1165.771610563.72167.6692
#Mann= 3 , 0 , 0
8382.353  0.1151       08382.353  0.1151       010563.72  0.1151       0
#XS Ineff= 2 , 0
       0                               0
Bank Sta=8382.353,10563.72
Exp/Cntr=0.3,0.1

Type RM Length L Ch R = 1 ,45749.86,66.006900,66.006900,66.006900
XS GIS Cut Line= 5
498772.183906521730005.985483481498510.431769769729908.763261258
498434.710615922729879.783560404 498338.42322276729876.044244164
497993.471299683730061.140398011
#Sta/Elev= 30
9608.055 175.0959637.054170.14729679.724168.22969711.726162.16789743.729162.0398
9765.064159.57579783.207158.72939797.067155.65779807.734155.41139818.402150.7935
9840.648 148.2529850.404147.5165 9887.28 147.9219925.218 142.7169978.075140.0059
9988.083135.906810018.11135.135410028.11135.376310048.13140.2375   10114143.4158
10168.26148.865510193.44 156.59910274.01 161.09210284.23162.512410316.31162.3974
10337.46167.263910352.32163.676410363.67165.729810386.36163.450610456.19165.2753
#Mann= 3 , 0 , 0
9608.055  0.0804       09608.055  0.0804       010456.19  0.0804       0
#XS Ineff= 2 , 0
       0 9878.28        10085.28       0
Bank Sta=9608.055,10456.19
Exp/Cntr=0.3,0.1

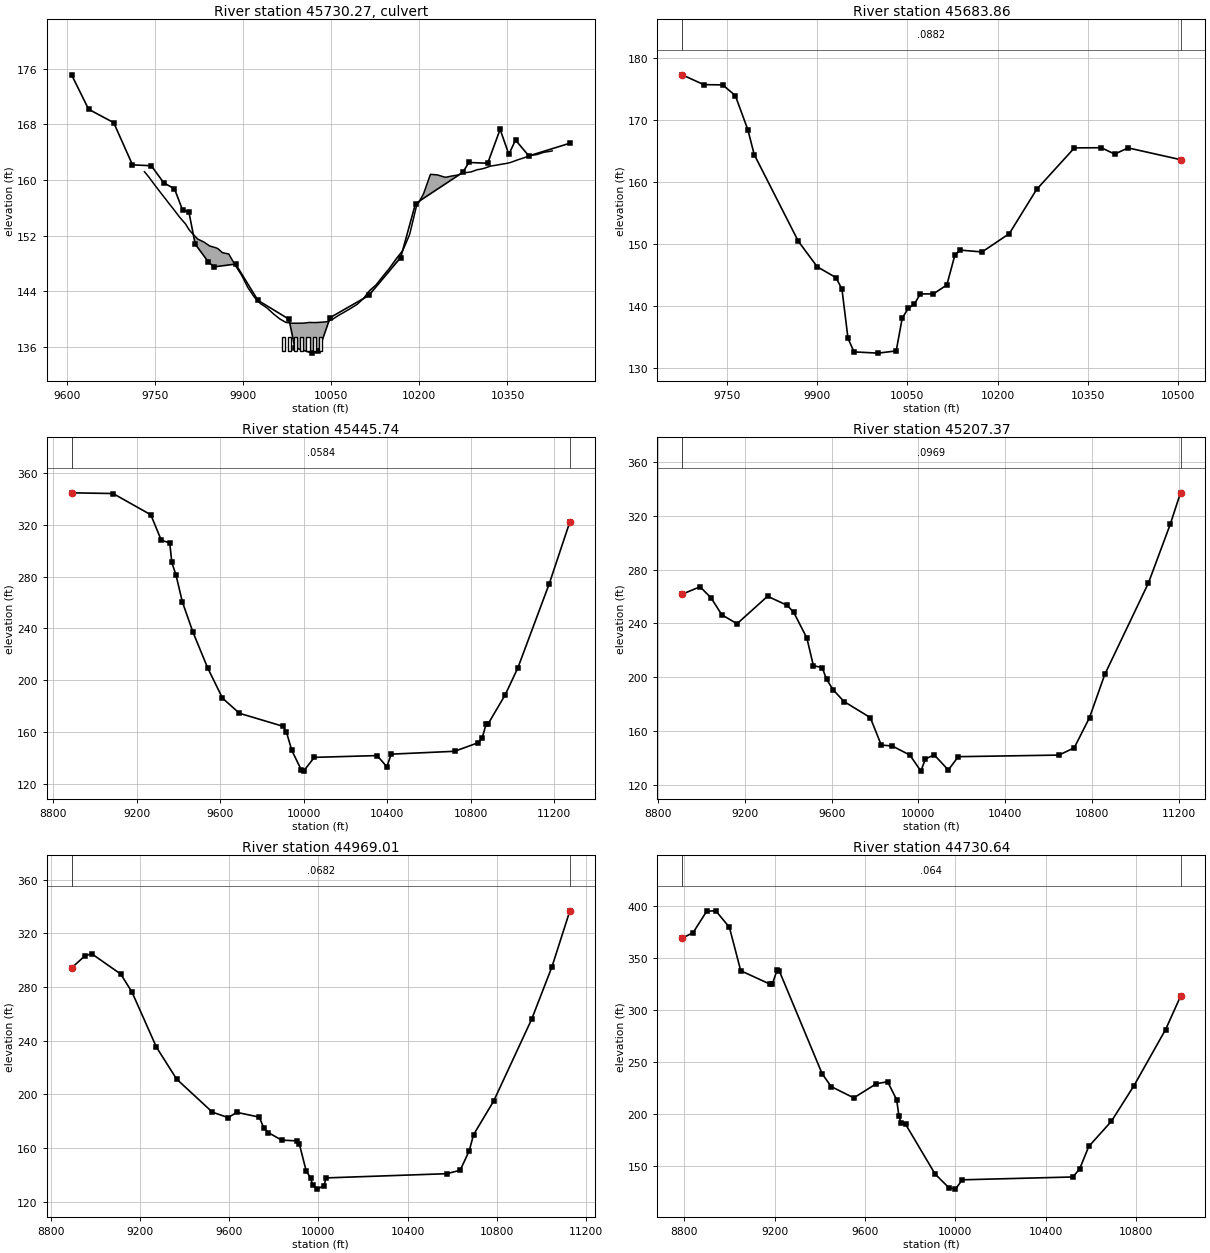
Type RM Length L Ch R = 2 ,45730.27,,,
Bridge Culvert--1,0,-1,-1, 0
Deck Dist Width WeirC Skew NumUp NumDn MinLoCord MaxHiCord MaxSubmerge Is_Ogee
14.503,37,2.6,0,96,96, , , 0.95, 0, 0,0,,
 9732.05 9736.97 9739.53 9749.94 9760.36 9770.77 9772.77 9781.19 9791.60 9802.02
 9808.57 9812.43 9822.84 9833.26 9843.67 9844.37 9854.09 9857.23 9864.79 9873.93
 9875.62 9886.45 9897.28 9900.00 9908.11 9918.93 9926.07 9929.76 9934.13 9940.69
 9950.71 9951.69 9962.69 9962.98 9972.72 9982.72 9992.7210002.7210012.7210022.72
10032.7210042.7210052.7210062.7210069.1010072.9710083.6510086.5110094.3210105.00
10115.0410115.6810126.3610137.0310143.5710143.6310148.1510159.9910162.2910171.82
10180.9910183.6610195.4910199.6910207.3310218.3910219.1610230.9910237.0910242.83
10245.7910254.2110257.5510265.4310276.6610279.5610287.8910299.1110301.5610310.34
10321.5710323.5610332.7910344.0210345.5710355.2410366.4710367.5710377.7010388.92
10389.5710400.1510411.3810411.5810422.6010426.10
  161.18  160.69  160.42  159.24  158.09  156.97  156.74  155.85  154.69  153.68
  152.79  152.42  151.51  151.09  150.49  150.49  150.25  150.13  149.56  149.40
  149.37  147.78  146.34  145.90  144.55  143.20  142.54  142.23  142.00  141.62
  140.85  140.77  140.03  140.02  139.55  139.43  139.43  139.44  139.54  139.52
  139.57  139.65  140.02  140.57  140.87  141.06  141.59  141.74  142.15  142.99
  144.09  144.15  144.94  146.08  146.76  146.77  147.22  148.61  148.87  149.88
  151.68  152.24  156.40  156.85  158.06  160.71  160.81  160.72  160.56  160.41
  160.40  160.55  160.60  160.71  161.06  161.06  161.15  161.49  161.50  161.67
  162.01  162.02  162.15  162.32  162.33  162.51  162.86  162.89  163.17  163.51
  163.52  163.65  163.96  163.97  164.11  164.18
                                                                                
                                                                                
                                                                                
                                                                                
                                                                                
                                                                                
                                                                                
                                                                                
                                                                                
                                                
 9732.05 9736.97 9739.53 9749.94 9760.36 9770.77 9772.77 9781.19 9791.60 9802.02
 9808.57 9812.43 9822.84 9833.26 9843.67 9844.37 9854.09 9857.23 9864.79 9873.93
 9875.62 9886.45 9897.28 9900.00 9908.11 9918.93 9926.07 9929.76 9934.13 9940.69
 9950.71 9951.69 9962.69 9962.98 9972.72 9982.72 9992.7210002.7210012.7210022.72
10032.7210042.7210052.7210062.7210069.1010072.9710083.6510086.5110094.3210105.00
10115.0410115.6810126.3610137.0310143.5710143.6310148.1510159.9910162.2910171.82
10180.9910183.6610195.4910199.6910207.3310218.3910219.1610230.9910237.0910242.83
10245.7910254.2110257.5510265.4310276.6610279.5610287.8910299.1110301.5610310.34
10321.5710323.5610332.7910344.0210345.5710355.2410366.4710367.5710377.7010388.92
10389.5710400.1510411.3810411.5810422.6010426.10
  161.18  160.69  160.42  159.24  158.09  156.97  156.74  155.85  154.69  153.68
  152.79  152.42  151.51  151.09  150.49  150.49  150.25  150.13  149.56  149.40
  149.37  147.78  146.34  145.90  144.55  143.20  142.54  142.23  142.00  141.62
  140.85  140.77  140.03  140.02  139.55  139.43  139.43  139.44  139.54  139.52
  139.57  139.65  140.02  140.57  140.87  141.06  141.59  141.74  142.15  142.99
  144.09  144.15  144.94  146.08  146.76  146.77  147.22  148.61  148.87  149.88
  151.68  152.24  156.40  156.85  158.06  160.71  160.81  160.72  160.56  160.41
  160.40  160.55  160.60  160.71  161.06  161.06  161.15  161.49  161.50  161.67
  162.01  162.02  162.15  162.32  162.33  162.51  162.86  162.89  163.17  163.51
  163.52  163.65  163.96  163.97  164.11  164.18
                                                                                
                                                                                
                                                                                
                                                                                
                                                                                
                                                                                
                                                                                
                                                                                
                                                                                
                                                
BR Coef=-1 , 0 , 0 ,, 0 ,,,0.8,-1,,0,
WSPro=,,,, 1 ,,,, 0 ,,,, 0 ,,,,-1 ,-1 ,-1 , 0 , 0 , 0 , 0 , 0
Multiple Barrel Culv=2,2,5.25,37,0.013,0.7,1,8,3,135.42,132.38,7,Culvert #1, 0, 14.503
 9968.50 9968.50 9979.00 9979.00 9989.50 9989.5010000.0010000.0010010.5010010.50
10021.0010021.0010031.5010031.50
Culvert Bottom n=0.013
BC Design=,, 0 ,, 0 ,,,,,,

Type RM Length L Ch R = 1 ,45683.86,238.112300,238.112300,238.112300
XS GIS Cut Line= 4
498729.181769769729889.332214622498493.604846692729816.415547956
 498340.29288088729811.741402657 497957.01296635730000.576872742
#Sta/Elev= 30
9676.262 177.2249712.044 175.6419743.448175.60599764.384173.8866 9785.32168.3572
9795.788 164.3819869.065150.39799900.469146.28839931.474144.55169941.479142.6955
9951.484134.75919961.488132.576110001.51 132.37710031.52132.734110041.53138.0098
10051.53139.594310061.53140.257910071.54141.9163 10093.3141.922910115.59 143.363
10128.88148.153810137.89148.977110174.13148.679610219.38151.644510264.64 158.756
 10327.4165.454310371.99165.473310394.29164.453310416.58165.447210503.52163.5562
#Mann= 3 , 0 , 0
9676.262  0.0882       09676.262  0.0882       010503.52  0.0882       0
#XS Ineff= 2 , 0
       0                               0
Bank Sta=9676.262,10503.52
Exp/Cntr=0.3,0.1

Type RM Length L Ch R = 1 ,45445.74,238.369300,238.369300,238.369300
XS GIS Cut Line= 6
499563.096193165729744.443806753499161.233041435729708.525131837
498895.840760887729670.865211502497992.229186237729481.262788266
497640.314410031729426.203357667497207.208985854  729372.0493169
#Sta/Elev= 30
 8888.32344.65779086.999344.1207 9267.94327.72569318.302308.0223 9358.64306.0579
9368.724290.96359388.893281.08049419.159260.51529469.733237.20949540.535 209.532
9611.516186.21039692.806174.5325 9900.97164.52929917.706160.14679943.514145.9522
9989.724130.621810000.01129.9056 10051.4 140.52810352.64141.904410399.29133.2407
10419.62143.002110723.71145.211210834.92 151.72210855.11155.140210875.28166.4593
10885.37166.638810966.05188.730911026.57209.4666 11177.7 274.68611276.15322.2889
#Mann= 3 , 0 , 0
 8888.32  0.0584       0 8888.32  0.0584       011276.15  0.0584       0
#XS Ineff= 2 , 0
       0                10232.49       0
Bank Sta=8888.32,11276.15
Exp/Cntr=0.3,0.1

Type RM Length L Ch R = 1 ,45207.37,238.369400,238.369400,238.369400
XS GIS Cut Line= 6
499596.949142754729477.110944971498993.732164621729419.759022772
498718.647654295729383.371024579498246.129942626 729304.72156547
497826.692151517729252.815886974 497317.90013047729198.917013785
#Sta/Elev= 30
8911.101261.7687  8993.3 267.2339043.452259.15259093.638246.39469163.922239.7225
9304.618260.19899395.127253.42749425.296248.16019485.635229.10169515.804208.4908
9556.114207.0972 9576.27198.45849606.504190.59829656.895181.82679778.054169.8417
9828.644149.39759879.279 148.703 9960.47141.962310011.34129.9897 10031.7138.9529
10072.35142.160510137.54130.8554 10183.8140.750510647.64141.9372 10718.1147.3391
10788.52169.834710858.94201.993511060.08270.072611160.59313.738711207.93337.2045
#Mann= 3 , 0 , 0
8911.101  0.0969       08911.101  0.0969       011207.93  0.0969       0
#XS Ineff= 2 , 0
       0                10365.38       0
Bank Sta=8911.101,11207.93
Exp/Cntr=0.3,0.1

Type RM Length L Ch R = 1 ,44969.01,238.369300,238.369300,238.369300
XS GIS Cut Line= 6
 499644.55882588729172.749042302498903.429740906729119.773770288
498612.946360052729111.226592153498411.989275366729112.726126269
498176.767388225729104.009304434497414.604568009729047.661355074
#Sta/Elev= 30
8893.534294.09098953.291303.1053 8983.39304.71219113.787289.54899163.921276.2416
9274.218234.9887 9364.46211.2812 9524.83186.63039594.944182.61299635.008186.4508
9735.089182.93759755.105174.94829775.121171.45429835.142165.78169905.152165.2198
9915.154162.65549945.157143.03919965.159137.4996 9975.16132.08159995.162129.2659
10025.17131.966710035.17 137.62810575.77140.761210635.93143.331410676.04157.6493
10696.09169.862510786.35194.9598 10956.9256.036611047.19294.805511127.84336.6597
#Mann= 3 , 0 , 0
8893.534  0.0682       08893.534  0.0682       011127.84  0.0682       0
#XS Ineff= 2 , 0
       0                10471.59       0
Bank Sta=8893.534,11127.84
Exp/Cntr=0.3,0.1

Type RM Length L Ch R = 1 ,44730.64,238.369300,238.369300,238.369300
XS GIS Cut Line= 6
499733.108973116728911.045772374499381.565944254728879.846514687
499009.444036454728860.280642763498799.107229978 728858.58178167
498126.481394738728892.446411505497529.106794483728868.568129056
#Sta/Elev= 30
8790.427 369.2428838.764374.55118899.048395.16788939.237395.51028999.467379.7105
9049.629 337.9139180.009324.92259190.031325.09469210.074338.22659220.095337.9467
9410.364238.82159450.402226.46899550.471215.60729650.484229.21719700.485231.1139
9740.495213.86559750.502198.21219760.509191.15029780.523 190.0689910.714142.3929
9970.909129.368510001.01127.834810031.12 136.79610521.62139.528410551.62147.4678
10591.64168.895710691.72193.051710791.82227.313710932.03281.350810998.03313.2132
#Mann= 3 , 0 , 0
8790.427   0.064       08790.427   0.064       010998.03   0.064       0
#XS Ineff= 2 , 0
       0                10576.31       0
Bank Sta=8790.427,10998.03
Exp/Cntr=0.3,0.1

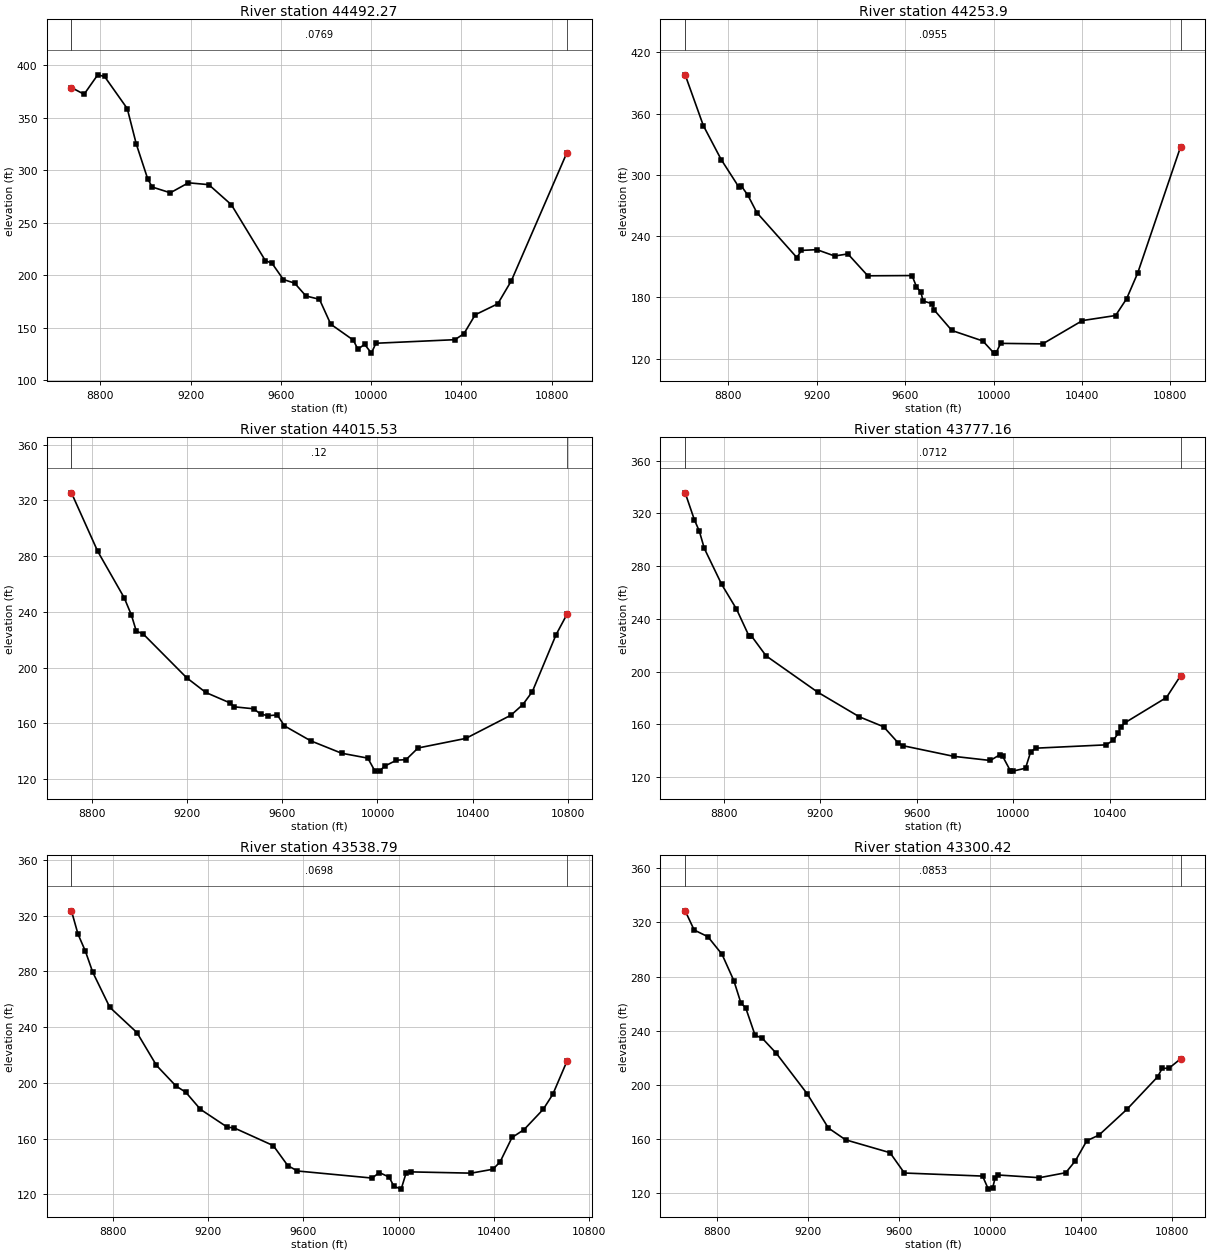
Type RM Length L Ch R = 1 ,44492.27,238.369300,238.369300,238.369300
XS GIS Cut Line= 6
499830.747187376728713.387923956499350.497976631 728664.63891767
499084.423767447728648.932767615 498566.60427615728636.685053438
497920.847446471728635.601018578497638.858442588728628.854774284
#Sta/Elev= 30
8672.394378.93388728.512372.58868788.911391.0977 8819.11389.51688919.666358.9679
8959.833325.06269010.041 292.1599030.124284.24549110.457278.75969190.721288.2689
 9280.92286.49629381.064267.35769531.166214.2549 9561.18 211.5679611.204196.1796
9661.227 192.7149711.238180.50069771.246177.32099821.254153.60929921.269138.4398
9941.271129.80489971.271  134.4210001.27 126.06210021.27 135.46810371.27138.8602
10411.27144.563410461.27162.581410561.27173.026410621.28194.9286 10867.5316.9387
#Mann= 3 , 0 , 0
8672.394  0.0769       08672.394  0.0769       0 10867.5  0.0769       0
#XS Ineff= 2 , 0
       0                               0
Bank Sta=8672.394,10867.5
Exp/Cntr=0.3,0.1

Type RM Length L Ch R = 1 , 44253.9,238.369300,238.369300,238.369300
XS GIS Cut Line= 6
499926.145176381728520.265165731499569.962030947728470.270013377
499179.260747761728433.480105817498664.053573191 728411.82564041
498408.587017357728390.882980525497690.636192201728389.880545269
#Sta/Elev= 30
8603.976397.90538686.052 348.2648766.892314.98288847.604287.81528857.692289.2024
8887.959279.96498928.315263.02279109.496219.01339129.592 226.0239199.926226.7782
9280.191220.57379340.358222.59899430.516201.18229630.693201.42169650.708190.4424
9670.722185.0969 9680.73176.52219720.759 173.9469730.766167.74779810.825 147.658
9951.089137.369510001.37125.488410011.42125.940810031.52135.044310221.78134.5323
 10401.8157.361410551.81162.299610601.81178.790510651.81203.868310846.18 327.635
#Mann= 3 , 0 , 0
8603.976  0.0955       08603.976  0.0955       010846.18  0.0955       0
#XS Ineff= 2 , 0
       0                               0
Bank Sta=8603.976,10846.18
Exp/Cntr=0.3,0.1

Type RM Length L Ch R = 1 ,44015.53,238.369300,238.369300,238.369300
XS GIS Cut Line= 6
 499803.53871549728243.395959824499301.076088607728161.768669784
498923.497507185728135.430118844498678.615775764728147.180472687
498171.527009606728200.925565541497729.568124712728210.194703028
#Sta/Elev= 30
8712.014325.43338822.456 283.4988934.057250.15068964.464237.69638984.735226.3403
9015.141223.95539197.008192.72539277.547182.17049378.031174.78129398.072171.8744
9478.238170.47219508.301166.71619538.322165.48049578.332166.07889608.338158.2154
9718.378147.53519848.738138.58979959.333135.06249989.495125.7349 10009.6125.8638
 10029.7129.259710080.04133.575110120.33 133.985 10170.7142.335810371.63149.2058
10561.81165.881210611.82 173.50610651.82182.801410751.82223.696910797.26238.1859
#Mann= 3 , 0 , 0
8712.014    0.12       08712.014    0.12       010797.26    0.12       0
#XS Ineff= 2 , 0
       0                               0
Bank Sta=8712.014,10797.26
Exp/Cntr=0.3,0.1

Type RM Length L Ch R = 1 ,43777.16,238.369400,238.369400,238.369400
XS GIS Cut Line= 6
499802.247383265728053.570123368499230.925852865727932.936866954
498821.318925798727886.271449968498612.852524608727896.603776857
498177.877994955727989.309522256497776.269765139727994.648670152
#Sta/Elev= 30
8639.593335.68338677.807315.16868698.327306.52538718.846293.49898790.663266.2208
8852.221247.43358903.416227.20918913.632227.12158974.927211.88129188.932184.3022
9361.194 165.6199461.982158.04499522.242145.82459542.322143.65159752.536135.5796
9903.975132.44739945.318136.97269955.675135.48569987.211124.62789997.722124.3563
10050.13126.5786 10070.9138.7535 10091.5141.776510384.08144.315210414.09147.8489
10434.09153.021210444.09158.0697 10464.1161.319210634.12180.263210692.88196.8784
#Mann= 3 , 0 , 0
8639.593  0.0712       08639.593  0.0712       010692.88  0.0712       0
#XS Ineff= 2 , 0
       0                               0
Bank Sta=8639.593,10692.88
Exp/Cntr=0.3,0.1

Type RM Length L Ch R = 1 ,43538.79,238.369300,238.369300,238.369300
XS GIS Cut Line= 6
499801.712456452727974.935882177499287.512661099 727849.97136502
498980.373804003727787.248873174498569.869703501727722.024523079
498246.992836863727662.163605601497756.154814363727596.326565459
#Sta/Elev= 30
8625.031 323.4738652.603306.75268683.569294.55858714.534 279.4298786.212254.2535
8900.004236.17658982.331212.59019064.442197.7633 9105.49193.33089167.021181.0765
9279.543168.30269310.172167.62219473.167 155.0349534.045140.7099 9574.63136.8246
9888.345131.74589918.914135.68729959.673132.49239980.052125.883710010.63123.8102
10031.03135.227810051.43136.178710304.75 135.27210395.65138.062410425.91143.2138
10476.36160.8591 10526.8166.487910607.48181.052810647.78191.828710707.05 215.493
#Mann= 3 , 0 , 0
8625.031  0.0698       08625.031  0.0698       010707.05  0.0698       0
#XS Ineff= 2 , 0
       0                10087.66       0
Bank Sta=8625.031,10707.05
Exp/Cntr=0.3,0.1

Type RM Length L Ch R = 1 ,43300.42,238.369300,238.369300,238.369300
XS GIS Cut Line= 6
499801.036955329727875.637217399498937.270403951727630.820191786
498715.870280802727554.449367225498231.898584634727357.175626025
498005.196833134727291.915209562 497725.41906938 727229.41860956
#Sta/Elev= 30
8662.131328.51528701.624314.34858761.853309.42728824.155296.41438876.074276.9607
8907.225260.40688927.993256.99478969.528236.63869000.679234.53799062.981223.3075
 9197.97193.60159291.424168.24819366.809159.55139562.327150.03249625.559135.0215
9969.309132.76749994.444123.134410013.21123.844110024.21 131.257 10035.2133.5889
10219.41131.564810334.78135.244610376.64 143.92710427.39158.844410480.68163.0031
10604.69182.204710738.05205.912710758.51212.201510789.21212.447110839.75219.2937
#Mann= 3 , 0 , 0
8662.131  0.0853       08662.131  0.0853       010839.75  0.0853       0
#XS Ineff= 2 , 0
       0                10289.76       0
Bank Sta=8662.131,10839.75
Exp/Cntr=0.3,0.1

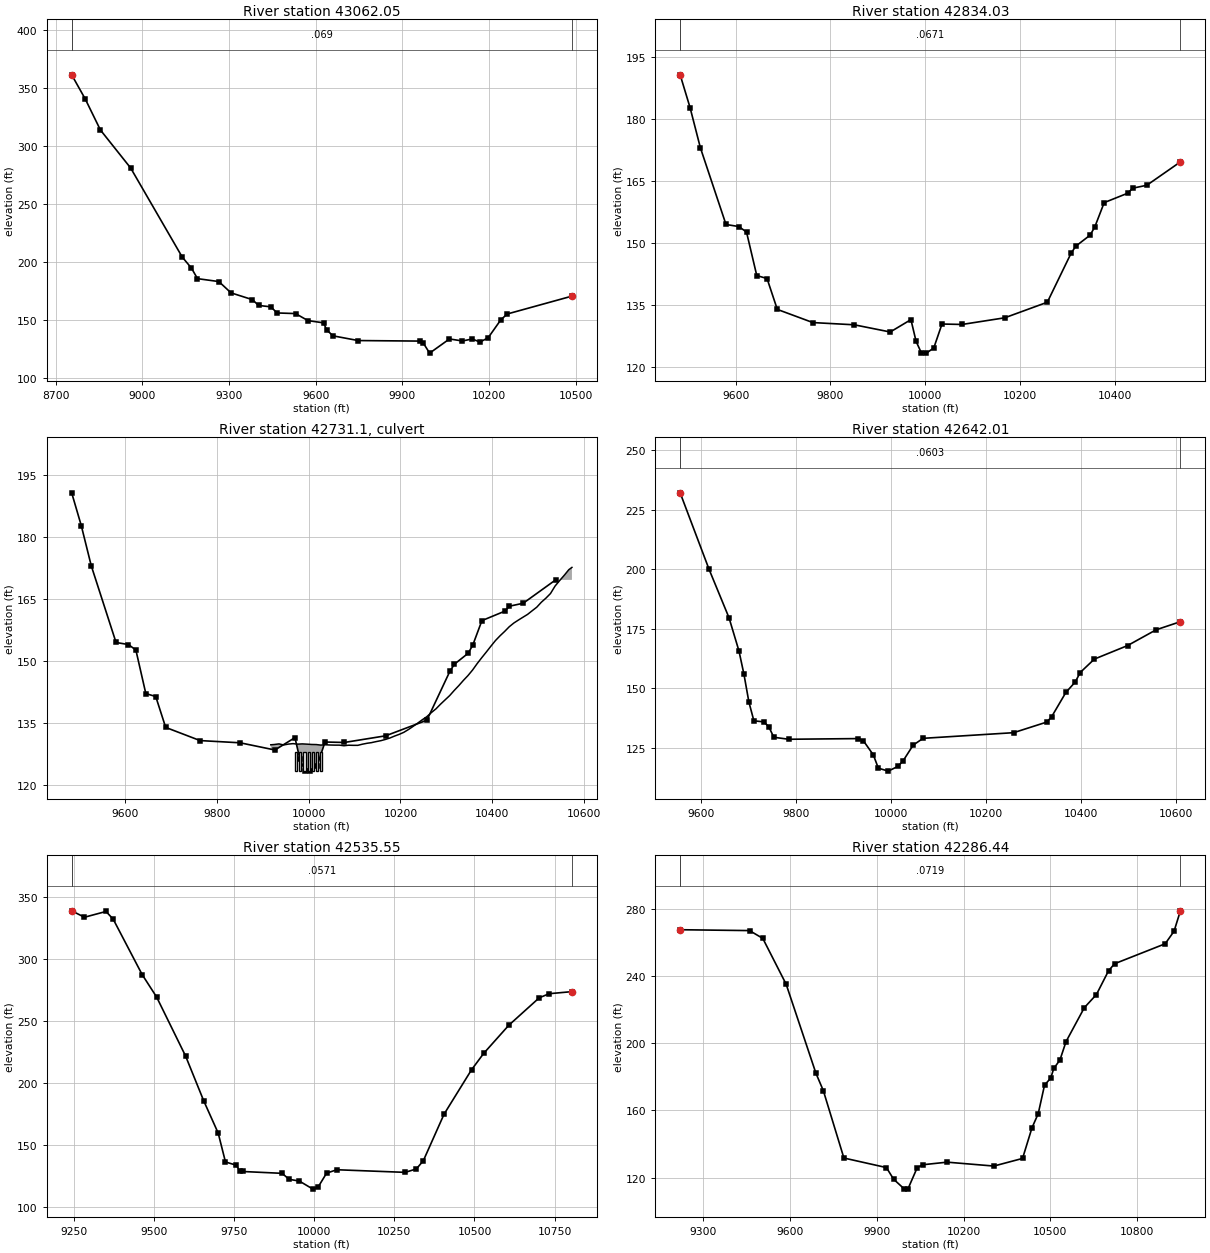
Type RM Length L Ch R = 1 ,43062.05,228.025400,228.025400,228.025400
XS GIS Cut Line= 6
499799.895111225727707.786134534499418.836571454727586.818851285
499067.184951368 727463.55547713498779.882758805 727337.88233864
498412.936371898 727149.37637757498195.546602254727066.148549211
#Sta/Elev= 30
8755.299361.31828802.341340.46738854.731 313.8248959.512281.04869138.114204.3177
 9169.71194.92249190.826185.77389264.731 183.2659306.963173.53239380.982167.6782
9402.283162.71059444.884161.49819466.184 156.2359530.114155.69969573.226149.6457
9627.116147.70849637.894141.69569659.603 136.532  9747.1132.45969960.124132.0025
9971.568130.64729994.458121.630510063.02133.836610108.05132.103810141.69133.8112
10168.71131.180510196.89134.833710240.68 150.25310262.75155.320810487.01170.7222
#Mann= 3 , 0 , 0
8755.299   0.069       08755.299   0.069       010487.01   0.069       0
#XS Ineff= 2 , 0
       0                               0
Bank Sta=8755.299,10487.01
Exp/Cntr=0.3,0.1

Type RM Length L Ch R = 1 ,42834.03,192.017700,192.017700,192.017700
XS GIS Cut Line= 4
499224.352068317727262.601240073498824.090437587 727096.09240169
498689.602529661727036.853680341498214.091712354727032.050540773
#Sta/Elev= 30
9482.738190.62799503.698182.6872 9525.36173.01419579.514154.41199606.671153.9085
9622.837152.57939644.498142.0462 9666.16141.33479687.821133.86099762.884130.6716
9850.283130.13449926.186128.39229969.894131.38599980.821 126.1129991.749123.3849
10002.68123.277910018.19124.544410035.46130.322110077.81130.216210167.82131.8252
10257.82135.595310307.82147.410210317.82149.153110347.83 151.80110357.83153.7503
10377.83159.699410427.83161.992210437.83163.189410467.83163.900610538.74169.5609
#Mann= 3 , 0 , 0
9482.738  0.0671       09482.738  0.0671       010538.74  0.0671       0
#XS Ineff= 2 , 0
       0                               0
Bank Sta=9482.738,10538.74
Exp/Cntr=0.3,0.1

Type RM Length L Ch R = 2 , 42731.1,,,
Bridge Culvert--1,0,-1,-1, 0
Deck Dist Width WeirC Skew NumUp NumDn MinLoCord MaxHiCord MaxSubmerge Is_Ogee
60.009,72,2.6,0,73,73, , , 0.95, 0, 0,0,,
 9917.14 9924.93 9935.09 9940.51 9945.26 9955.43 9965.59 9975.76 9976.11 9985.87
 9995.9710001.3510006.0710016.1710026.2710036.3710046.4710056.5810066.6810072.06
10076.7810086.8810096.9810107.0810117.1910127.2910137.3910139.8310147.4210157.42
10167.4310177.4410187.4410197.4510207.4610217.4610227.4710237.4810247.4810257.49
10267.5010273.0910277.5010287.5010297.5010307.5010317.5010327.5010337.5010347.50
10357.5010367.5010377.5010387.5010397.5010407.5010417.5010427.5010437.5010447.50
10457.5010467.5010477.5010487.5010497.5010507.5010517.5010527.5010537.5010547.50
10557.5010567.5010574.28
  129.65  129.72  129.87  129.73  129.61  129.82  129.93  129.81  129.81  129.87
  129.81  129.77  129.73  129.71  129.58  129.65  129.60  129.57  129.57  129.49
  129.42  129.55  129.52  129.52  129.80  130.02  130.18  130.25  130.43  130.65
  130.95  131.31  131.77  132.18  132.67  133.34  134.09  134.87  135.69  136.44
  137.44  137.95  138.34  139.47  140.52  141.56  142.81  143.98  145.24  146.41
  147.75  149.30  150.73  152.11  153.52  154.89  156.04  157.09  158.22  159.12
  159.84  160.53  161.21  162.09  162.95  164.15  165.14  166.26  168.07  169.40
  170.67  172.03  172.58
                                                                                
                                                                                
                                                                                
                                                                                
                                                                                
                                                                                
                                                                                
                        
 9917.14 9924.93 9935.09 9940.51 9945.26 9955.43 9965.59 9975.76 9976.11 9985.87
 9995.9710001.3510006.0710016.1710026.2710036.3710046.4710056.5810066.6810072.06
10076.7810086.8810096.9810107.0810117.1910127.2910137.3910139.8310147.4210157.42
10167.4310177.4410187.4410197.4510207.4610217.4610227.4710237.4810247.4810257.49
10267.5010273.0910277.5010287.5010297.5010307.5010317.5010327.5010337.5010347.50
10357.5010367.5010377.5010387.5010397.5010407.5010417.5010427.5010437.5010447.50
10457.5010467.5010477.5010487.5010497.5010507.5010517.5010527.5010537.5010547.50
10557.5010567.5010574.28
  129.65  129.72  129.87  129.73  129.61  129.82  129.93  129.81  129.81  129.87
  129.81  129.77  129.73  129.71  129.58  129.65  129.60  129.57  129.57  129.49
  129.42  129.55  129.52  129.52  129.80  130.02  130.18  130.25  130.43  130.65
  130.95  131.31  131.77  132.18  132.67  133.34  134.09  134.87  135.69  136.44
  137.44  137.95  138.34  139.47  140.52  141.56  142.81  143.98  145.24  146.41
  147.75  149.30  150.73  152.11  153.52  154.89  156.04  157.09  158.22  159.12
  159.84  160.53  161.21  162.09  162.95  164.15  165.14  166.26  168.07  169.40
  170.67  172.03  172.58
                                                                                
                                                                                
                                                                                
                                                                                
                                                                                
                                                                                
                                                                                
                        
BR Coef=-1 , 0 , 0 ,, 0 ,,,0.8,-1,,0,
WSPro=,,,, 1 ,,,, 0 ,,,, 0 ,,,,-1 ,-1 ,-1 , 0 , 0 , 0 , 0 , 0
Multiple Barrel Culv=2,4.6,4.6,72,0.013,0.7,1,8,3,123.28,115.5,7,Culvert #1, 0, 60.009
 9972.40 9972.40 9981.60 9981.60 9990.80 9990.8010000.0010000.0010009.2010009.20
10018.4010018.4010027.6010027.60
Culvert Bottom n=0.013
BC Design=,, 0 ,, 0 ,,,,,,

Type RM Length L Ch R = 1 ,42642.01,106.461900,106.461900,106.461900
XS GIS Cut Line= 3
 499253.17090573727024.045308158498750.442297532726865.541702389
498223.697991491726868.743795435
#Sta/Elev= 30
9555.161 232.0599616.155199.92089658.096179.64749679.066165.70979689.552155.9553
9700.037144.22859710.522136.37899731.493135.95459741.978133.87749752.463129.4833
9783.919 128.6489930.713  128.939941.198128.00679962.168122.08749972.654116.5252
9993.624115.274710014.59117.337110025.08119.660210046.05126.190510067.02129.0395
10257.73 131.40910327.73135.876210337.73138.089210367.73148.277310387.73152.7396
10397.73156.614110427.73162.283910497.74167.959210557.74174.566910609.04177.9822
#Mann= 3 , 0 , 0
9555.161  0.0603       09555.161  0.0603       010609.04  0.0603       0
#XS Ineff= 2 , 0
       0                               0
Bank Sta=9555.161,10609.04
Exp/Cntr=0.3,0.1

Type RM Length L Ch R = 1 ,42535.55,249.105100,249.105100,249.105100
XS GIS Cut Line= 6
499540.796510309727120.112233073499097.605841935726889.932067066
498968.682802022726829.115819082498759.724054873726752.099597782
498374.255974531726596.649706334 498106.89114362726512.365585446
#Sta/Elev= 30
 9243.27339.21199283.159334.02769350.433 338.697  9372.9332.4122 9463.06287.7435
9508.273269.56019598.697221.87389655.213185.70729700.425159.60649723.031136.3175
9756.741133.68749767.885129.0711 9776.52128.60359899.972127.11129921.471122.2842
 9953.61120.87629996.011114.353610011.42115.728910038.56127.254310070.47130.0172
10283.76127.902610318.67130.6827 10340.3137.252210405.08174.903810490.73210.7502
10528.71224.026810607.48246.871210702.09268.950110733.27 272.25910804.07273.9239
#Mann= 3 , 0 , 0
 9243.27  0.0571       0 9243.27  0.0571       010804.07  0.0571       0
#XS Ineff= 2 , 0
       0                               0
Bank Sta=9243.27,10804.07
Exp/Cntr=0.3,0.1

Type RM Length L Ch R = 1 ,42286.44,249.105000,249.105000,249.105000
XS GIS Cut Line= 6
499657.203864425726982.214290544499289.958889455726781.974247023
  498897.2010777726510.110133037498762.700509369726429.244229004
498475.592698544726308.585540786498123.436214745726217.311817586
#Sta/Elev= 30
9220.291267.41129460.025 266.8989505.912 262.2689586.694234.99879689.647182.0365
 9715.23171.70029786.285131.65089933.196125.97479958.176119.03619995.645113.1526
10008.16113.450410039.41125.808210058.03127.636110143.02129.188910304.52126.8717
10403.79131.409610436.34149.601310458.04 158.07910479.74 175.01610501.06179.1544
10511.68184.923310532.91189.909410554.15200.908110617.35221.065410659.15228.8794
10700.96242.985610721.68247.172610896.69 259.05310927.39266.512110949.37278.6496
#Mann= 3 , 0 , 0
9220.291  0.0719       09220.291  0.0719       010949.37  0.0719       0
#XS Ineff= 2 , 0
       0                               0
Bank Sta=9220.291,10949.37
Exp/Cntr=0.3,0.1