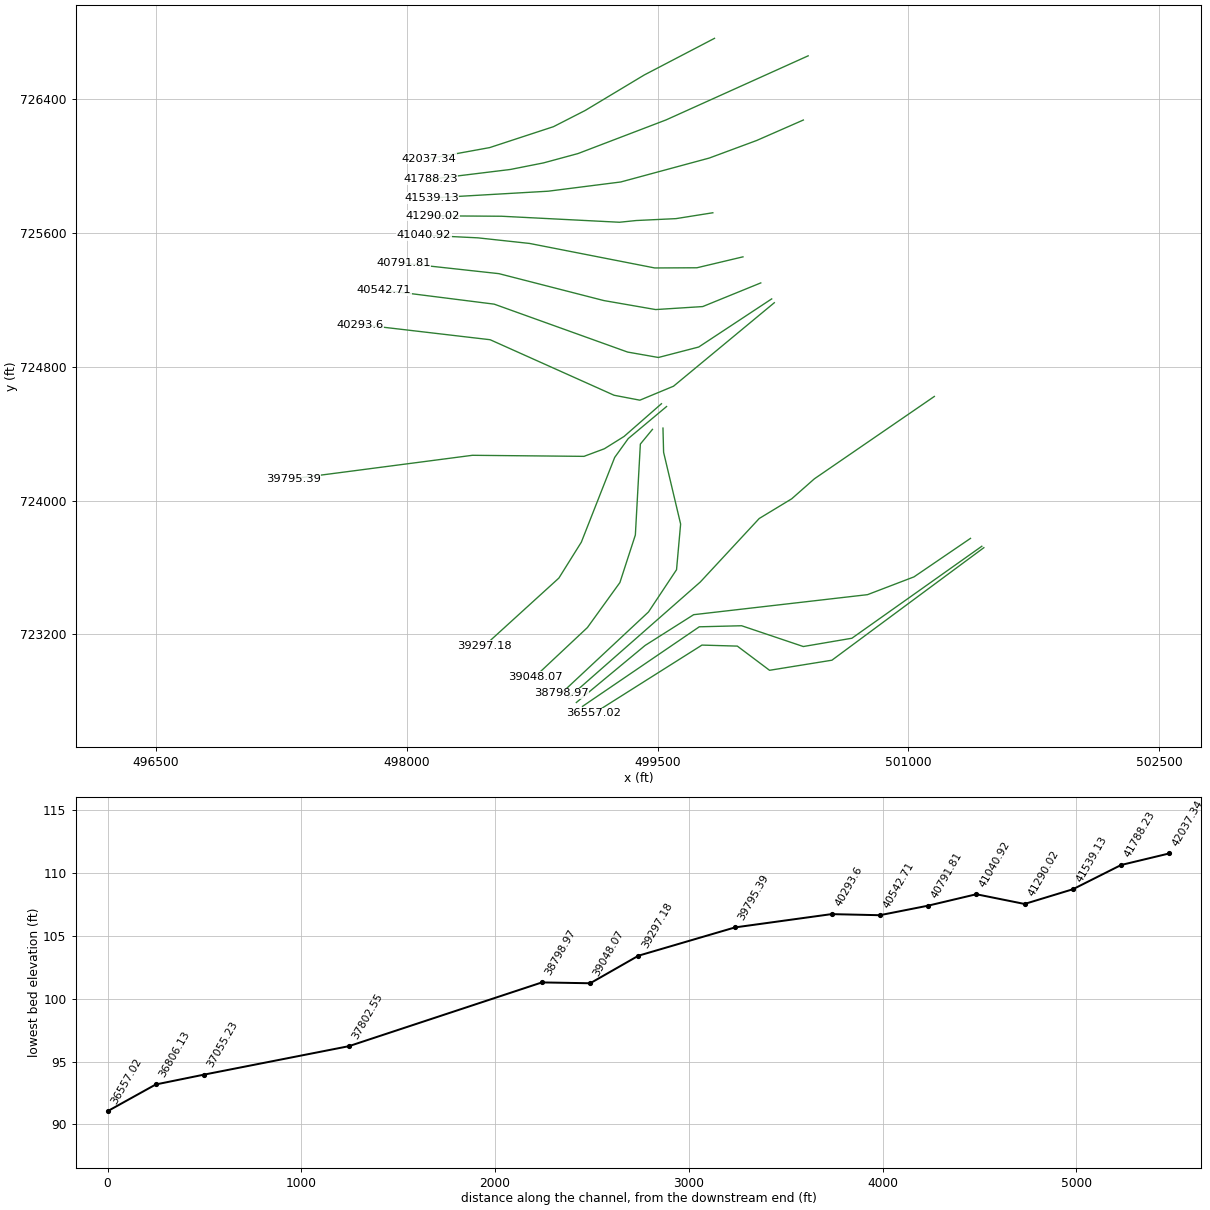
HEC-RAS study 978_ras.prj: 978

--- 978_ras.g01 (geometry) --- (continued)

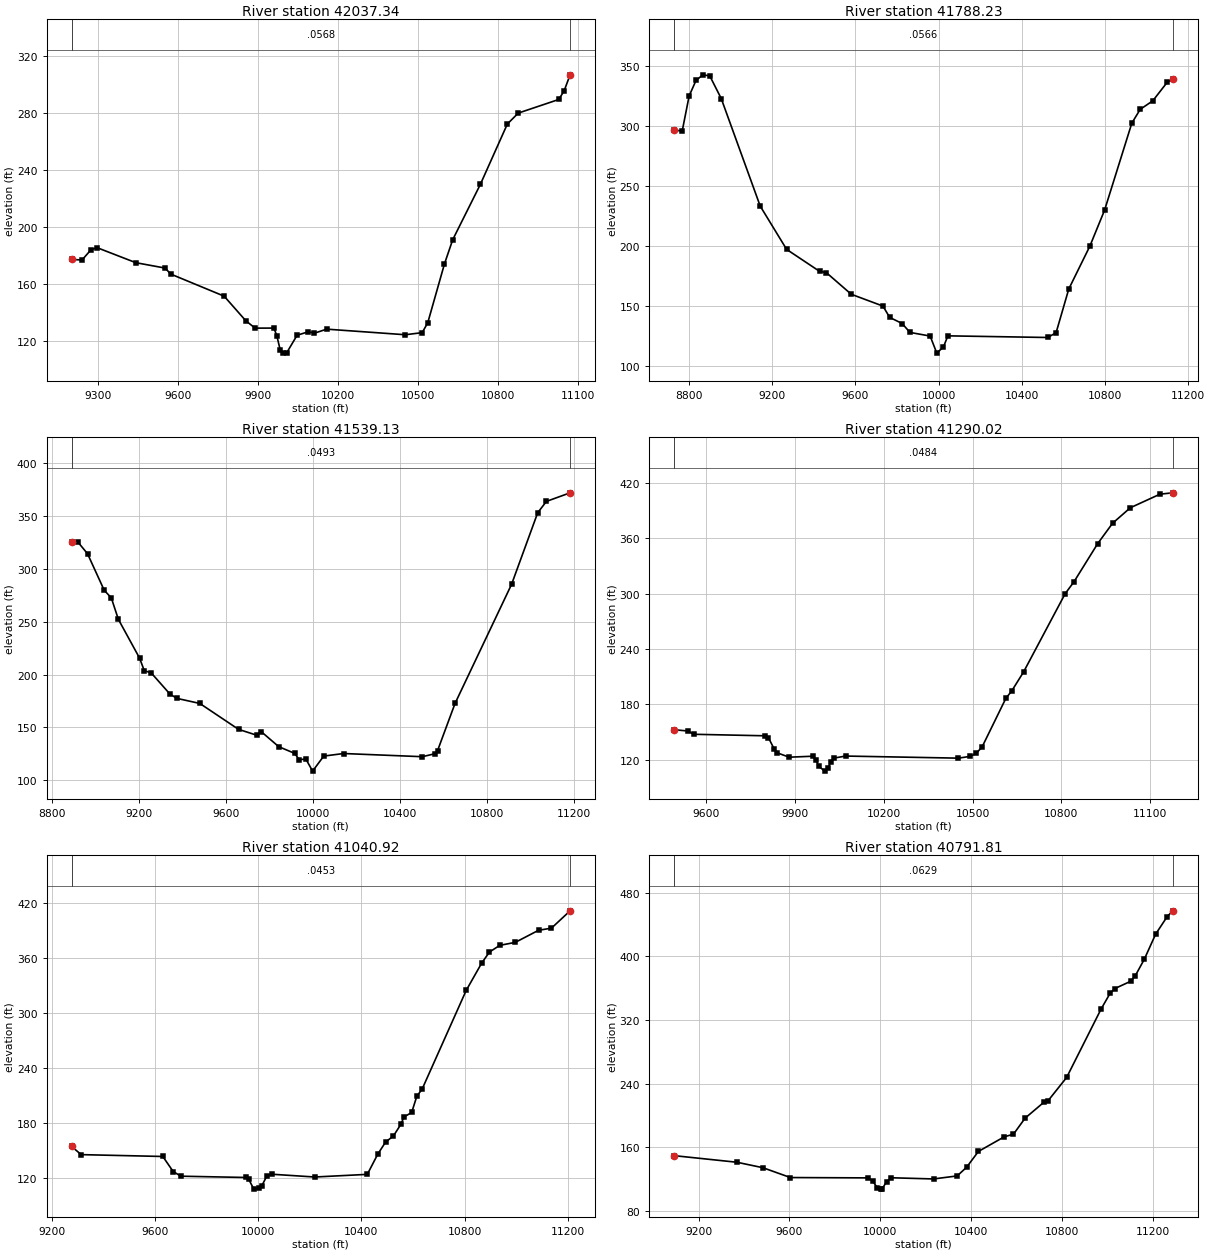
Type RM Length L Ch R = 1 ,42037.34,249.105100,249.105100,249.105100
XS GIS Cut Line= 6
499840.161062181726765.480379313499420.029392689726546.324785262
 499066.45656544726333.835919365 498876.82442224726236.997573808
498495.187373698726111.857869208498133.045900792726045.939082265
#Sta/Elev= 30
9201.391177.25089240.594176.92369274.043184.03129296.342185.58769442.483174.9974
9552.348171.22469573.304167.02099773.628151.51999854.572134.32929889.761129.1006
9960.382 129.1419971.144123.81649983.922113.80719995.692111.570510008.88111.9996
10047.26124.115810089.53126.547510112.45125.573510158.21128.387810453.26124.4673
10516.48125.938410537.41132.877810599.99174.100510630.97 191.10810734.54229.8665
10836.04272.297410876.76279.919611028.88289.491411049.09295.596211071.28306.7715
#Mann= 3 , 0 , 0
9201.391  0.0568       09201.391  0.0568       011071.28  0.0568       0
#XS Ineff= 2 , 0
       0                               0
Bank Sta=9201.391,11071.28
Exp/Cntr=0.3,0.1

Type RM Length L Ch R = 1 ,41788.23,249.105100,249.105100,249.105100
XS GIS Cut Line= 6
500400.449183851726660.839227721499550.751030624726277.582646012
499023.577065825 726076.15887855 498817.29271999726020.287262455
498618.435464293725980.931567073498139.976004106725922.352239794
#Sta/Elev= 30
8729.572296.55748768.632296.20598801.689325.28638834.746338.27198867.802342.9152
8900.859 342.0238955.953323.11249143.273233.32679270.219197.2221 9428.23178.9316
9460.928 177.8519580.824159.76759732.935149.91389765.413140.47429825.095135.3737
9862.848127.92329959.694124.9032 9991.83110.6483 10023.8115.870510045.07125.0718
10524.23123.693210564.95127.646210625.96164.191110727.21199.915710797.92229.9538
10928.87302.584810969.16 314.10611029.51321.199611099.81 336.88611124.95 339.445
#Mann= 3 , 0 , 0
8729.572  0.0566       08729.572  0.0566       011124.95  0.0566       0
#XS Ineff= 2 , 0
       0                               0
Bank Sta=8729.572,11124.95
Exp/Cntr=0.3,0.1

Type RM Length L Ch R = 1 ,41539.13,249.105000,249.105000,249.105000
XS GIS Cut Line= 6
500371.751229554726276.836054444500092.611934692726154.467717275
499808.939325929726049.334169835499279.404549181725906.209519163
498845.099187791725850.978598773498146.243905257725810.574669234
#Sta/Elev= 30
8889.511325.27618918.895325.1596 8962.83314.22079039.611279.67869072.207272.5301
9104.802252.16979202.473215.5193  9223.9203.7301 9256.04201.53439341.748181.6584
9373.888177.49359479.505172.70229657.685148.22139740.807142.71719761.588146.1612
9842.868131.83619916.214125.4999 9936.83119.55259967.755120.12659998.679 108.717
10050.07122.944210141.63125.359710503.82122.347510563.97125.280710573.99128.1801
10654.19172.6829 10914.6285.365911034.76352.990111074.81 363.68411183.72371.7812
#Mann= 3 , 0 , 0
8889.511  0.0493       08889.511  0.0493       011183.72  0.0493       0
#XS Ineff= 2 , 0
       0                               0
Bank Sta=8889.511,11183.72
Exp/Cntr=0.3,0.1

Type RM Length L Ch R = 1 ,41290.02,249.105100,249.105100,249.105100
XS GIS Cut Line= 6
 499830.16999951 725722.01391916499609.643301159 725686.93774493
499371.521906286725675.548588961499271.600909889725665.233233616
498566.426819682725701.190172136498152.235526472725703.724090934
#Sta/Elev= 30
9492.574152.46439538.637151.0914 9558.96147.51359800.863145.86949810.873143.8369
9830.885131.19049840.891127.34899880.916122.66369961.002 123.7199971.066 119.667
 9981.13 112.65610001.27107.546310011.36110.480810021.45117.745610031.49121.6568
10071.54123.901410452.25 121.62110492.32123.560110512.35126.808210532.39 133.928
10612.44186.514310632.45194.658810672.48215.288310812.55300.010610842.55313.0551
10922.56354.434410972.56376.410211032.56393.257111132.57407.975811175.34409.4472
#Mann= 3 , 0 , 0
9492.574  0.0484       09492.574  0.0484       011175.34  0.0484       0
#XS Ineff= 2 , 0
       0                               0
Bank Sta=9492.574,11175.34
Exp/Cntr=0.3,0.1

Type RM Length L Ch R = 1 ,41040.92,249.105000,249.105000,249.105000
XS GIS Cut Line= 6
500010.417051435725458.284022152499734.836224854725392.926760152
499482.461275369725391.849510327498733.774024665725538.464479789
498425.044025779725571.931212828498102.778153896725587.718893141
#Sta/Elev= 30
9276.181154.71759313.524145.8435 9630.04143.83239670.062127.47769700.063122.3851
9952.127120.99499962.384119.39499982.899108.319610003.43109.294410013.72111.8664
10034.29123.078410054.86124.486710219.12121.4972   10423124.378910463.56146.3654
10493.93159.5093 10524.3166.153810553.84179.098910564.79186.729210595.07191.6929
10615.22209.530310635.37216.971210806.45324.439310866.69354.252310896.79366.2509
10936.87373.498310996.99376.747711087.11389.884511137.14392.200811209.41411.0465
#Mann= 3 , 0 , 0
9276.181  0.0453       09276.181  0.0453       011209.41  0.0453       0
#XS Ineff= 2 , 0
       0                               0
Bank Sta=9276.181,11209.41
Exp/Cntr=0.3,0.1

Type RM Length L Ch R = 1 ,40791.81,249.105100,249.105100,249.105100
XS GIS Cut Line= 6
500117.000278115725302.335932583499769.679078192  725160.8496252
499488.006267548725142.881538168499177.809559464725196.839790642
498550.581030458725357.709319755497980.442010373725420.234887138
#Sta/Elev= 30
9091.676149.49289368.404141.18539482.738134.33579604.053121.95899946.373121.5341
9966.734117.49529987.154108.9189   10001107.409510007.61107.420510028.12116.9691
10048.63121.688910234.83   120.210338.71124.010610380.26134.8687 10432.2154.7524
10545.71 173.10510586.87176.465710638.04196.613110719.68216.328810739.96218.7285
10821.09247.777110972.47333.528711012.71353.602811032.79359.412211103.07368.6408
11123.15  375.39 11163.3396.3498 11213.4427.981811263.48 449.62711288.05457.1991
#Mann= 3 , 0 , 0
9091.676  0.0629       09091.676  0.0629       011288.05  0.0629       0
#XS Ineff= 2 , 0
       0                               0
Bank Sta=9091.676,11288.05
Exp/Cntr=0.3,0.1

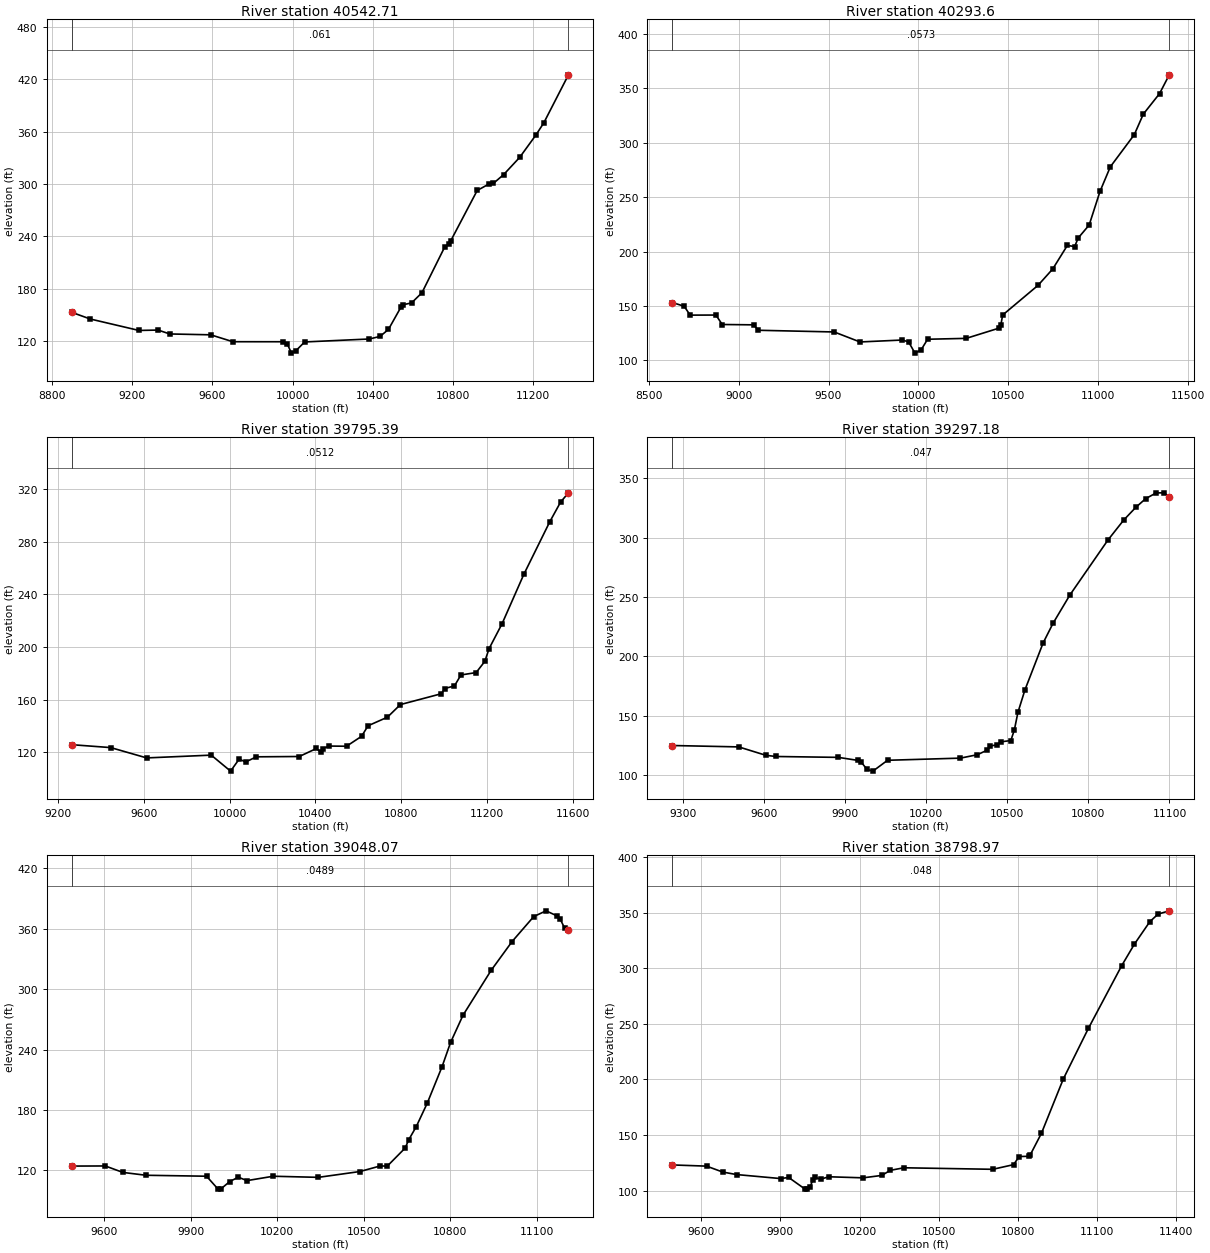
Type RM Length L Ch R = 1 ,40542.71,249.105100,249.105100,249.105100
XS GIS Cut Line= 6
500182.307162046725206.781649753499745.677395612724918.847011134
499504.561548769724856.257401183499320.197328895724888.696510255
498522.438329279725175.267749637497862.449443787725258.697444767
#Sta/Elev= 30
8897.936153.37788991.898145.62969234.286132.57779329.794133.01569387.773128.5679
9592.073127.5852 9702.54119.69679951.157119.66589972.769117.61599994.754106.6506
10017.03109.449910060.47119.424510383.37122.816310436.31125.762810478.17 133.727
10541.24159.484910551.67161.968510593.41164.057810645.12175.606210758.23227.7323
10778.64231.084510788.81235.007910920.92292.633310981.54300.245311001.74300.7832
11052.21310.6423 11132.6330.4163   11213355.800411253.07369.972611375.82424.8112
#Mann= 3 , 0 , 0
8897.936   0.061       08897.936   0.061       011375.82   0.061       0
#XS Ineff= 2 , 0
       0                               0
Bank Sta=8897.936,11375.82
Exp/Cntr=0.3,0.1

Type RM Length L Ch R = 1 , 40293.6,498.210100,498.210100,498.210100
XS GIS Cut Line= 6
500197.985407948725183.841900513499595.042257547 724684.44165577
499393.648297966724600.820299312499239.479573816724630.288799405
498498.113565981  724962.4563317497720.810931355725053.467895687
#Sta/Elev= 30
8631.284153.21278697.119149.79038730.427141.63558873.711141.70938908.689133.0261
9083.241 132.7159110.016127.72119531.393126.1709 9674.86116.99789910.482118.7675
9945.108117.06489980.456106.737110014.44 109.66310050.84119.485210265.41 120.286
10447.18 129.659 10457.7132.353410468.23141.7247 10664.9168.999110746.71184.0426
10827.88205.636910868.37204.602510888.62212.561510949.14224.361711009.52255.2677
11066.97277.865311200.21 307.38111250.34326.232711340.41345.015111394.62362.3106
#Mann= 3 , 0 , 0
8631.284  0.0573       08631.284  0.0573       011394.62  0.0573       0
#XS Ineff= 2 , 0
       0                               0
Bank Sta=8631.284,11394.62
Exp/Cntr=0.3,0.1

Type RM Length L Ch R = 1 ,39795.39,498.210100,498.210100,498.210100
XS GIS Cut Line= 6
499522.731864125724579.538184509499299.190473795724383.865521953
499181.246045411724310.171822041499059.236972749724264.738189533
498391.872858286724271.076163024497318.955688894724130.793219328
#Sta/Elev= 30
9262.636125.78619445.661123.56159613.248115.72159914.405117.835610004.65105.6794
 10044.8114.824610074.92112.629910125.11116.554310325.21116.794410405.25122.8851
10425.28120.0487 10435.3122.872510465.35124.739410545.56124.592410615.85132.1693
10646.01140.152510736.48146.690910796.92 156.26510988.46164.531511003.51 168.443
11049.08170.475111079.38178.7767 11150.1180.576711190.51189.041511210.72198.8333
11271.35217.779111372.47255.171111493.82295.245711544.39310.221811580.84317.2048
#Mann= 3 , 0 , 0
9262.636  0.0512       09262.636  0.0512       011580.84  0.0512       0
#XS Ineff= 2 , 0
       0                               0
Bank Sta=9262.636,11580.84
Exp/Cntr=0.3,0.1

Type RM Length L Ch R = 1 ,39297.18,249.105100,249.105100,249.105100
XS GIS Cut Line= 6
499553.398697853724562.813131213499323.996615171724370.990245819
499242.907662898724258.160295546499043.613047183723751.612515777
498909.149298131723536.599133179498465.935930014723133.243165001
#Sta/Elev= 30
9260.958 124.9979506.543123.8289 9606.62116.7762 9643.67115.7491 9875.06115.0095
9948.771112.41919959.579111.03969981.268104.871710002.99 103.42710057.17112.5607
10326.85114.374910389.48117.257110425.04 121.00510437.92124.590610462.74125.6523
10475.19128.065310513.24129.177510526.29138.188810539.35152.807110565.45171.8849
10632.59211.335910669.35227.924110731.92251.832910872.56298.083710930.59 314.804
10975.76325.612411011.87332.844411050.94337.742311079.34337.788911099.29334.5407
#Mann= 3 , 0 , 0
9260.958   0.047       09260.958   0.047       011099.29   0.047       0
#XS Ineff= 2 , 0
       0                               0
Bank Sta=9260.958,11099.29
Exp/Cntr=0.3,0.1

Type RM Length L Ch R = 1 ,39048.07,249.105000,249.105000,249.105000
XS GIS Cut Line= 6
499468.930214942 724426.12776795499396.609882802724338.326187789
499366.675284207723794.371971399499274.223981082723509.836489514
499079.855071157723240.611810207498766.130768299722946.351436868
#Sta/Elev= 30
9486.103124.14339603.248124.26199664.088117.85499744.354115.01249954.376114.0605
9994.376101.233410004.38101.489110034.41108.693110064.48 113.10410094.59109.6942
10185.74114.044210342.05112.940910486.28118.732210556.97124.289110581.22124.1091
10643.15142.083910655.95 150.51210681.54163.301510719.93186.789610771.21223.0214
10800.63247.029210843.75274.0805 10941.1318.6206   11014347.357111088.98372.1519
11131.73377.873611171.36372.641811180.81369.628811196.12360.738311209.44359.0669
#Mann= 3 , 0 , 0
9486.103  0.0489       09486.103  0.0489       011209.44  0.0489       0
#XS Ineff= 2 , 0
       0                               0
Bank Sta=9486.103,11209.44
Exp/Cntr=0.3,0.1

Type RM Length L Ch R = 1 ,38798.97,996.420300,996.420300,996.420300
XS GIS Cut Line= 6
 499531.89762944724433.806720957499535.594217718724289.329357177
499637.470899254723859.813376904499613.012609452723586.588951513
499445.343628049723333.978991821498924.529623181722847.737363771
#Sta/Elev= 30
9490.639123.04749620.221121.97749681.792116.6463 9733.79114.40439900.621110.8022
9931.496111.77319992.586 101.46510002.69101.300910012.77103.145910022.85109.7763
10032.93111.774110053.09110.2607 10083.3112.4098 10213.5111.456810284.18113.6297
10316.34118.184310367.96120.498110704.62119.124610783.35123.300610805.01130.6177
 10840.5130.808810847.01132.257910889.01151.479210971.88200.318711067.02245.8655
11193.36302.316111241.36321.602811299.93341.8129   11331348.585911373.35351.5129
#Mann= 3 , 0 , 0
9490.639   0.048       09490.639   0.048       011373.35   0.048       0
#XS Ineff= 2 , 0
       0                               0
Bank Sta=9490.639,11373.35
Exp/Cntr=0.3,0.1

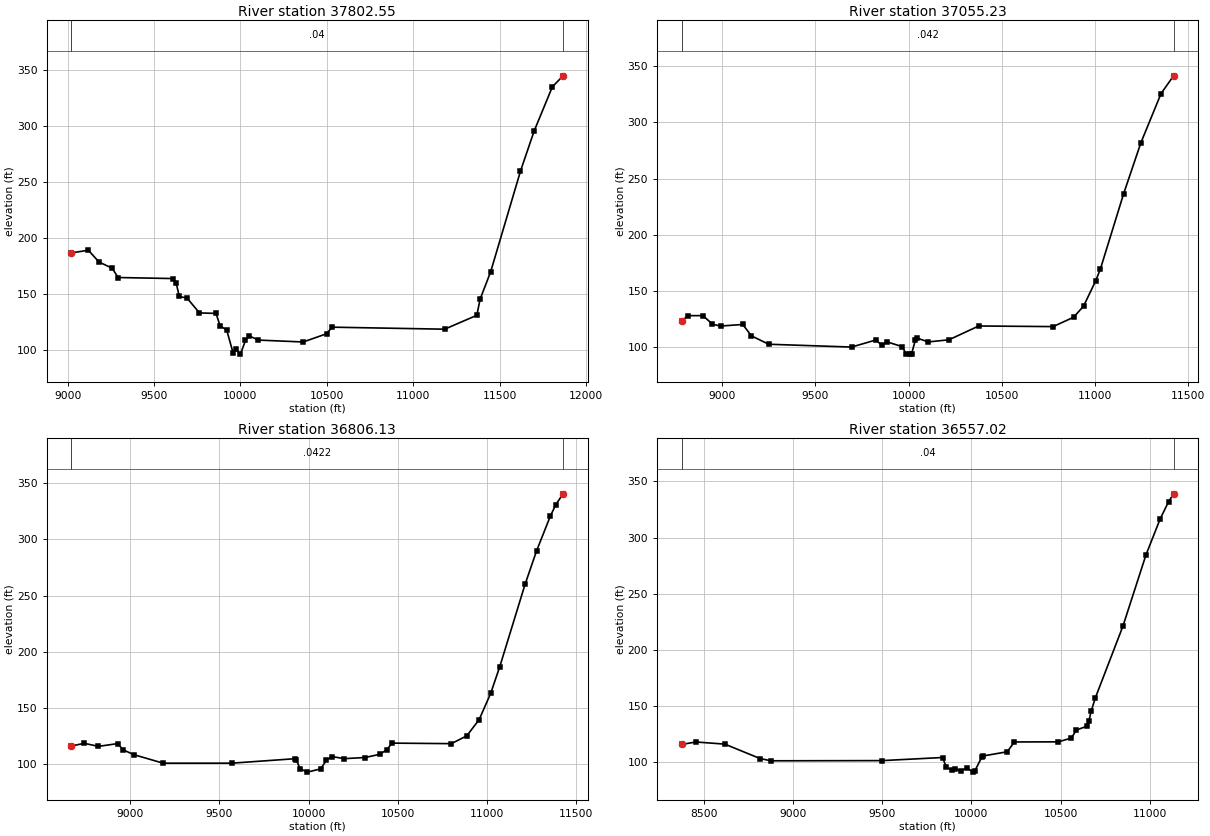
Type RM Length L Ch R = 1 ,37802.55,747.315200,747.315200,747.315200
XS GIS Cut Line= 6
501155.364938647724623.209073722500437.577896565724130.350045785
500302.196931571724010.941117585500107.640749961723892.964665264
499755.115522265723513.053636372498967.416145861722821.037583113
#Sta/Elev= 30
9021.021186.69979120.086189.0759 9181.72178.54299257.966173.00939292.168164.6952
9610.169163.76379628.384159.70899646.598147.76989691.549146.26659763.335133.0377
 9859.05 132.6449882.979121.33329920.375117.93979958.26597.111499972.186100.4745
 10000.596.2243710029.58108.464410050.77112.548610104.83108.762110363.75107.0862
 10499.6114.4628 10530.2 120.31711182.42118.508211368.84130.935711387.48145.2134
11448.74169.794511621.45259.7874 11700.8295.764511806.13335.168311867.89344.9585
#Mann= 3 , 0 , 0
9021.021    0.04       09021.021    0.04       011867.89    0.04       0
#XS Ineff= 2 , 0
       0                               0
Bank Sta=9021.021,11867.89
Exp/Cntr=0.3,0.1

Type RM Length L Ch R = 1 ,37055.23,249.105000,249.105000,249.105000
XS GIS Cut Line= 6
501371.581958473723774.111387208501033.578122437723543.777811348
500755.397568613723437.374603942499715.416920424723317.588073373
499424.953138471723133.531526849499013.632620186722792.264680803
#Sta/Elev= 30
8782.635 123.1048813.459128.18448896.276128.16948947.433120.59138990.588118.9182
9109.905120.33229156.226110.22829248.987 102.7519693.753100.2473 9824.28106.5431
9854.444102.02049884.717104.83559965.446100.6194  9985.594.4000410005.5193.96034
10015.5194.0916610035.52 106.23710045.54108.171110105.69104.812410215.77106.6805
10376.04118.981610774.92 118.43410884.56126.702410938.36136.585311002.62158.7916
11028.32  169.3711153.11236.352811246.33282.007711354.39325.6701 11421.5341.4051
#Mann= 3 , 0 , 0
8782.635   0.042       08782.635   0.042       0 11421.5   0.042       0
#XS Ineff= 2 , 0
       0                               0
Bank Sta=8782.635,11421.5
Exp/Cntr=0.3,0.1

Type RM Length L Ch R = 1 ,36806.13,249.105100,249.105100,249.105100
XS GIS Cut Line= 6
501439.310453117723726.958637804500662.157713205723176.725048095
500371.411518663723127.093717337500002.392235994723251.404562503
499749.192128986723245.113858446499050.685852677722769.196520492
#Sta/Elev= 30
8669.942116.3635 8743.01118.75468822.352 116.0468929.969118.51748959.506113.0373
9021.553108.63949184.307101.14059570.305101.13729921.898105.07479931.938103.7086
9952.05396.227459992.28393.1773310068.0796.06643 10099.8103.839310130.88106.9728
10200.41105.147710316.27106.159610397.13108.955510437.19112.868710467.26118.9372
10799.51118.466910885.79125.346210955.34139.759611020.26163.204211070.97186.8092
11212.65259.916811277.21289.656811353.78320.305611385.15330.793511425.61340.3195
#Mann= 3 , 0 , 0
8669.942  0.0422       08669.942  0.0422       011425.61  0.0422       0
#XS Ineff= 2 , 0
       0                               0
Bank Sta=8669.942,11425.61
Exp/Cntr=0.3,0.1

Type RM Length L Ch R = 1 ,36557.02,998.409400,998.409400,998.409400
XS GIS Cut Line= 6
501451.519529611723718.458647832500542.582725823723045.271588728
500169.368124843722984.917828187499976.693513274723129.593470395
499765.087880284723135.715275228499118.154260457722727.192842498
#Sta/Elev= 30
8375.798115.71658454.725117.9014 8617.13115.99368814.317 103.1778876.248101.1376
9498.991101.30779838.241104.06819858.27795.763619888.35292.756479908.63494.20216
 9939.72 92.19239975.55494.7508810008.1791.0458110019.7292.3958110058.47104.4373
 10067.1105.490810200.64109.177710240.98117.918910488.22118.018610560.83121.4822
10588.89128.548710647.07131.937410658.98136.752710671.06145.072710695.03157.2513
10849.36220.998110978.79284.535911057.91316.413811105.39331.885311133.57338.9456
#Mann= 3 , 0 , 0
8375.798    0.04       08375.798    0.04       011133.57    0.04       0
#XS Ineff= 2 , 0
       0                               0
Bank Sta=8375.798,11133.57
Exp/Cntr=0.3,0.1