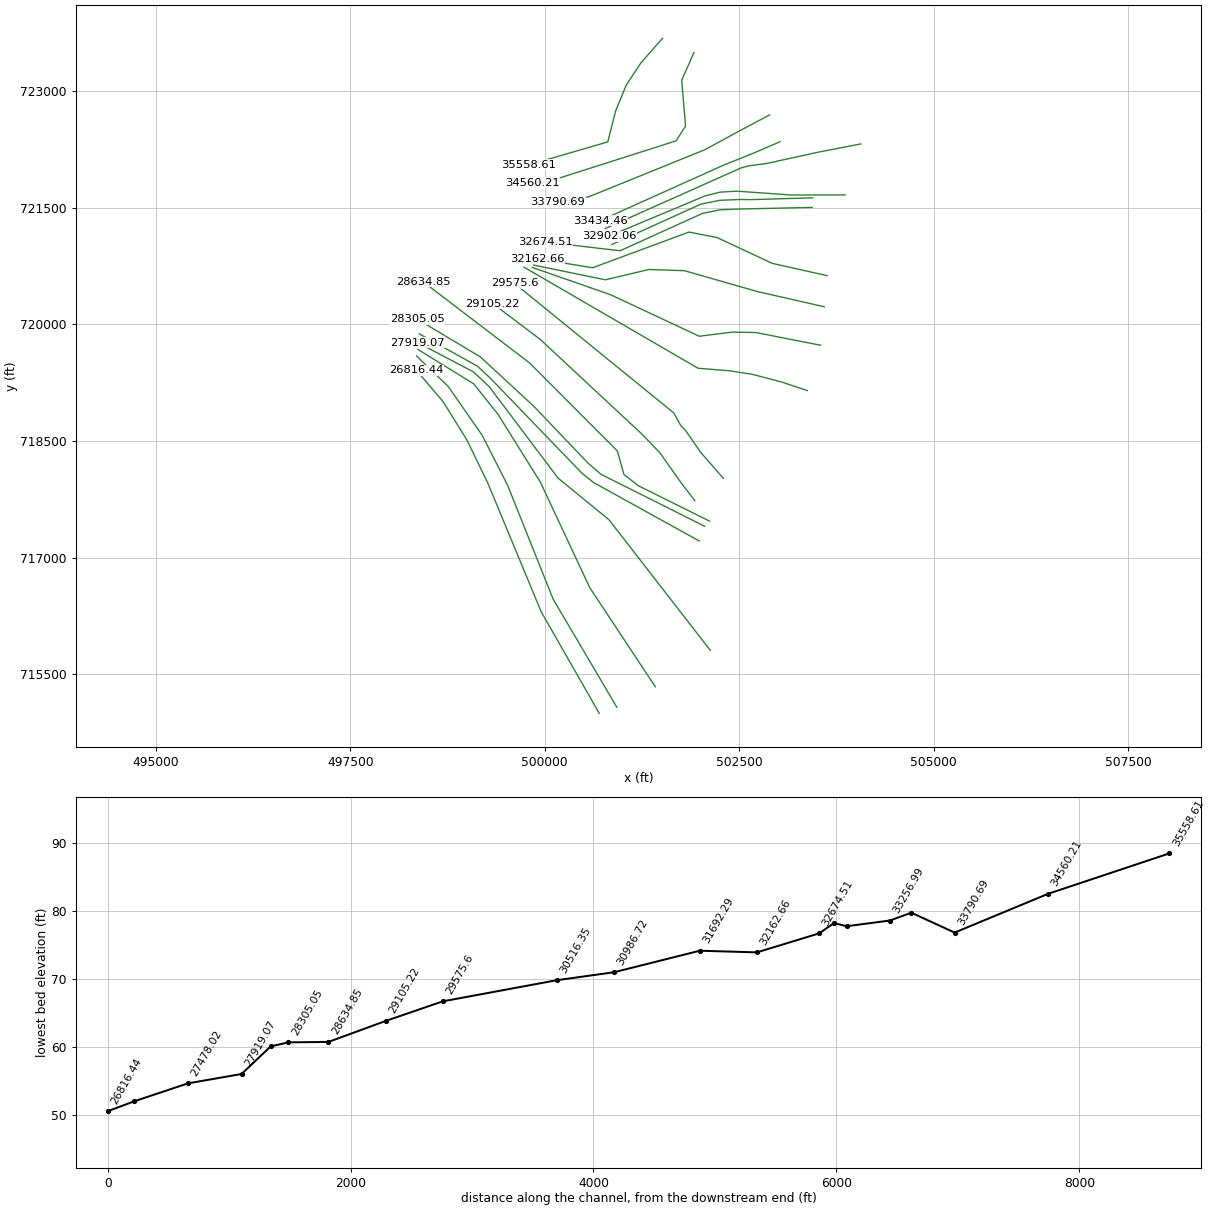
HEC-RAS study 978_ras.prj: 978

--- 978_ras.g01 (geometry) --- (continued)

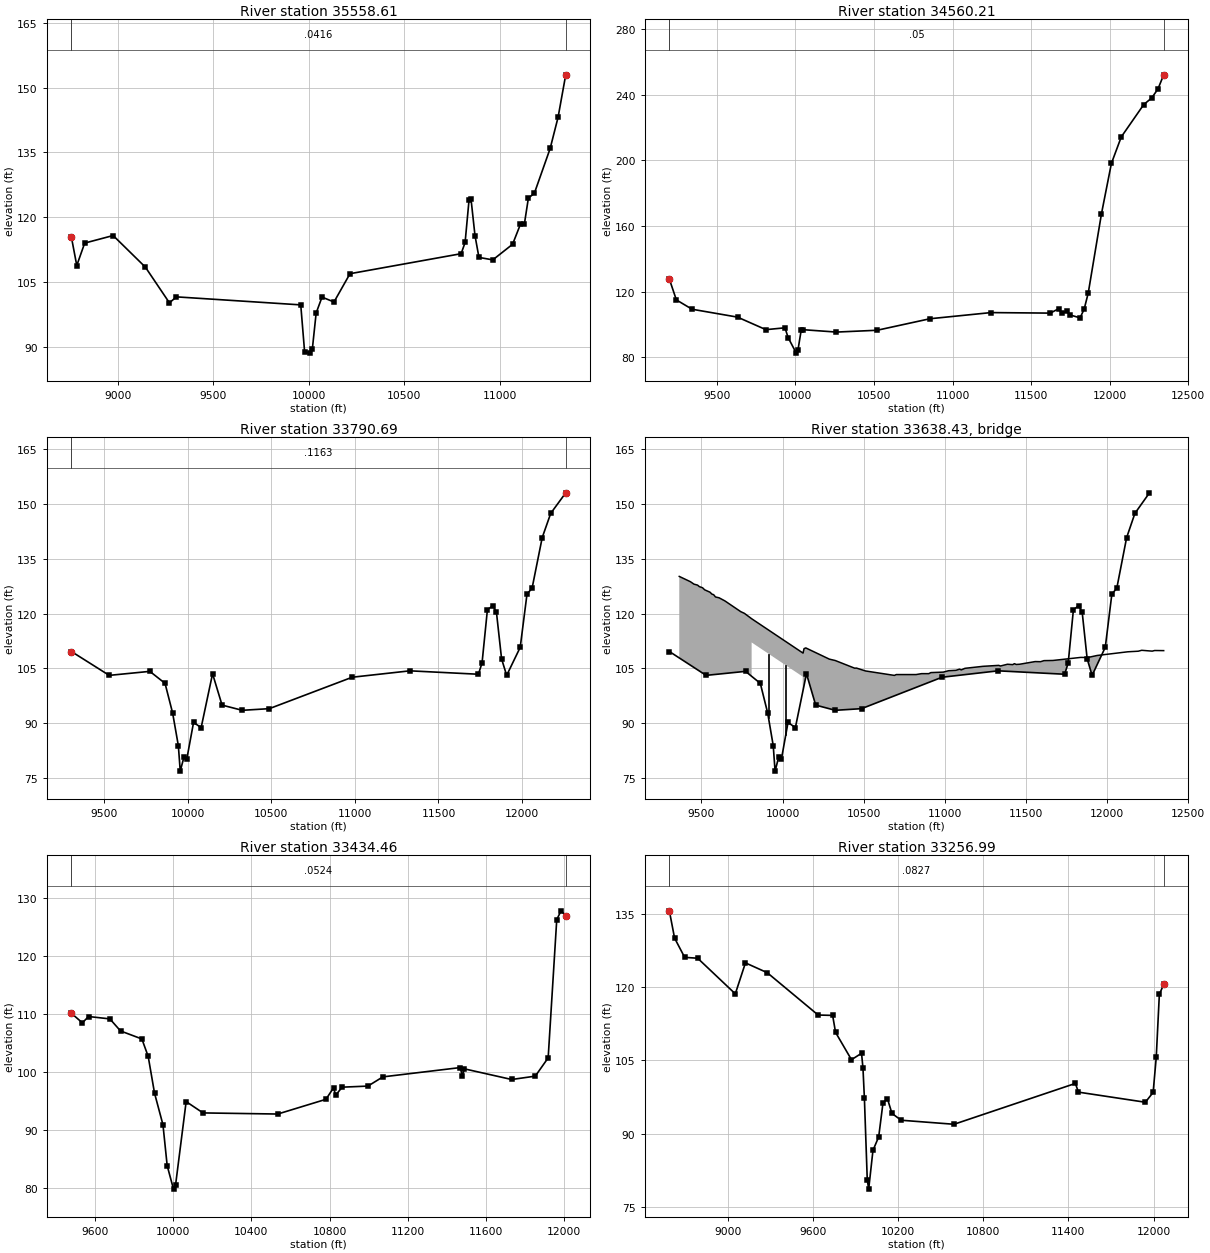
Type RM Length L Ch R = 1 ,35558.61,998.409300,998.409300,998.409300
XS GIS Cut Line= 6
501513.335800171723675.422003761501236.743411571723360.891939625
501048.503809929723077.571493417500909.557224125 722738.03857927
500810.189247102722344.346552178499796.260110348722049.428216398
#Sta/Elev= 30
8756.511115.38948784.749108.79658826.231113.99118975.325115.74199144.358108.4128
9270.207100.1516 9306.92101.5334 9958.4499.677499978.60788.7982510008.8388.50134
10018.8989.3422910039.1697.7961510069.89101.481310132.56100.342710216.42106.8984
 10798.9111.535210819.63114.132710840.36124.012410850.73124.165410871.46115.7395
10892.19110.674410964.74110.1002 11068.4113.715611109.86 118.37511130.59118.5006
11151.32124.429811182.41125.513311265.34135.9089 11306.8143.122811346.95152.9664
#Mann= 3 , 0 , 0
8756.511  0.0416       08756.511  0.0416       011346.95  0.0416       0
#XS Ineff= 2 , 0
       0                               0
Bank Sta=8756.511,11346.95
Exp/Cntr=0.3,0.1

Type RM Length L Ch R = 1 ,34560.21,769.512700,769.512700,769.512700
XS GIS Cut Line= 6
501917.317926228723492.784238622501760.163766056723136.433594465
501809.310099095722547.410214812501688.613183558722358.413136318
500048.787561476721835.329520181499838.566228747721819.292783663
#Sta/Elev= 30
9198.117127.66479242.682114.9902 9342.68109.28459631.786104.4875 9812.56 96.8465
9933.69297.973269954.26991.9397210005.7882.5478710016.14  84.24610036.8596.42786
10047.2196.8408110261.21 95.376510520.1796.4789110856.06103.494911244.42107.2448
 11622.3106.926911674.78109.601511695.77106.841811727.26 108.10711748.25105.7918
11811.23104.035511837.58109.369711863.71119.303911947.69167.515412010.66198.1011
12073.64214.297712216.68233.997812266.82 237.97812306.94243.465412343.48252.1013
#Mann= 3 , 0 , 0
9198.117    0.05       09198.117    0.05       012343.48    0.05       0
#XS Ineff= 2 , 0
       0                10387.07       0
Bank Sta=9198.117,12343.48
Exp/Cntr=0.3,0.1

Type RM Length L Ch R = 1 ,33790.69,356.235900,356.235900,356.235900
XS GIS Cut Line= 5
502889.712203294722691.009871528502543.757517844722507.920007229
 502057.64640674722244.031118348500568.063073397721639.864451677
500166.441395253721571.298108071
#Sta/Elev= 30
9302.493109.62049529.125103.07829772.145104.17759863.173100.89219908.68792.73722
9942.82283.81177  9954.276.833859976.95780.776419993.47580.1603310033.85 90.1763
10079.3688.7638710147.63103.532210204.5394.9282710325.4293.5015610487.2993.95378
10983.69102.568111329.01104.322211739.07 103.38811760.99106.491411793.03121.0766
 11825.4122.157711846.99120.438411877.87107.6073 11908.3103.071511989.46 110.768
12030.04125.347412060.47126.966112121.07140.827512172.07147.480112261.91153.1091
#Mann= 3 , 0 , 0
9302.493  0.1163       09302.493  0.1163       012261.91  0.1163       0
#XS Ineff= 2 , 0
       0 9740.09        10206.55       0
Bank Sta=9302.493,12261.91
Exp/Cntr=0.3,0.1

Type RM Length L Ch R = 3 ,33638.43,,,
BEGIN DESCRIPTION:
END DESCRIPTION:
Bridge Culvert--1,0,-1,-1, 0
Deck Dist Width WeirC Skew NumUp NumDn MinLoCord MaxHiCord MaxSubmerge Is_Ogee
131.117950,94.000000,2.6,0, 60, 60, , , 0.95, 0, 0,0,,
 9363.59 9432.37 9454.29 9476.21 9487.17 9507.22 9520.04 9553.32 9564.46 9575.60
 9586.74 9609.03 9644.85 9742.73 9765.02 9809.58 9809.5810124.5810124.5810126.49
10132.7010143.7010288.7010325.0610444.7010455.8510511.5610689.8510701.0010823.57
10857.0010901.5710914.3710990.7211024.1511068.7211091.0011102.1511124.4311235.86
11332.7811343.5311386.5211418.7711429.5211440.2611461.7611557.1811590.7311611.74
11665.9711837.9411880.9311939.1412128.1312192.6212214.1212278.6012293.8312349.53
  130.20  128.75  128.08  127.82  127.41  127.09  126.53  125.87  125.36  125.19
  124.57  124.34  123.49  120.54  120.08  118.61  118.61  109.24  109.24  109.18
  110.41  110.60  107.53  107.15  105.05  105.08  104.29  103.07  103.30  103.30
  103.55  103.55  103.84  103.97  104.36  104.46  104.78  104.58  105.01  105.56
  105.82  105.65  106.13  106.02  106.29  106.07  106.13  106.86  106.83  107.12
  107.16  108.00  107.97  108.53  109.54  109.70  109.95  109.72  109.89  109.86
 -869.80 -871.25 -871.92 -872.18 -872.59 -872.91 -873.47 -874.13 -874.64 -874.81
 -875.43 -875.66 -876.51 -879.46 -879.92 -881.39  112.11  102.74 -890.76 -890.82
 -889.59 -889.40 -892.47 -892.85 -894.95 -894.92 -895.71 -896.93 -896.70 -896.70
 -896.45 -896.45 -896.16 -896.03 -895.64 -895.54 -895.22 -895.42 -894.99 -894.44
 -894.18 -894.35 -893.87 -893.98 -893.71 -893.93 -893.87 -893.14 -893.17 -892.88
 -892.84 -892.00 -892.03 -891.47 -890.46 -890.30 -890.05 -890.28 -890.11 -890.14
 9363.59 9432.37 9454.29 9476.21 9487.17 9507.22 9520.04 9553.32 9564.46 9575.60
 9586.74 9609.03 9644.85 9742.73 9765.02 9858.22 9858.2210126.4910132.7010143.70
10173.2210173.2210210.7010221.8410288.7010325.0610444.7010455.8510511.5610689.85
10701.0010823.5710857.0010901.5710914.3710990.7211024.1511068.7211091.0011102.15
11124.4311235.8611332.7811343.5311386.5211418.7711429.5211440.2611461.7611557.18
11590.7311611.7411665.9711837.9411880.9311939.1412214.1212278.6012293.8312349.53
  130.20  128.75  128.08  127.82  127.41  127.09  126.53  125.87  125.36  125.19
  124.57  124.34  123.49  120.54  120.08  117.16  117.16  109.18  110.41  110.60
  110.06  110.06  109.07  109.02  107.53  107.15  105.05  105.08  104.29  103.07
  103.30  103.30  103.55  103.55  103.84  103.97  104.36  104.46  104.78  104.58
  105.01  105.56  105.82  105.65  106.13  106.02  106.29  106.07  106.13  106.86
  106.83  107.12  107.16  108.00  107.97  108.53  109.95  109.72  109.89  109.86
 -869.80 -871.25 -871.92 -872.18 -872.59 -872.91 -873.47 -874.13 -874.64 -874.81
 -875.43 -875.66 -876.51 -879.46 -879.92 -882.84  110.66  102.68  103.91  104.10
  103.56 -889.94 -890.93 -890.98 -892.47 -892.85 -894.95 -894.92 -895.71 -896.93
 -896.70 -896.70 -896.45 -896.45 -896.16 -896.03 -895.64 -895.54 -895.22 -895.42
 -894.99 -894.44 -894.18 -894.35 -893.87 -893.98 -893.71 -893.93 -893.87 -893.14
 -893.17 -892.88 -892.84 -892.00 -892.03 -891.47 -890.05 -890.28 -890.11 -890.14
Pier Skew, UpSta & Num, DnSta & Num=  ,9913.92, 2 ,9962.56, 2 , 0 , 0 , 0 ,,
    4.00    4.00
 -884.50  115.50
    4.00    4.00
 -885.94  114.06
Pier Skew, UpSta & Num, DnSta & Num=  ,10020.25, 2 ,10068.89, 2 , 0 , 0 , 0 ,,
    4.00    4.00
 -887.66  112.34
    4.00    4.00
 -889.11  110.89
BR Coef=-1 , 0 , 0 ,, 0 ,,,0.8,0,1,0,
WSPro=,,,, 1 ,,,, 0 ,,,, 0 ,,,,-1 ,-1 ,-1 , 0 , 0 , 0 , 0 , 0
BC Design=,, 0 ,, 0 ,,,,,,

Type RM Length L Ch R = 1 ,33434.46,177.465900,177.465900,177.465900
XS GIS Cut Line= 4
503025.665214243722347.128726144502668.016938968722193.550349114
502303.433605634 722047.71701578500713.155827857721332.439238002
#Sta/Elev= 30
9481.269110.15199537.352108.50139569.057109.59019677.887109.18129732.302 107.098
 9841.48105.71079873.747102.68959906.05896.349029949.13990.88789 9970.6883.81895
10002.9979.7638710013.7680.5216710067.61 94.888710153.7892.9330710535.5792.74022
10781.7495.2833210820.6697.2681110831.6395.9918610864.5297.38365 10996.197.56655
11072.8699.1625111467.59100.766711478.5699.3778311489.52100.546111730.75 98.7084
11851.3799.2873211917.16102.448111961.02126.338611982.95127.8545 12006.9127.0334
#Mann= 3 , 0 , 0
9481.269  0.0524       09481.269  0.0524       0 12006.9  0.0524       0
#XS Ineff= 2 , 0
       09820.471        10276.04       0
Bank Sta=9481.269,12006.9
Exp/Cntr=0.3,0.1

Type RM Length L Ch R = 1 ,33256.99,354.931700,354.931700,354.931700
XS GIS Cut Line= 6
504061.253492028722317.931545958503523.037638634722214.015692085
502855.050386161722067.621061638502623.659540236722036.839335993
502527.164697528722011.630968288500777.097886443721230.786732197
#Sta/Elev= 30
8589.304135.69928626.101130.10678697.175126.1571 8788.79125.97449053.854 118.669
9125.283125.02229278.804123.0088 9637.11114.32699739.484114.24619759.958110.7703
9872.139105.15929943.065106.48039953.139103.42259963.21397.221449983.32880.53253
9993.36878.6104210023.4886.5599810063.7789.3243810094.3796.3564310125.5697.15267
10157.1694.1479610222.0192.7420610594.5191.9149911449.06 100.29211470.9798.50645
11942.07 96.433311996.8598.4539412018.76105.634612040.68118.549712071.24120.6234
#Mann= 3 , 0 , 0
8589.304  0.0827       08589.304  0.0827       012071.24  0.0827       0
#XS Ineff= 2 , 0
       0                10341.76       0
Bank Sta=8589.304,12071.24
Exp/Cntr=0.3,0.1

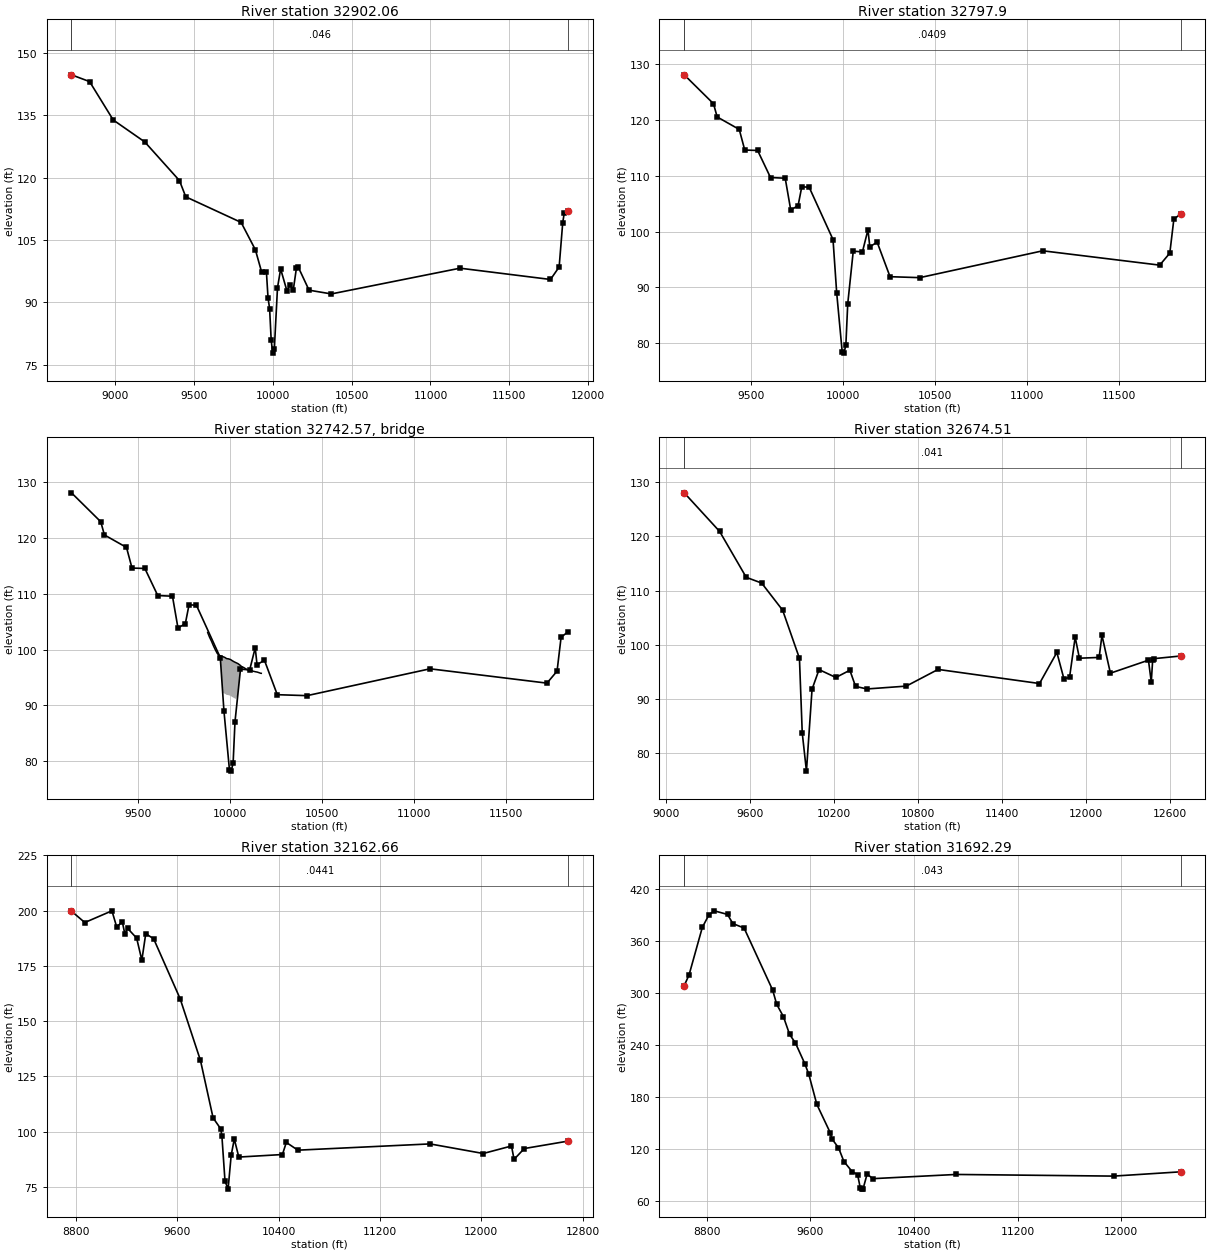
Type RM Length L Ch R = 1 ,32902.06,104.164100,104.164100,104.164100
XS GIS Cut Line= 6
503859.816156566721663.260205612503173.673889428721661.478520885
502468.050562114721711.262464881502254.436249912 721698.94218339
502059.375678122721649.760650903500824.039258957721132.481221795
#Sta/Elev= 30
8722.763144.77828837.608143.14878987.616133.90679187.621128.62299407.656119.3178
9447.698115.40729798.815109.24799889.306102.65959929.45597.223439959.53197.20405
9969.55691.071899979.58188.514149989.606  80.8719999.61677.7729610009.6278.79529
10029.6393.5318510049.6498.0288310089.6692.7387210109.6794.2876510129.6892.96622
10149.6898.2574810159.68 98.624910229.7392.9303910371.0292.0255211187.47 98.2222
11761.4395.5079611816.2698.50758 11839.1109.222311848.79111.501311871.51112.0053
#Mann= 3 , 0 , 0
8722.763   0.046       08722.763   0.046       011871.51   0.046       0
#XS Ineff= 2 , 0
       0                   10323       0
Bank Sta=8722.763,11871.51
Exp/Cntr=0.3,0.1

Type RM Length L Ch R = 1 , 32797.9,123.383500,123.383500,123.383500
XS GIS Cut Line= 6
 503444.10097991721625.446954918502659.289726348721602.632674292
502506.489885297721604.180216404502248.632675066721593.506962041
502009.082728485721545.596972725500861.524412958721025.431374434
#Sta/Elev= 30
9136.164128.09919295.332122.9204 9315.34120.55159435.391118.31979465.404114.6223
9535.433114.54739605.463109.69799685.497109.57359715.509103.87829755.526104.6634
9775.535108.02229815.552 107.9769945.59798.583239965.59889.00425  9995.6 78.4386
 10005.678.23668 10015.679.77627 10025.687.07031 10055.696.5011210105.6396.38144
10135.66100.341510145.6797.29711 10185.798.1119910255.7691.9305210417.4891.75979
11086.59 96.570311722.8294.0022411777.7296.1534411799.68102.222611836.43103.1768
#Mann= 3 , 0 , 0
9136.164  0.0409       09136.164  0.0409       011836.43  0.0409       0
#XS Ineff= 2 , 0
       0                 10412.5       0
Bank Sta=9136.164,11836.43
Exp/Cntr=0.3,0.1

Type RM Length L Ch R = 3 ,32742.57,,,
BEGIN DESCRIPTION:
END DESCRIPTION:
Bridge Culvert--1,0,-1,-1, 0
Deck Dist Width WeirC Skew NumUp NumDn MinLoCord MaxHiCord MaxSubmerge Is_Ogee
38.691750,46.000000,2.6,0, 43, 43, , , 0.95, 0, 0,0,,
 9876.92 9876.97 9887.29 9889.97 9897.61 9907.93 9918.24 9928.56 9930.63 9938.88
 9949.19 9950.61 9950.61 9959.51 9959.94 9969.80 9971.78 9980.09 9990.3810000.67
10010.9610014.2010021.2510031.5410041.8310052.1110052.1110052.1210056.6110062.41
10072.7010082.9910093.2810099.0310103.5710113.8610124.1510134.4410141.4410144.73
10155.0210165.3110168.78
  103.08  103.07  102.22  102.04  101.53  100.72  100.00   99.36   99.27   98.98
   98.86   98.84   98.84   98.75   98.74   98.62   98.58   98.40   98.35   98.24
   98.02   97.96   97.82   97.66   97.50   97.25   97.25   97.25   97.12   96.94
   96.81   96.59   96.39   96.42   96.44   96.29   96.14   96.06   96.01   96.00
   95.89   95.77   95.76
 -896.92 -896.93 -897.78 -897.96 -898.47 -899.28 -900.00 -900.64 -900.73 -901.02
 -901.14 -901.16   92.34   92.25   92.24   92.12   92.08   91.90   91.85   91.74
   91.52   91.46   91.32   91.16   91.00   90.75 -902.75 -902.75 -902.88 -903.06
 -903.19 -903.41 -903.61 -903.58 -903.56 -903.71 -903.86 -903.94 -903.99 -904.00
 -904.11 -904.23 -904.24
 9876.92 9876.97 9887.29 9889.97 9897.61 9907.93 9918.24 9928.56 9930.63 9938.88
 9944.89 9944.89 9949.19 9959.51 9959.94 9969.80 9971.78 9980.09 9990.3810000.67
10010.9610014.2010021.2510031.5410041.8310046.3910046.3910052.1210056.6110062.41
10072.7010082.9910093.2810099.0310103.5710113.8610124.1510134.4410141.4410144.73
10155.0210165.3110168.78
  103.08  103.07  102.22  102.04  101.53  100.72  100.00   99.36   99.27   98.98
   98.91   98.91   98.86   98.75   98.74   98.62   98.58   98.40   98.35   98.24
   98.02   97.96   97.82   97.66   97.50   97.39   97.39   97.25   97.12   96.94
   96.81   96.59   96.39   96.42   96.44   96.29   96.14   96.06   96.01   96.00
   95.89   95.77   95.76
 -896.92 -896.93 -897.78 -897.96 -898.47 -899.28 -900.00 -900.64 -900.73 -901.02
 -901.09   92.41   92.36   92.25   92.24   92.12   92.08   91.90   91.85   91.74
   91.52   91.46   91.32   91.16   91.00   90.89 -902.61 -902.75 -902.88 -903.06
 -903.19 -903.41 -903.61 -903.58 -903.56 -903.71 -903.86 -903.94 -903.99 -904.00
 -904.11 -904.23 -904.24
BR Coef=-1 , 0 , 0 ,, 0 ,,,0.8,0,1,0,
WSPro=,,,, 1 ,,,, 0 ,,,, 0 ,,,,-1 ,-1 ,-1 , 0 , 0 , 0 , 0 , 0
BC Design=,, 0 ,, 0 ,,,,,,

Type RM Length L Ch R = 1 ,32674.51,511.850600,511.850600,511.850600
XS GIS Cut Line= 6
 503437.88101691721502.674900115502498.926674366721481.344982341
502251.453162998721471.101531178502030.805014849721426.971901566
500968.389636129720945.399920732500006.822868019721057.452032313
#Sta/Elev= 30
9130.506128.02849383.494120.90639573.574112.44529683.621111.39129833.684 106.384
9953.72197.511359973.72283.7473310003.7276.7140410043.73   91.8110093.7595.43532
10213.8593.9825510313.9495.3171710354.6692.3344410436.25 91.863610716.8392.38883
10944.1395.4671911668.7792.8670711792.9298.5984811843.2693.7517611883.5393.99195
 11923.8101.4139   11954 97.534812094.9597.6769512115.09101.746312175.4994.77329
12447.3297.1690312467.4693.1505212477.5297.1937712487.59 97.455612677.0497.94146
#Mann= 3 , 0 , 0
9130.506   0.041       09130.506   0.041       012677.04   0.041       0
#XS Ineff= 2 , 0
       0                10518.39       0
Bank Sta=9130.506,12677.04
Exp/Cntr=0.3,0.1

Type RM Length L Ch R = 1 ,32162.66,470.375500,470.375500,470.375500
XS GIS Cut Line= 6
503628.285678357720625.595711872502924.269036055 720783.17111285
502215.274615347721114.497643173501853.429225206721185.619151324
500615.219714701720726.657744244499906.059097707720843.284623459
#Sta/Elev= 30
8765.073199.73488870.062194.58439084.348199.88259122.001192.56689166.198194.9556
9186.729189.26799207.295191.97849279.279187.55129320.412 177.5339351.303189.5309
9413.497187.23879622.387160.1363 9783.12132.17539882.824 106.1649943.648101.1522
9952.47497.839459976.71877.6295710001.17   73.9210025.6589.2720310050.1396.59632
10085.7688.4334310430.0989.5784410460.77 95.054410551.91  91.55411595.0594.38501
12015.2290.0453412238.1793.4432512258.4487.4020112339.5192.2941412683.0195.64113
#Mann= 3 , 0 , 0
8765.073  0.0441       08765.073  0.0441       012683.01  0.0441       0
#XS Ineff= 2 , 0
       0                10686.23       0
Bank Sta=8765.073,12683.01
Exp/Cntr=0.3,0.1

Type RM Length L Ch R = 1 ,31692.29,705.563300,705.563300,705.563300
XS GIS Cut Line= 6
503591.421960473720225.624374062502731.621998936720421.157562524
501794.345046133720689.218580514501337.784073383720704.475188076
 500779.70116958720571.979896039499858.316042185720760.819345698
#Sta/Elev= 30
8626.562308.31878663.841320.60998766.196375.31178817.373389.74318858.315394.3162
8960.686 390.1819001.685379.61919088.523374.52369309.335303.0173 9340.21286.7392
9391.669272.73729440.014252.05089484.295242.44519556.674218.62559587.766206.3631
 9649.95171.63569754.279138.78379764.738132.25549817.036121.8529 9858.98 105.914
9922.22894.380549964.39490.827379985.47775.367079996.01974.1623310006.5574.28751
10038.1391.6760610080.2286.1922210724.6891.0420511940.1689.1437912457.3894.07107
#Mann= 3 , 0 , 0
8626.562   0.043       08626.562   0.043       012457.38   0.043       0
#XS Ineff= 2 , 0
       0                10908.82       0
Bank Sta=8626.562,12457.38
Exp/Cntr=0.3,0.1

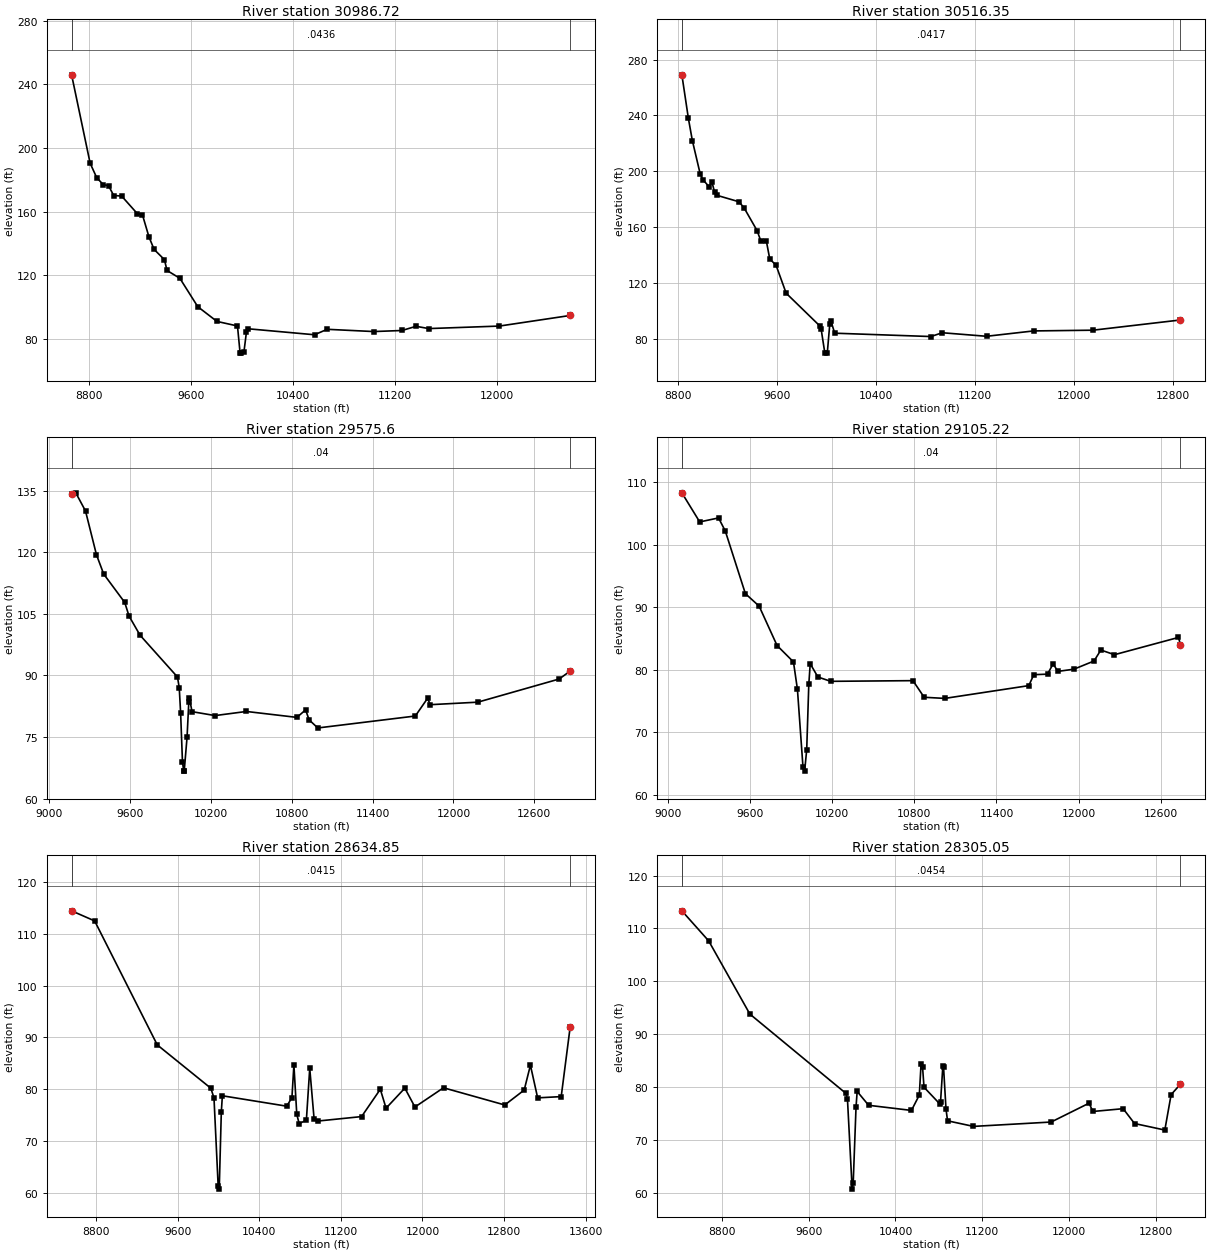
Type RM Length L Ch R = 1 ,30986.72,470.375500,470.375500,470.375500
XS GIS Cut Line= 6
503545.805881202719730.689913988502715.381672502719893.891116858
502413.660500765719900.056956232501985.113772869719846.668573692
500848.533124715720379.280000404499840.954931051 720730.43740125
#Sta/Elev= 30
8667.679246.06388812.901190.42818864.363181.35078915.613176.99258956.612176.3281
8997.612170.12669059.112169.83119181.403158.8023 9222.12158.06779273.001144.1863
9313.484136.24619394.367129.79339414.506123.00479515.198118.06499655.467100.2051
9805.52990.941099966.25388.073329986.38671.319319996.45270.99316 10016.671.59319
10036.7784.4694110046.8786.3289510569.24 82.550210668.6385.9767611033.07 84.5658
11253.9485.2321311364.3787.8680311463.76 86.435912016.0988.0133212571.0594.68694
#Mann= 3 , 0 , 0
8667.679  0.0436       08667.679  0.0436       012571.05  0.0436       0
#XS Ineff= 2 , 0
       0                11366.99       0
Bank Sta=8667.679,12571.05
Exp/Cntr=0.3,0.1

Type RM Length L Ch R = 1 ,30516.35,940.751000,940.751000,940.751000
XS GIS Cut Line= 6
503374.655828208719147.592833102503057.903946996719254.115467787
502673.039326876  719356.1896175502375.995814502719402.371047124
501970.420040548719435.228971809499732.447986603720734.777679026
#Sta/Elev= 30
8833.407269.09398886.127237.84578917.979222.05238981.324198.18729002.363 194.113
 9054.96188.81549075.999192.53079097.037185.22989118.076182.77839295.638 178.179
9337.302173.63679440.715157.59639471.649150.08969516.132149.9667 9543.37137.2887
9594.481 132.7259675.927112.72839947.89389.288369957.92187.350099988.00470.10442
10008.0669.82242 10028.190.3886210038.1292.6831210068.1984.0958910844.8981.69737
10937.1484.41842 11294.681.8810411675.1185.71779 12154.986.24188 12861.693.56016
#Mann= 3 , 0 , 0
8833.407  0.0417       08833.407  0.0417       0 12861.6  0.0417       0
#XS Ineff= 2 , 0
       0                11641.45       0
Bank Sta=8833.407,12861.6
Exp/Cntr=0.3,0.1

Type RM Length L Ch R = 1 , 29575.6,470.375500,470.375500,470.375500
XS GIS Cut Line= 6
502296.289362311718020.028416336 502003.07535094718354.881356776
501811.476945668718633.335225224501748.417801023718698.697330698
501659.005815119718860.323405623499610.920208812720526.444345698
#Sta/Elev= 30
9166.934134.24219197.908 134.4489270.149130.02869351.508119.36629405.094 114.681
9561.124 107.7699593.152104.44999674.70199.79446 9952.5589.610229965.66486.98967
9975.83380.873759989.50668.96925    999966.7021910002.6466.7760810023.5474.92589
10036.6483.6043210041.48 84.429510060.5781.1771510231.4280.2237610463.9881.22527
10838.6679.7824110903.2681.61856 10929.179.18498 10993.777.2107111717.2380.11665
11807.6784.40795 11828.782.8782812180.9583.4888112784.2189.1215612866.4591.06657
#Mann= 3 , 0 , 0
9166.934    0.04       09166.934    0.04       012866.45    0.04       0
#XS Ineff= 2 , 0
       0                11722.86       0
Bank Sta=9166.934,12866.45
Exp/Cntr=0.3,0.1

Type RM Length L Ch R = 1 ,29105.22,470.375500,470.375500,470.375500
XS GIS Cut Line= 6
501929.286201358717732.658016756501756.331514329717957.465104014
501481.424182862718346.344215885501255.517751276718582.534604654
 499941.60152629719806.274906188 499333.14243111720266.027679011
#Sta/Elev= 30
9099.648108.28789230.129103.63779367.802104.27499417.132102.18329563.975 92.1749
9664.52290.180489795.70283.881679915.54981.265919944.667 76.86689985.00464.51546
9997.12263.8098610012.3867.21245 10027.777.6785210038.0680.9753310094.1878.85337
 10187.978.1614110789.1878.2704110871.1775.6131911021.4975.4319211636.4477.47588
11672.7379.2239311773.0979.3063311814.0980.95911 11848.879.7506911966.1880.10147
12113.3181.4119112163.0783.1652812262.5982.4177312730.4885.1750412745.3484.00163
#Mann= 3 , 0 , 0
9099.648    0.04       09099.648    0.04       012745.34    0.04       0
#XS Ineff= 2 , 0
       0                11621.77       0
Bank Sta=9099.648,12745.34
Exp/Cntr=0.3,0.1

Type RM Length L Ch R = 1 ,28634.85,329.794800,329.794800,329.794800
XS GIS Cut Line= 6
502115.479077011717471.601693466501204.020743579717924.726693481
501018.088710636718068.754447713500933.303640395718371.846341521
 499805.00000003719503.316885248498434.770248115720548.719634503
#Sta/Elev= 30
8559.855 114.426 8785.98112.4791 9400.09 88.55289925.22680.19484 9956.2278.32349
9997.35561.2791410007.6260.7242110028.1575.6406810038.4178.7377510669.2976.72991
10720.5878.37478 10739.9 84.682110768.1475.1611810791.3973.36624 10862.274.02657
10895.2484.0293410937.6174.33923 10975.573.8630511403.6574.7222111587.2479.99387
11643.7376.3394811827.7880.21437 11926.776.5705612206.9680.28152 12807.876.96254
12998.3179.8396513059.3684.63812 13130.278.3365313361.2378.5763513449.5792.07388
#Mann= 3 , 0 , 0
8559.855  0.0415       08559.855  0.0415       013449.57  0.0415       0
#XS Ineff= 2 , 0
       0                11586.62       0
Bank Sta=8559.855,13449.57
Exp/Cntr=0.3,0.1

Type RM Length L Ch R = 1 ,28305.05,145.856600,145.856600,145.856600
XS GIS Cut Line= 6
502056.000062943 717403.95159696500725.822474569718070.367913708
 500558.09974876718214.238556147499860.270743579718945.560026795
499172.770743608719580.976693481498360.920208812720066.374901235
#Sta/Elev= 30
8428.847113.34448676.031107.66059056.31493.801349944.05878.764839957.23377.63044
10000.5460.6595710009.9361.7571610036.2876.2583310046.6179.1504210152.4776.52938
10547.6875.5594910620.1178.4656810636.2584.2962910650.0783.7970910663.5779.94769
10808.4276.8072910815.9377.1391210837.3983.9452510843.5883.8510310866.36 75.8325
10880.8573.5912511120.0272.5351811836.47 73.359612186.87 76.928412221.8275.35905
12501.45 75.887812606.31 73.078312885.9371.8450612944.1978.55488 13030.580.53363
#Mann= 3 , 0 , 0
8428.847  0.0454       08428.847  0.0454       0 13030.5  0.0454       0
#XS Ineff= 2 , 0
       09951.247        11561.59       0
Bank Sta=8428.847,13030.5
Exp/Cntr=0.3,0.1

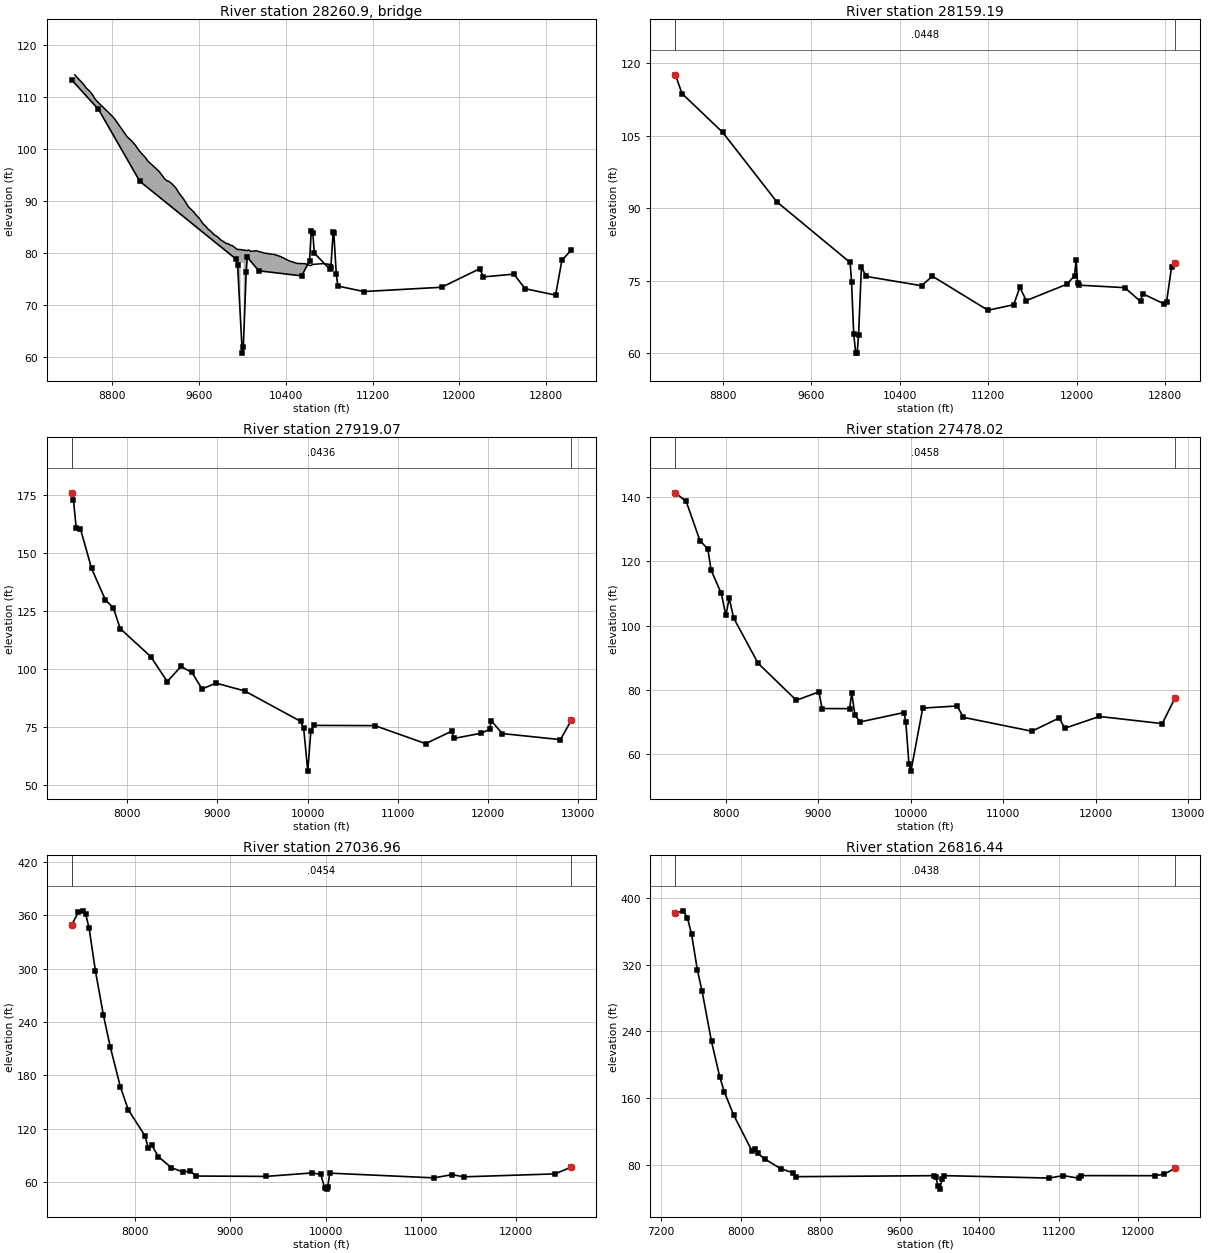
Type RM Length L Ch R = 3 , 28260.9,,,
BEGIN DESCRIPTION:
END DESCRIPTION:
Bridge Culvert--1,0,-1,-1, 0
Deck Dist Width WeirC Skew NumUp NumDn MinLoCord MaxHiCord MaxSubmerge Is_Ogee
61.778300,22.300000,2.6,0, 60, 60, , , 0.95, 0, 0,0,,
 8457.03 8536.66 8562.36 8595.61 8629.50 8639.93 8662.10 8806.15 8828.32 8939.46
 8984.57 9017.04 9052.22 9108.60 9131.15 9233.61 9288.95 9311.49 9320.32 9342.00
 9385.36 9424.20 9458.01 9503.08 9559.40 9570.66 9580.70 9593.19 9602.43 9638.24
 9667.63 9683.29 9711.10 9739.61 9773.12 9798.13 9857.41 9869.27 9893.02 9905.12
 9953.55 9984.23 9984.2310013.7310013.7310044.7610060.3610080.2810130.3610204.34
10297.9810354.1010432.8410508.5010578.6810620.7810634.8210648.8510747.1010830.05
  114.32  112.54  111.79  111.14  110.22  109.78  109.24  106.28  105.72  102.39
  101.51  100.73   99.63   98.36   97.69   95.71   94.19   93.82   93.83   93.50
   92.61   91.33   90.43   88.91   87.75   87.34   87.24   86.85   86.72   85.63
   85.04   84.60   84.14   83.51   83.09   82.55   81.76   81.78   81.43   81.44
   80.67   80.62   80.62   80.53   80.53   80.44   80.54   80.28   80.39   79.95
   79.66   79.27   78.44   77.94   77.91   77.56   77.57   77.77   77.92   77.71
 -885.68 -887.46 -888.21 -888.86 -889.78 -890.22 -890.76 -893.72 -894.28 -897.61
 -898.49 -899.27 -900.37 -901.64 -902.31 -904.29 -905.81 -906.18 -906.17 -906.50
 -907.39 -908.67 -909.57 -911.09 -912.25 -912.66 -912.76 -913.15 -913.28 -914.37
 -914.96 -915.40 -915.86 -916.49 -916.91 -917.45 -918.24 -918.22 -918.57 -918.56
 -919.33 -919.38   78.12   78.03 -919.47 -919.56 -919.46 -919.72 -919.61 -920.05
 -920.34 -920.73 -921.56 -922.06 -922.09 -922.44 -922.43 -922.23 -922.08 -922.29
 8457.03 8536.66 8562.36 8595.61 8629.50 8639.93 8662.10 8806.15 8828.32 8939.46
 8984.57 9017.04 9052.22 9108.60 9131.15 9233.61 9288.95 9311.49 9320.32 9342.00
 9385.36 9424.20 9458.01 9503.08 9559.40 9570.66 9580.70 9593.19 9602.43 9638.24
 9667.63 9683.29 9711.10 9739.61 9773.12 9798.13 9857.41 9869.27 9893.02 9905.12
 9953.55 9987.67 9987.6710017.1710017.1710044.7610060.3610080.2810130.3610204.34
10297.9810354.1010432.8410508.5010578.6810620.7810634.8210648.8510747.1010830.05
  114.32  112.54  111.79  111.14  110.22  109.78  109.24  106.28  105.72  102.39
  101.51  100.73   99.63   98.36   97.69   95.71   94.19   93.82   93.83   93.50
   92.61   91.33   90.43   88.91   87.75   87.34   87.24   86.85   86.72   85.63
   85.04   84.60   84.14   83.51   83.09   82.55   81.76   81.78   81.43   81.44
   80.67   80.61   80.61   80.52   80.52   80.44   80.54   80.28   80.39   79.95
   79.66   79.27   78.44   77.94   77.91   77.56   77.57   77.77   77.92   77.71
 -885.68 -887.46 -888.21 -888.86 -889.78 -890.22 -890.76 -893.72 -894.28 -897.61
 -898.49 -899.27 -900.37 -901.64 -902.31 -904.29 -905.81 -906.18 -906.17 -906.50
 -907.39 -908.67 -909.57 -911.09 -912.25 -912.66 -912.76 -913.15 -913.28 -914.37
 -914.96 -915.40 -915.86 -916.49 -916.91 -917.45 -918.24 -918.22 -918.57 -918.56
 -919.33 -919.39   78.11   78.02 -919.48 -919.56 -919.46 -919.72 -919.61 -920.05
 -920.34 -920.73 -921.56 -922.06 -922.09 -922.44 -922.43 -922.23 -922.08 -922.29
BR Coef=-1 , 0 , 0 ,, 0 ,,,0.8,0,1,0,
WSPro=,,,, 1 ,,,, 0 ,,,, 0 ,,,,-1 ,-1 ,-1 , 0 , 0 , 0 , 0 , 0
BC Design=,, 0 ,, 0 ,,,,,,

Type RM Length L Ch R = 1 ,28159.19,240.120900,240.120900,240.120900
XS GIS Cut Line= 6
  501985.1656681717215.586264431 500629.68362236  717965.2642809
500478.605533779718085.238057122499308.187410265719299.726693481
499136.312410235 719461.18502681 498387.44072479719876.640403196
#Sta/Elev= 30
8369.599117.59288429.104113.7216 8797.09105.70689286.66191.352369950.42978.80475
9963.19974.855889982.805 64.031510001.5160.0702110014.2860.1088610027.0563.90942
10052.5977.8557910095.3775.9299610597.5874.0021110694.7975.9750411197.8468.92822
11430.8570.07815 11486.473.69697 11543.770.9270111912.6474.3191311981.2476.08057
11994.9679.2465212008.6874.62231 12022.474.1150412436.0773.6081412578.1370.75005
12596.1772.3594612790.58 70.255912813.45 70.5933 12859.277.8881512890.7178.66923
#Mann= 3 , 0 , 0
8369.599  0.0448       08369.599  0.0448       012890.71  0.0448       0
#XS Ineff= 2 , 0
       09941.428        11611.18       0
Bank Sta=8369.599,12890.71
Exp/Cntr=0.3,0.1

Type RM Length L Ch R = 1 ,27919.07,441.054600,441.054600,441.054600
XS GIS Cut Line= 6
502127.814402282715809.388413087500826.124554515717487.212272346
500170.949791133718023.250413761499286.560174793719197.595505729
499084.229076892719388.268360153498368.508915454719763.049547181
#Sta/Elev= 30
7387.321175.82937407.086172.78337437.934160.72857484.207160.38647608.211143.2459
7760.253129.79747850.067126.22767924.695117.3808 8264.42105.26598446.38594.56456
8597.513 101.051 8719.7698.478478831.50591.383928985.54893.890749304.06890.51899
9923.45177.429099957.23974.4584610002.5355.9973910036.4973.1850410069.1775.68632
10746.0375.5894211308.2967.8338611596.4773.1828911620.8370.0742611919.7172.29318
 12015.973.9476212035.4777.6439812157.4272.1650812800.8469.5605612921.0577.87206
#Mann= 3 , 0 , 0
7387.321  0.0436       07387.321  0.0436       012921.05  0.0436       0
#XS Ineff= 2 , 0
       0                11733.77       0
Bank Sta=7387.321,12921.05
Exp/Cntr=0.3,0.1

Type RM Length L Ch R = 1 ,27478.02,441.054600,441.054600,441.054600
XS GIS Cut Line= 6
501421.038273692715340.992398873500577.996572435716615.669897348
499944.262847126717970.194726303 499398.34505266 718844.32366772
 499085.73910889719235.457902983498368.508915454719677.856405169
#Sta/Elev= 30
7456.119141.39387572.756138.70337720.998126.51677806.964123.84787841.644117.2826
7952.857110.00588001.361103.2049 8037.74108.56628086.245102.35418350.15688.23755
8763.403 76.71269007.43679.325819041.99274.134739339.52674.094849362.18779.00269
9396.17872.144259452.83169.954429926.92772.883459946.929 70.06269981.05956.79865
 10002.754.6194810130.1374.2769410502.3874.93678 10569.371.3949611309.3867.06164
11604.7571.1754911665.8767.9847912039.8771.6653512719.4269.43507 12858.277.43732
#Mann= 3 , 0 , 0
7456.119  0.0458       07456.119  0.0458       0 12858.2  0.0458       0
#XS Ineff= 2 , 0
       09893.848        11785.25       0
Bank Sta=7456.119,12858.2
Exp/Cntr=0.3,0.1

Type RM Length L Ch R = 1 ,27036.96,220.527300,220.527300,220.527300
XS GIS Cut Line= 6
 500927.13742998715077.145178901500107.629681587716467.869006887
499521.319173068717934.252035305499194.441227913718575.656274065
498758.667219877719201.444100037498353.350034744719592.153359801
#Sta/Elev= 30
7335.312349.24447405.296363.43497453.682365.0523 7481.47361.87567517.824345.9744
7585.605296.95657669.369247.42177740.541211.91497847.239166.88247929.548141.3306
8105.096111.88038140.08497.837788174.863101.86388244.06488.622298382.46776.07594
8501.16771.330898576.51272.317638644.78166.699829375.27766.307169854.73870.15632
9949.66668.693969991.699 53.021710012.6451.98374 10023.154.6199910044.3269.96525
11136.2964.6657511328.5268.2449711450.0165.8073312407.32 69.111412579.0776.73497
#Mann= 3 , 0 , 0
7335.312  0.0454       07335.312  0.0454       012579.07  0.0454       0
#XS Ineff= 2 , 0
       09845.414         11580.7       0
Bank Sta=7335.312,12579.07
Exp/Cntr=0.3,0.1

Type RM Length L Ch R = 1 ,26816.44,220.527300,220.527300,220.527300
XS GIS Cut Line= 6
500700.664008268714999.443000742499955.112082958716303.080368266
499266.986777842717962.001370937499000.939215571718510.614287242
 498694.40023753719004.244098872498348.090833634719411.587456211
#Sta/Elev= 30
7344.464382.49837423.044385.05657464.129376.97647506.278357.43267565.611313.6604
7613.077  288.197707.398228.08257789.572 185.7857836.365167.53077929.582 139.754
8117.30395.771398149.34998.520868172.209 93.42228240.72686.981558405.91874.88758
8524.93370.391168557.30365.479559941.67566.699549963.52665.423639985.37754.23118
10003.0450.5113710029.1162.8811310050.9866.73306 11100.763.8146811247.4166.74005
11408.06  63.54411419.6766.7625612168.9866.6652712260.3568.4965212370.4875.52864
#Mann= 3 , 0 , 0
7344.464  0.0438       07344.464  0.0438       012370.48  0.0438       0
#XS Ineff= 2 , 0
       09851.612        11429.29       0
Bank Sta=7344.464,12370.48
Exp/Cntr=0.3,0.1