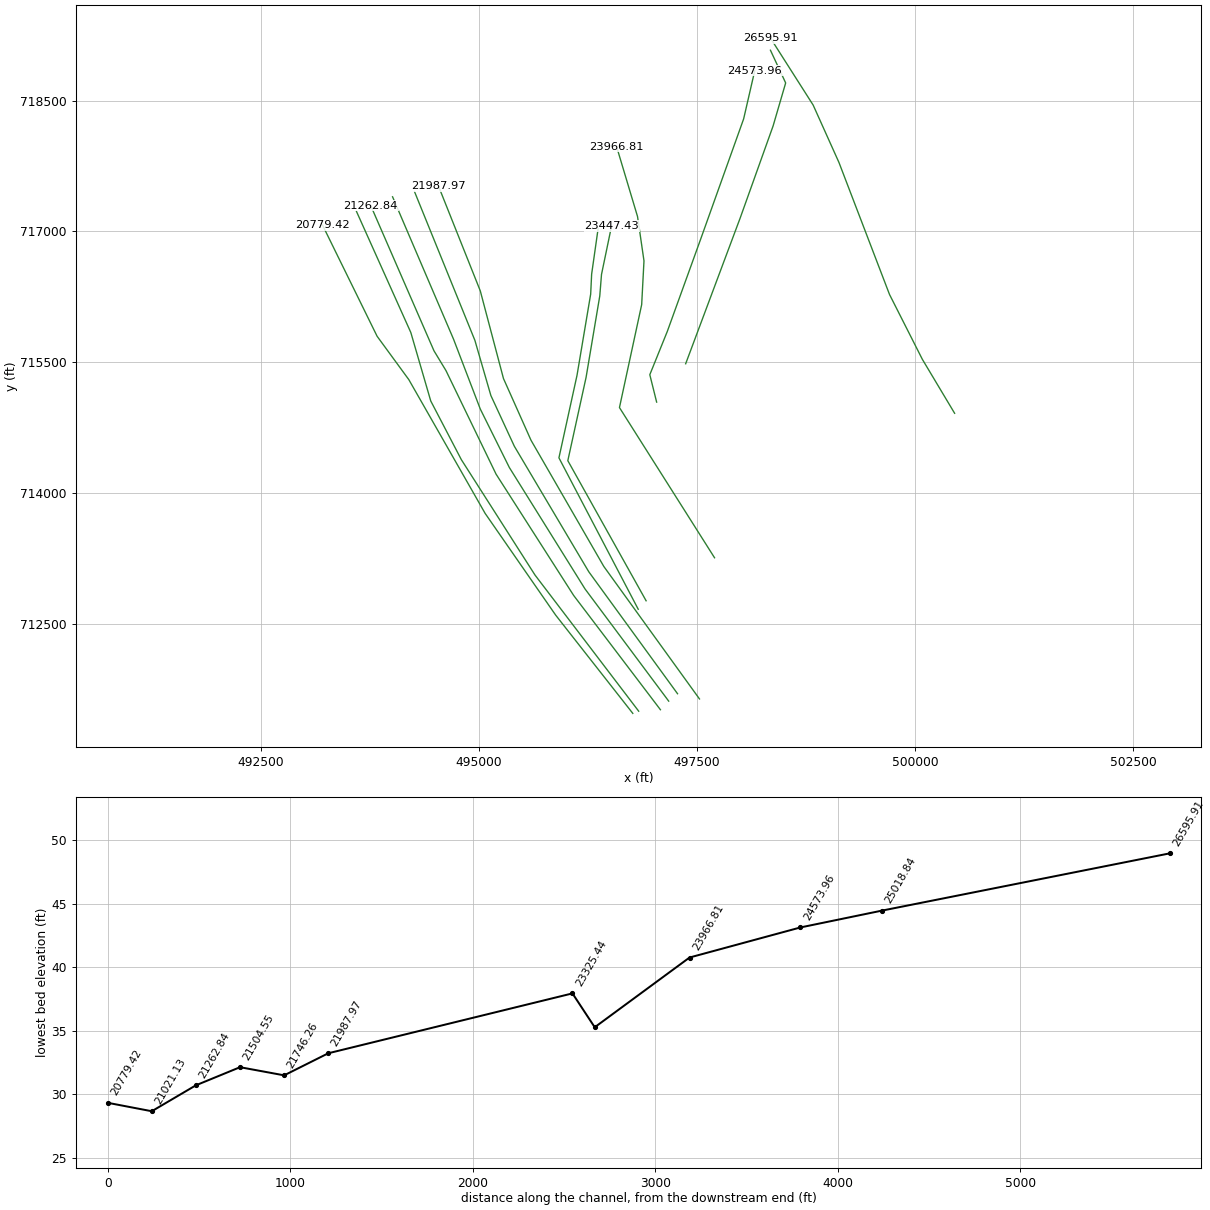
HEC-RAS study 978_ras.prj: 978

--- 978_ras.g01 (geometry) --- (continued)

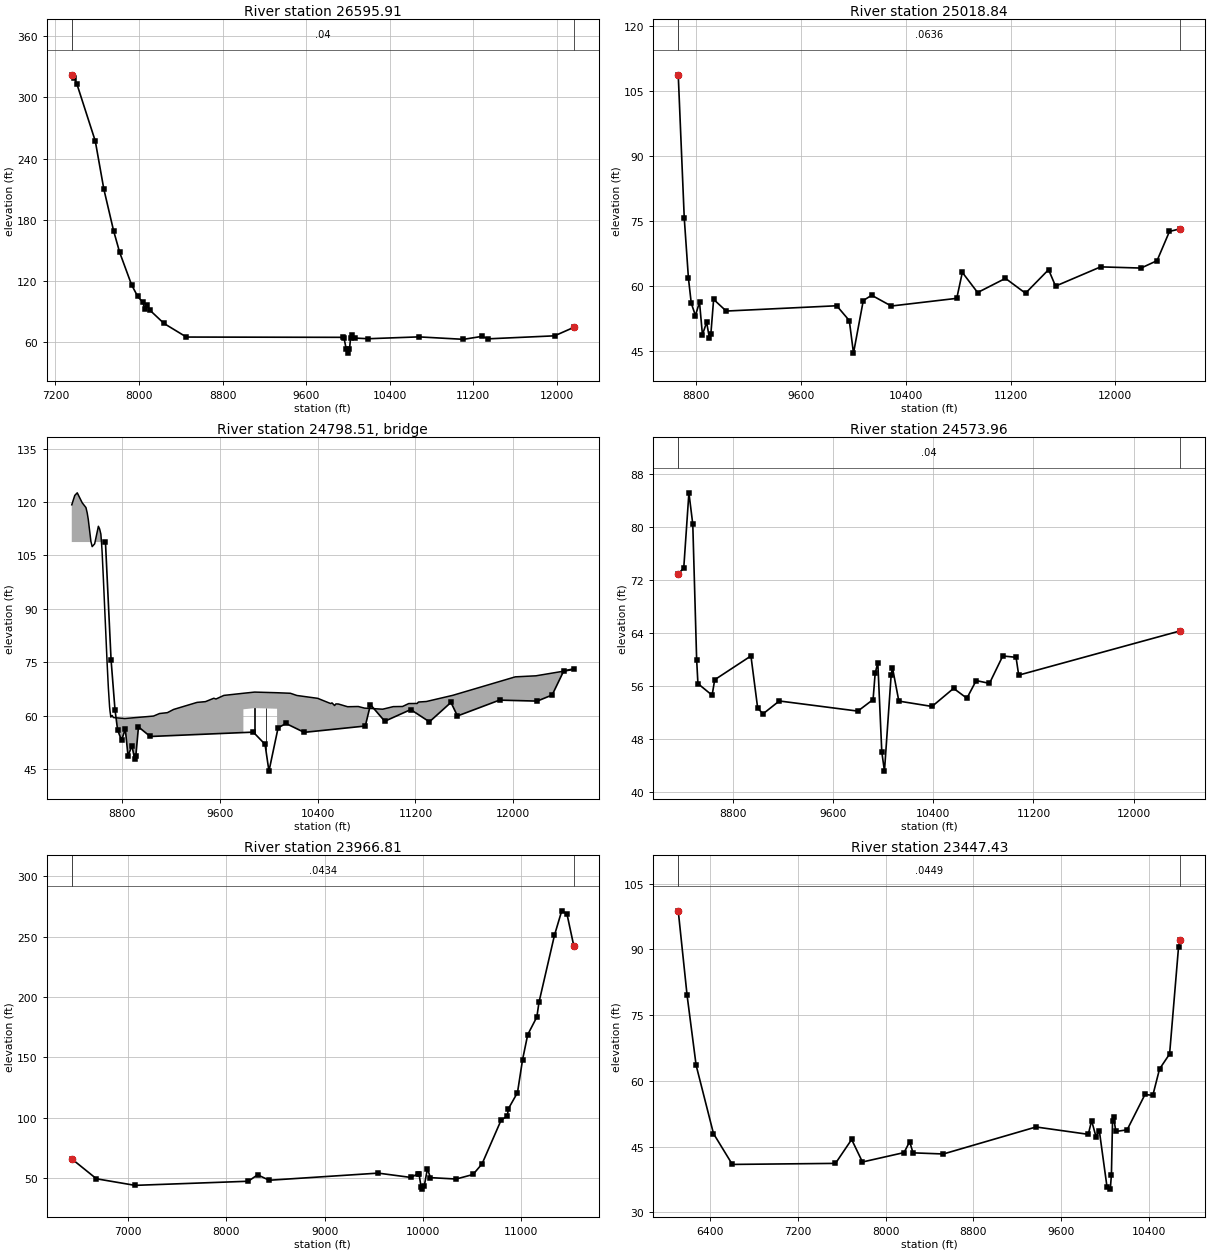
Type RM Length L Ch R = 1 ,26595.91,1577.069800,1577.069800,1577.069800
XS GIS Cut Line= 6
500451.767201851 714914.04744373500082.136252344 715532.21914418
499705.430986285716275.981433779499125.702637941717789.811852515
498829.985361934718447.648822397498342.308838427719213.072287589
#Sta/Elev= 30
7356.274322.23297381.099319.50897406.451312.85317581.504257.13437663.318209.9982
7756.739169.10457814.667147.9269 7928.76116.04127987.888104.57228033.85699.19469
 8056.8492.30847 8079.7995.922248102.52291.284058238.89778.116388453.66264.74292
9951.976 64.46469962.50363.772759984.437 52.792910004.6148.9565510015.1552.84456
 10025.764.0087110036.2467.2132510067.8763.7302810195.0963.1014210678.4964.90978
 11106.162.5057411286.0865.4356611341.0562.9834511978.7665.94784 12163.174.26619
#Mann= 3 , 0 , 0
7356.274    0.04       07356.274    0.04       0 12163.1    0.04       0
#XS Ineff= 2 , 0
       09700.578        11289.97       0
Bank Sta=7356.274,12163.1
Exp/Cntr=0.3,0.1

Type RM Length L Ch R = 1 ,25018.84,444.882600,444.882600,444.882600
XS GIS Cut Line= 5
497368.121553659715481.978700921497993.748819917 717154.57404539
498370.401969999718207.926075295498514.638413131718701.658515304
498340.111201465719076.771458849
#Sta/Elev= 30
8663.223108.76148709.15675.680028741.18661.725668762.53956.021028794.56953.11815
8825.57656.242868847.95248.687578879.98251.589798901.33647.893648912.01248.79274
8933.36656.869679029.456 54.17249872.91255.396889969.00151.9740710001.0344.45072
10075.7756.6064910139.8357.82589 10289.355.3354310789.2957.1110110831.7763.10608
10948.5958.4496411160.9961.7279611314.0258.2893711490.2263.7384411543.3259.93432
11887.5764.3840312196.0164.1066512318.2365.8193312413.0572.5726512495.7673.18294
#Mann= 3 , 0 , 0
8663.223  0.0636       08663.223  0.0636       012495.76  0.0636       0
#XS Ineff= 2 , 0
       0 9762.83        10173.11       0
Bank Sta=8663.223,12495.76
Exp/Cntr=0.3,0.1

Type RM Length L Ch R = 3 ,24798.51,,,
BEGIN DESCRIPTION:
END DESCRIPTION:
Bridge Culvert--1,0,-1,-1, 0
Deck Dist Width WeirC Skew NumUp NumDn MinLoCord MaxHiCord MaxSubmerge Is_Ogee
201.441300,42.000000,2.6,0, 60, 60, , , 0.95, 0, 0,0,,
 8387.59 8412.10 8432.44 8473.13 8503.65 8513.82 8522.55 8544.34 8554.51 8574.86
 8605.38 8615.55 8625.72 8631.62 8635.89 8646.07 8676.58 8686.76 8696.93 8700.58
 8707.26 8717.68 8728.10 8821.87 9056.31 9105.65 9170.09 9220.80 9412.71 9481.54
 9549.78 9567.46 9632.03 9791.81 9791.81 9883.8810067.4110067.4110176.3410229.38
10399.6510506.0610516.7010537.9910548.6310569.9110644.4010732.0210782.7410931.72
11018.1311094.1011144.5211213.4711224.3311289.4411504.9012016.6012185.2612472.48
  119.22  121.85  122.58  119.78  118.44  116.95  115.14  108.92  107.48  108.26
  113.19  112.44  110.99  108.34  105.91   98.58   74.97   67.97   62.53   61.29
   59.62   60.08   59.49   59.22   59.91   60.62   60.87   61.77   63.75   63.96
   64.91   64.70   65.71   66.31   66.31   66.64   66.46   66.46   66.31   65.69
   64.89   63.42   63.61   62.87   63.32   63.29   62.53   62.59   62.14   61.84
   62.56   62.60   63.42   63.45   63.85   64.00   65.73   70.92   71.21   72.86
 -880.78 -878.15 -877.42 -880.22 -881.56 -883.05 -884.86 -891.08 -892.52 -891.74
 -886.81 -887.56 -889.01 -891.66 -894.09 -901.42 -925.03 -932.03 -937.47 -938.71
 -940.38 -939.92 -940.51 -940.78 -940.09 -939.38 -939.13 -938.23 -936.25 -936.04
 -935.09 -935.30 -934.29 -933.69   61.81   62.14   61.96 -933.54 -933.69 -934.31
 -935.11 -936.58 -936.39 -937.13 -936.68 -936.71 -937.47 -937.41 -937.86 -938.16
 -937.44 -937.40 -936.58 -936.55 -936.15 -936.00 -934.27 -929.08 -928.79 -927.14
 8387.59 8401.93 8412.10 8432.44 8473.13 8503.65 8513.82 8522.55 8544.34 8554.51
 8574.86 8595.20 8605.38 8615.55 8625.72 8631.62 8635.89 8646.07 8676.58 8686.76
 8696.93 8700.58 8707.26 8717.68 8728.10 8821.87 9056.31 9105.65 9170.09 9220.80
 9412.71 9481.54 9492.28 9535.24 9549.78 9567.46 9632.03 9910.10 9910.1010176.34
10228.3610228.3610399.6510506.0610516.7010537.9910548.6310569.9110644.4010964.34
11018.1311094.1011144.5211213.4711224.3311289.4411504.9012016.6012185.2612472.48
  119.22  121.00  121.85  122.58  119.78  118.44  116.95  115.14  108.92  107.48
  108.26  111.79  113.19  112.44  110.99  108.34  105.91   98.58   74.97   67.97
   62.53   61.29   59.62   60.08   59.49   59.22   59.91   60.62   60.87   61.77
   63.75   63.96   64.35   64.47   64.91   64.70   65.71   66.61   66.61   66.31
   65.70   65.70   64.89   63.42   63.61   62.87   63.32   63.29   62.53   61.93
   62.56   62.60   63.42   63.45   63.85   64.00   65.73   70.92   71.21   72.86
 -880.78 -879.00 -878.15 -877.42 -880.22 -881.56 -883.05 -884.86 -891.08 -892.52
 -891.74 -888.21 -886.81 -887.56 -889.01 -891.66 -894.09 -901.42 -925.03 -932.03
 -937.47 -938.71 -940.38 -939.92 -940.51 -940.78 -940.09 -939.38 -939.13 -938.23
 -936.25 -936.04 -935.65 -935.53 -935.09 -935.30 -934.29 -933.39   62.11   61.81
   61.20 -934.30 -935.11 -936.58 -936.39 -937.13 -936.68 -936.71 -937.47 -938.07
 -937.44 -937.40 -936.58 -936.55 -936.15 -936.00 -934.27 -929.08 -928.79 -927.14
Pier Skew, UpSta & Num, DnSta & Num=  ,9883.01, 2 ,10015.52, 2 , 0 , 0 , 0 ,,
    4.00    4.00
 -933.36   66.64
    4.00    4.00
 -933.49   66.51
Pier Skew, UpSta & Num, DnSta & Num=  ,9976.21, 2 ,10122.94, 2 , 0 , 0 , 0 ,,
    4.00    4.00
 -933.45   66.55
    4.00    4.00
 -933.66   66.34
BR Coef=-1 , 0 , 0 ,, 0 ,,,0.8,0,1,0,
WSPro=,,,, 1 ,,,, 0 ,,,, 0 ,,,,-1 ,-1 ,-1 , 0 , 0 , 0 , 0 , 0
BC Design=,, 0 ,, 0 ,,,,,,

Type RM Length L Ch R = 1 ,24573.96,607.146700,607.146700,607.146700
XS GIS Cut Line= 6
497035.275445402715042.231876642496956.989840835715356.369929805
497157.451147705715852.247899309497540.488249451716911.983880922
498032.655961692718288.881647304498159.731564015718839.937293261
#Sta/Elev= 30
8360.88672.948378404.962 73.79928446.185 85.17448477.10380.43984 8508.0259.96249
8518.32656.35206 8631.6954.596328652.30256.936748942.02360.531618995.95452.63386
9039.099 51.78879168.53353.729339796.61352.198599918.32753.944029934.844  57.905
9956.11159.51869 9988.0146.0255810009.2843.1313610062.4457.5788310073.0858.77288
10124.2653.7085710389.4452.9023110561.9355.6350910668.1254.1426710742.4656.80999
10848.6656.3892710954.8560.5282511061.0560.3270511082.2957.6323512374.0764.32193
#Mann= 3 , 0 , 0
8360.886    0.04       08360.886    0.04       012374.07    0.04       0
#XS Ineff= 2 , 0
       09917.509        10278.09       0
Bank Sta=8360.886,12374.07
Exp/Cntr=0.3,0.1

Type RM Length L Ch R = 1 ,23966.81,519.376000,519.376000,519.376000
XS GIS Cut Line= 6
 497699.28154552713257.453575119496609.003767759714979.675797358
496863.771989286716160.064133331496890.214041173716661.887764961
496816.329204291717169.656661868496576.300182104 717971.27173081
#Sta/Elev= 30
  6426.965.809356677.94649.33994 7070.5543.88888 8222.9847.293048317.66352.61574
8436.01748.124679544.60754.031569880.33550.425639950.91253.638959961.24353.19582
9982.41442.15597    999340.7662510014.2343.4366610046.0557.6595110077.0450.28817
10338.2549.1318310510.2452.8928710602.2261.7140910797.1898.1539210859.06101.1799
10869.54107.281910962.72120.766611014.55148.145711066.72168.740411159.74183.4047
11181.64195.659511339.04251.143511412.97271.378911465.87268.902511536.24242.1278
#Mann= 3 , 0 , 0
  6426.9  0.0434       0  6426.9  0.0434       011536.24  0.0434       0
#XS Ineff= 2 , 0
       09464.615                       0
Bank Sta=6426.9,11536.24
Exp/Cntr=0.3,0.1

Type RM Length L Ch R = 1 ,23447.43,121.991100,121.991100,121.991100
XS GIS Cut Line= 6
496914.559323307712764.398019563496016.965171864714370.696786668
496226.251644262715325.566316985496383.216498561716258.635173094
496403.228399501716506.075366228496518.380678652717060.899983955
#Sta/Elev= 30
6108.60498.802586189.48279.484926271.70263.555586430.04447.957736601.87540.91824
7542.705 41.15537690.13446.612797788.70641.472148168.068 43.62088219.255 46.1118
8249.96743.561288526.37743.302279371.82249.464839848.42647.787459878.76250.90492
9918.78447.24273  9948.848.6525910019.0335.8037110049.2735.2798310059.3538.58399
10069.4350.78724 10079.551.6556610099.66 48.437910202.5148.8103910365.6356.88476
   10437 56.683510498.17 62.697510589.9366.1215610671.4990.52706 10687.792.15177
#Mann= 3 , 0 , 0
6108.604  0.0449       06108.604  0.0449       0 10687.7  0.0449       0
#XS Ineff= 2 , 0
       08971.628                       0
Bank Sta=6108.604,10687.7
Exp/Cntr=0.3,0.1

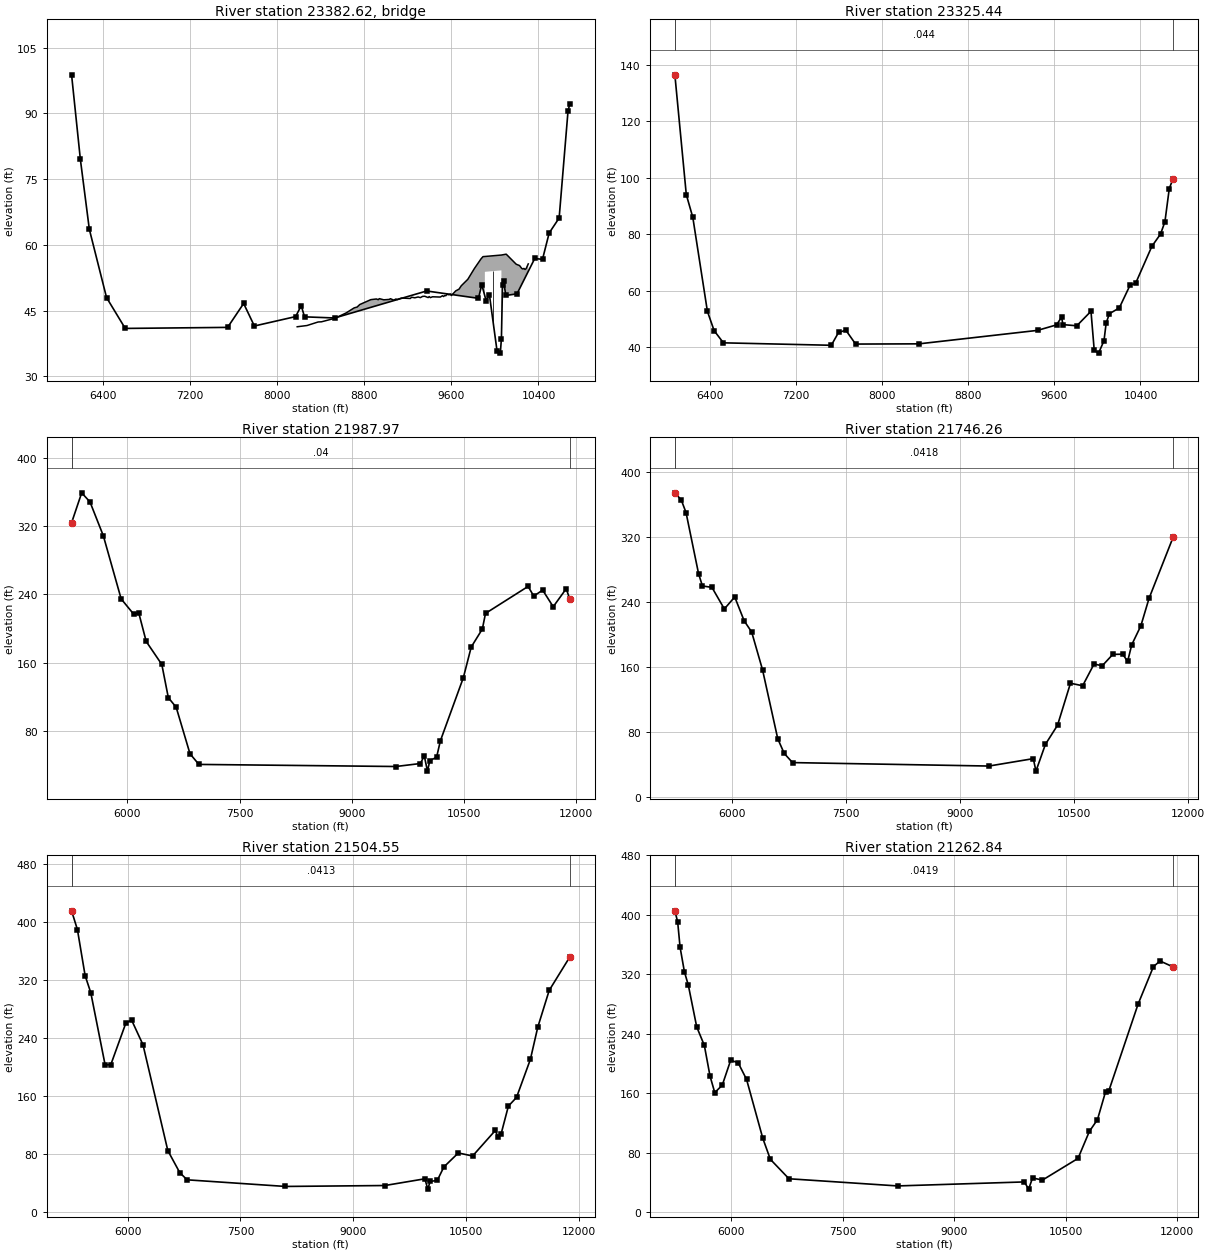
Type RM Length L Ch R = 3 ,23382.62,,,
BEGIN DESCRIPTION:
END DESCRIPTION:
Bridge Culvert--1,0,-1,-1, 0
Deck Dist Width WeirC Skew NumUp NumDn MinLoCord MaxHiCord MaxSubmerge Is_Ogee
48.695550,24.600000,2.6,0, 60, 60, , , 0.95, 0, 0,0,,
 8182.34 8272.25 8374.77 8405.52 8528.55 8631.08 8706.14 8733.24 8757.22 8859.36
 8910.44 8926.99 8937.18 8977.97 9028.96 9039.16 9069.75 9090.14 9100.34 9141.13
 9222.69 9232.87 9263.43 9293.99 9314.36 9334.73 9355.11 9385.66 9395.85 9406.04
 9426.41 9497.52 9517.83 9527.98 9538.14 9548.29 9558.44 9578.75 9588.90 9599.06
 9639.58 9669.90 9690.11 9750.74 9811.37 9872.01 9890.22 9907.37 9907.3710059.37
10059.3710103.3410195.5310226.0410246.2810256.3910266.5110276.6310286.7510306.05
   41.30   41.58   42.39   42.43   43.23   44.44   45.61   45.80   46.37   47.49
   47.64   47.48   47.72   47.45   47.54   47.71   47.37   47.64   47.50   47.85
   47.75   48.04   47.91   48.10   47.95   48.23   48.26   47.96   48.19   47.95
   48.14   48.08   48.38   48.20   48.44   48.38   48.70   48.59   48.78   48.42
   49.49   49.89   50.65   52.14   54.61   56.80   57.31   57.34   57.34   57.67
   57.67   57.87   55.57   55.27   54.61   54.49   54.61   54.38   54.58   55.65
 -958.70 -958.42 -957.61 -957.57 -956.77 -955.56 -954.39 -954.20 -953.63 -952.51
 -952.36 -952.52 -952.28 -952.55 -952.46 -952.29 -952.63 -952.36 -952.50 -952.15
 -952.25 -951.96 -952.09 -951.90 -952.05 -951.77 -951.74 -952.04 -951.81 -952.05
 -951.86 -951.92 -951.62 -951.80 -951.56 -951.62 -951.30 -951.41 -951.22 -951.58
 -950.51 -950.11 -949.35 -947.86 -945.39 -943.20 -942.69 -942.66   53.84   54.17
 -942.33 -942.13 -944.43 -944.73 -945.39 -945.51 -945.39 -945.62 -945.42 -944.35
 8182.34 8272.25 8374.77 8405.52 8528.55 8631.08 8706.14 8733.24 8757.22 8859.36
 8910.44 8926.99 8937.18 8977.97 9028.96 9039.16 9069.75 9090.14 9100.34 9141.13
 9222.69 9232.87 9253.24 9263.43 9293.99 9314.36 9334.73 9355.11 9385.66 9395.85
 9406.04 9426.41 9497.52 9517.83 9527.98 9538.14 9548.29 9558.44 9578.75 9588.90
 9599.06 9639.58 9669.90 9690.11 9750.74 9811.37 9890.22 9956.14 9956.1410103.34
10108.1410108.1410195.5310226.0410246.2810256.3910266.5110276.6310286.7510306.05
   41.30   41.58   42.39   42.43   43.23   44.44   45.61   45.80   46.37   47.49
   47.64   47.48   47.72   47.45   47.54   47.71   47.37   47.64   47.50   47.85
   47.75   48.04   48.08   47.91   48.10   47.95   48.23   48.26   47.96   48.19
   47.95   48.14   48.08   48.38   48.20   48.44   48.38   48.70   48.59   48.78
   48.42   49.49   49.89   50.65   52.14   54.61   57.31   57.45   57.45   57.87
   57.76   57.76   55.57   55.27   54.61   54.49   54.61   54.38   54.58   55.65
 -958.70 -958.42 -957.61 -957.57 -956.77 -955.56 -954.39 -954.20 -953.63 -952.51
 -952.36 -952.52 -952.28 -952.55 -952.46 -952.29 -952.63 -952.36 -952.50 -952.15
 -952.25 -951.96 -951.92 -952.09 -951.90 -952.05 -951.77 -951.74 -952.04 -951.81
 -952.05 -951.86 -951.92 -951.62 -951.80 -951.56 -951.62 -951.30 -951.41 -951.22
 -951.58 -950.51 -950.11 -949.35 -947.86 -945.39 -942.69 -942.55   53.95   54.37
   54.26 -942.24 -944.43 -944.73 -945.39 -945.51 -945.39 -945.62 -945.42 -944.35
Pier Skew, UpSta & Num, DnSta & Num=  ,9983.37, 2 ,10032.14, 2 , 0 , 0 , 0 ,,
    4.00    4.00
 -942.49   57.51
    4.00    4.00
 -942.39   57.61
BR Coef=-1 , 0 , 0 ,, 0 ,,,0.8,0,1,0,
WSPro=,,,, 1 ,,,, 0 ,,,, 0 ,,,,-1 ,-1 ,-1 , 0 , 0 , 0 , 0 , 0
BC Design=,, 0 ,, 0 ,,,,,,

Type RM Length L Ch R = 1 ,23325.44,1337.469900,1337.469900,1337.469900
XS GIS Cut Line= 6
 496824.28154553 712667.17579734495915.016065978714403.288055256
496122.424236725715349.587834293496278.983769863716280.247281275
 496290.04662963716509.002741166496364.071866869717029.924969641
#Sta/Elev= 30
6072.939136.49586179.15994.07116 6239.81 85.99876375.27252.740656437.80445.90493
6524.01941.590177526.69840.722977594.42945.28904 7662.1646.045357752.58341.15338
8341.621 41.2318 9443.04 45.99969619.83447.943889666.13250.651029680.11448.03471
9808.09947.629729939.92552.763789970.17538.9419610010.4637.9445310060.8142.33119
10080.9648.6004510111.17 51.914810202.8853.9388210303.8862.0637710354.3862.63254
10505.8975.7710710586.6980.13729 10627.184.47841 10667.596.1991210702.7799.75052
#Mann= 3 , 0 , 0
6072.939   0.044       06072.939   0.044       010702.77   0.044       0
#XS Ineff= 2 , 0
       08881.987                       0
Bank Sta=6072.939,10702.77
Exp/Cntr=0.3,0.1

Type RM Length L Ch R = 1 ,21987.97,241.709900,241.709900,241.709900
XS GIS Cut Line= 6
497526.431230545711638.904254124496430.000199586713157.356895328
  495594.7921803714605.051499799495279.104128838715312.632739291
 495013.35284254716317.429740846 494534.23167944717518.612201259
#Sta/Elev= 30
5254.175323.78155389.288 358.8315500.343348.16575679.279308.39335916.804234.7121
6082.464217.0626 6152.67218.13536251.388184.94486460.134158.01556547.169119.1992
6652.154107.95636836.72653.538296955.52341.082549588.21538.636119915.322 42.1296
9967.80651.0326210010.4333.2341610041.7345.5476910132.2349.4586910182.4268.56261
10489.99142.617110595.13178.437910743.43199.432210786.12217.778911355.16249.3463
11430.82238.011111549.74245.029211690.87225.568811864.64246.623811912.18234.5462
#Mann= 3 , 0 , 0
5254.175    0.04       05254.175    0.04       011912.18    0.04       0
#XS Ineff= 2 , 0
       08892.589                       0
Bank Sta=5254.175,11912.18
Exp/Cntr=0.3,0.1

Type RM Length L Ch R = 1 ,21746.26,241.709900,241.709900,241.709900
XS GIS Cut Line= 6
497274.873230368711698.653718159496257.275040567713096.953510553
495403.468810141714536.614574566495134.706759244715117.612132624
494951.427298248715750.307088673494259.169901609717455.440118313
#Sta/Elev= 30
5253.198374.65155337.149365.85185399.878 350.3545564.909274.87695615.334 259.816
5740.571258.05195903.378231.47256039.876246.26576163.903 216.8196262.563203.0434
6405.193156.47296605.40371.391826690.61653.275246799.65142.020529380.91737.76227
9963.73846.902929998.66731.4977810122.8464.5145410282.0888.0568110452.17139.8583
 10612.2136.770410761.99163.572710869.43161.3706 11009.1175.478111138.53175.6482
11203.36166.881511257.38187.2733 11377.3210.6916 11484.7244.4928 11800.6 319.761
#Mann= 3 , 0 , 0
5253.198  0.0418       05253.198  0.0418       0 11800.6  0.0418       0
#XS Ineff= 2 , 0
       08657.694                       0
Bank Sta=5253.198,11800.6
Exp/Cntr=0.3,0.1

Type RM Length L Ch R = 1 ,21504.55,241.709900,241.709900,241.709900
XS GIS Cut Line= 6
497173.566059411711613.736402258496214.953108549712899.004497543
495346.457003951714292.388453811495013.439559251714962.587250143
494707.202235669715762.349715784494007.586522579 717396.13619107
#Sta/Elev= 30
5252.541415.33075330.444389.40985432.983326.05835508.425302.49575698.971203.1959
5774.595203.49435975.321260.91526051.341264.90226202.893230.94126533.37685.21515
6692.666 54.82346790.32244.945158097.457 35.83259422.07137.094959954.48246.36139
9993.78232.1383210024.3642.7185110119.5644.1519410207.7762.7126110399.9181.95761
10589.6877.7520210892.81113.007910925.29103.970710968.59108.016611066.03146.4516
11174.29 158.43311359.02210.895711456.93  255.0611609.24305.818111883.05351.7354
#Mann= 3 , 0 , 0
5252.541  0.0413       05252.541  0.0413       011883.05  0.0413       0
#XS Ineff= 2 , 0
       08520.038                       0
Bank Sta=5252.541,11883.05
Exp/Cntr=0.3,0.1

Type RM Length L Ch R = 1 ,21262.84,241.709900,241.709900,241.709900
XS GIS Cut Line= 6
497078.701055825711515.227680922496084.127225041712825.178366035
495194.227324724714216.364317074494620.074633271715403.200159997
 494482.13411212715630.929568276493757.635951906717294.916538477
#Sta/Elev= 30
5244.566405.2637 5282.29390.34275314.123356.66025372.809323.24455425.539305.2059
5538.389249.01955640.854224.15185717.261182.8815  5780.8160.62415881.741170.6298
  5995.3204.28396096.042200.61566208.583 178.333  6426.999.082736528.46370.81623
6778.79744.659788239.21335.016659943.30940.40448   1000130.7136910053.17 45.7599
10186.8342.9028710664.69 72.073510817.24108.397410926.34124.297411035.56162.0248
11079.24163.130811472.43279.702611678.53330.150711767.64337.757911942.67329.7777
#Mann= 3 , 0 , 0
5244.566  0.0419       05244.566  0.0419       011942.67  0.0419       0
#XS Ineff= 2 , 0
       08391.396                       0
Bank Sta=5244.566,11942.67
Exp/Cntr=0.3,0.1

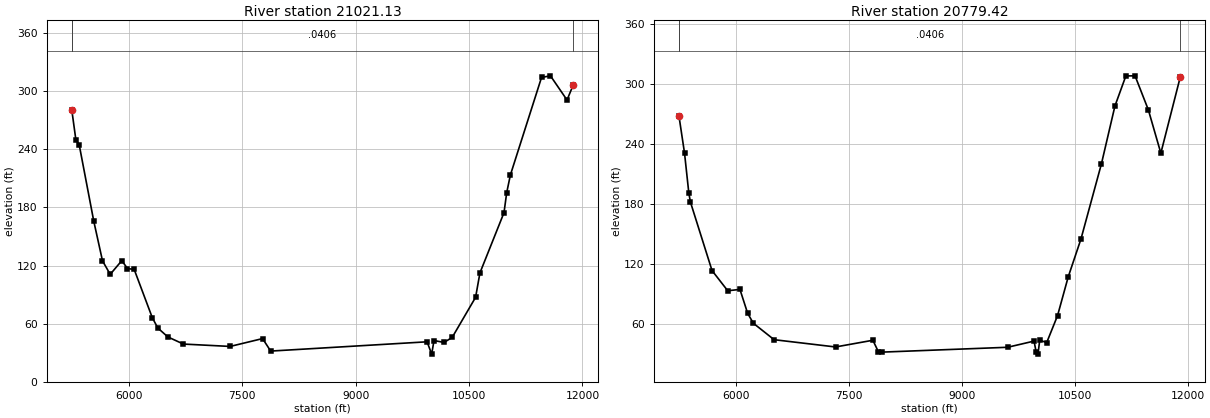
Type RM Length L Ch R = 1 ,21021.13,241.710000,241.710000,241.710000
XS GIS Cut Line= 6
496829.461066723711498.569106951495640.774253458713059.341504827
 494796.39754799714381.961052418494445.489965737 715054.88660723
494216.864896655715840.171745762493593.683288336 717228.52248463
#Sta/Elev= 30
5242.361 280.7195297.092249.54885340.742244.6279 5533.82165.72245649.166124.8888
  5751.2110.89645905.019125.04175980.148116.8711 6068.67 115.9866308.01866.27864
6381.36955.582116514.54246.376396719.79839.052787338.01236.603727767.31444.69596
7874.58331.811719943.80641.3777710004.7428.6737310035.3342.6994310168.5240.73311
10275.8445.89052 10585.787.22477 10643.1112.358410961.63174.504710997.46195.1306
11045.81213.242711458.17313.843311576.22315.509411795.49290.5786 11876.1305.8385
#Mann= 3 , 0 , 0
5242.361  0.0406       05242.361  0.0406       0 11876.1  0.0406       0
#XS Ineff= 2 , 0
       08047.961                       0
Bank Sta=5242.361,11876.1
Exp/Cntr=0.3,0.1

Type RM Length L Ch R = 1 ,20779.42,241.709900,241.709900,241.709900
XS GIS Cut Line= 6
496761.887298673711473.373625219495877.720501095712599.668982387
495068.752965122713766.534878433 494194.04715535715299.763215259
493830.226846933715797.415993512493204.824518949717071.050751582
#Sta/Elev= 30
5240.871267.97735314.879230.7314 5372.22190.4982  5393.8 181.5755679.979113.0909
5888.54692.842916050.88994.192176152.38270.366596228.01160.328476504.53843.80199
7320.27536.514267816.17643.240957887.91931.92433 7935.7131.347079605.44136.20244
9956.69842.400519983.57831.7708810008.8329.33837 10032.143.3020910124.8640.90654
10268.8867.96586 10410.6 106.78110579.94144.764510852.36220.285911030.84277.9571
 11175.9  308.12   11298308.2187 11474.8274.093811640.54230.731811899.57307.3427
#Mann= 3 , 0 , 0
5240.871  0.0406       05240.871  0.0406       011899.57  0.0406       0
#XS Ineff= 2 , 0
       07960.022                       0
Bank Sta=5240.871,11899.57
Exp/Cntr=0.3,0.1