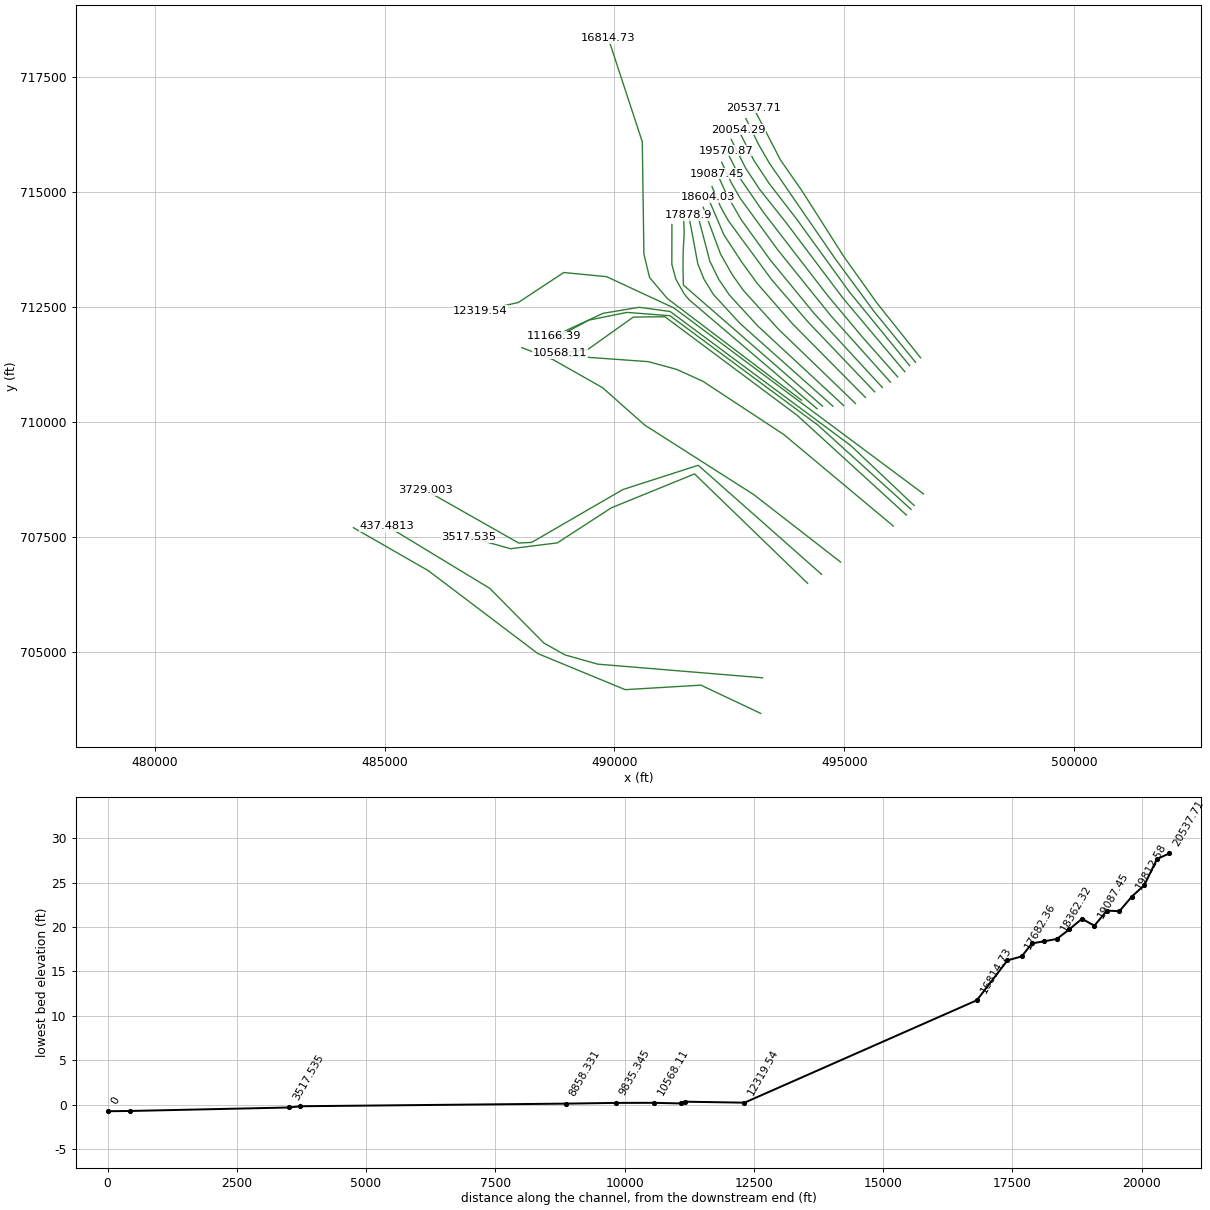
HEC-RAS study 978_ras.prj: 978

--- 978_ras.g01 (geometry) --- (continued)

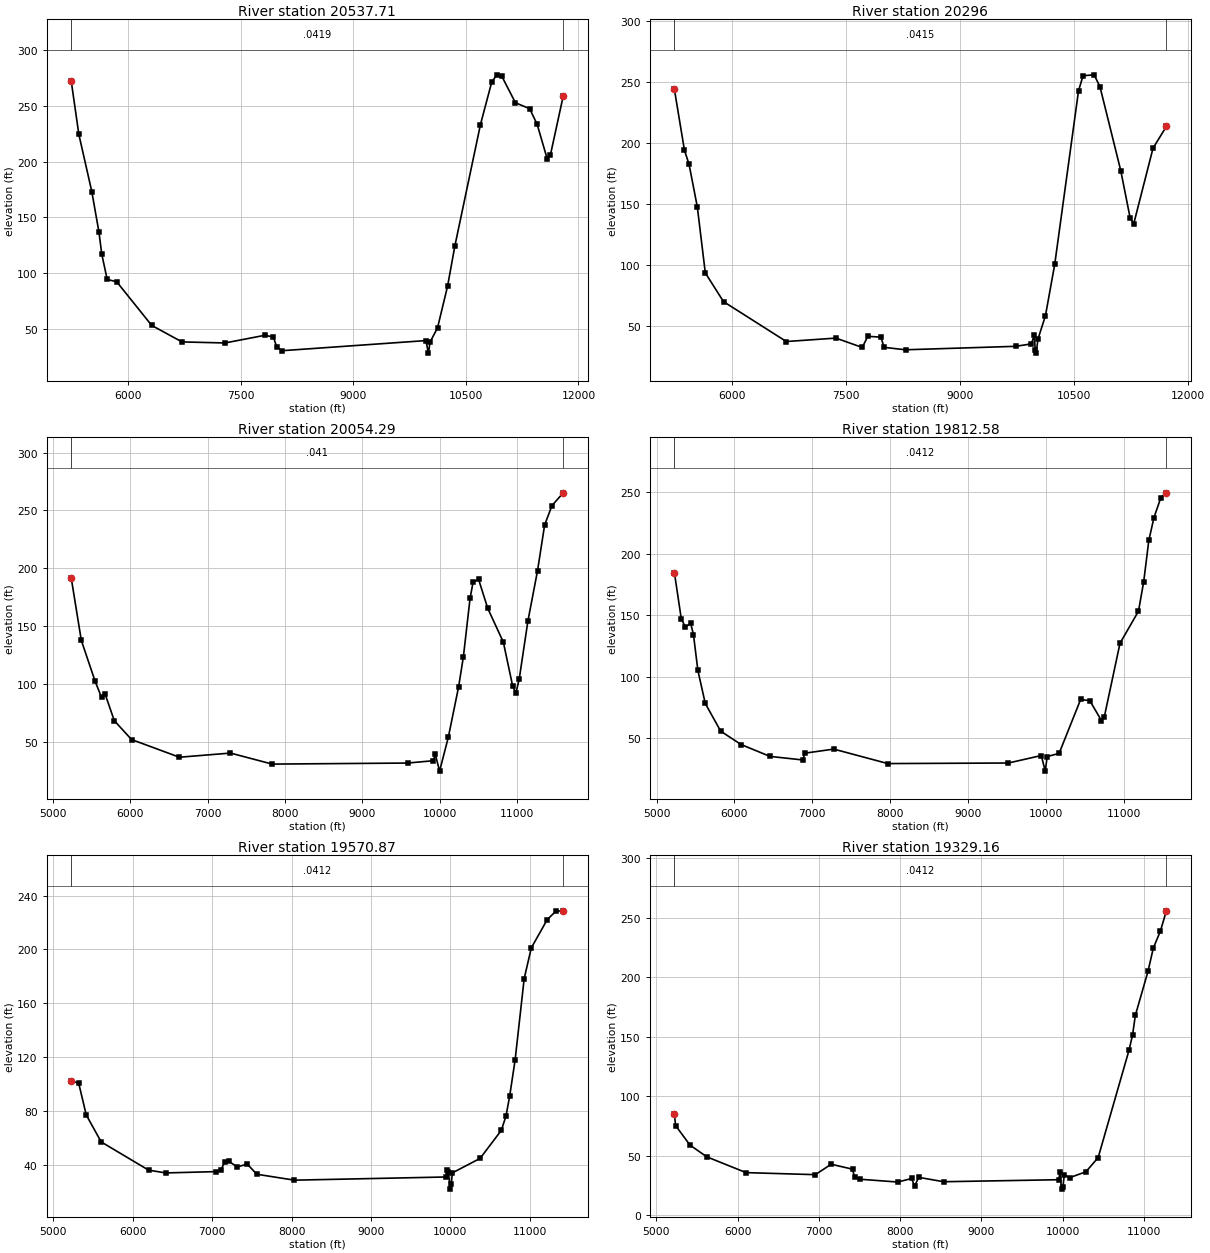
Type RM Length L Ch R = 1 ,20537.71,241.709900,241.709900,241.709900
XS GIS Cut Line= 6
496659.567030758711391.539698794495714.153784126 712577.23335202
 494994.31799984713585.758939847494079.550151646 715022.40220964
493608.421006709715699.182652563493025.485582411716830.069354847
#Sta/Elev= 30
5240.009271.88995341.193224.35325513.577173.13615608.165137.12815646.875116.9303
5718.63594.352965845.69892.237766312.127 53.12646716.11738.328297287.87437.38006
  7825.244.327117934.30942.57479 7976.9534.070588042.86730.416489966.94539.51841
10000.3528.2721710021.8438.1405210121.51 50.943110255.6788.3545810353.01124.4996
10693.86233.247710842.84271.0581 10911.6277.806610975.52276.930811159.88252.7457
11349.89247.444611449.51233.361811582.34202.712111626.61206.082811797.14258.9036
#Mann= 3 , 0 , 0
5240.009  0.0419       05240.009  0.0419       011797.14  0.0419       0
#XS Ineff= 2 , 0
       0  7839.5                       0
Bank Sta=5240.009,11797.14
Exp/Cntr=0.3,0.1

Type RM Length L Ch R = 1 ,   20296,241.709900,241.709900,241.709900
XS GIS Cut Line= 6
496549.922209561711294.143131629495653.279786855712390.343690097
 494792.76072675713558.649833143493368.382649779715628.220571831
493136.219829381716029.772616923492860.389905453716594.218387768
#Sta/Elev= 30
5239.411243.87435371.694193.96775432.469 182.4175541.272147.39255645.90593.43296
5885.76269.842826712.15737.138557364.15339.95341 7710.56  32.296 7784.4541.42116
7955.68140.741057998.81632.362848279.848 30.38059729.60833.218549936.91935.21984
9973.89142.638799986.21630.03825 9998.5427.6337210023.0739.2432610120.91 58.2955
10242.89100.423410556.04242.703610615.66255.0576 10761.1 255.80110837.57246.1839
 11111.8177.226411235.54138.316111282.62133.759711536.18195.672511711.75213.4528
#Mann= 3 , 0 , 0
5239.411  0.0415       05239.411  0.0415       011711.75  0.0415       0
#XS Ineff= 2 , 0
       07716.272                       0
Bank Sta=5239.411,11711.75
Exp/Cntr=0.3,0.1

Type RM Length L Ch R = 1 ,20054.29,241.709900,241.709900,241.709900
XS GIS Cut Line= 6
496419.499774963711222.273067683495105.474666923712830.860986799
493960.902519882714411.821638837493362.831194401715186.547069937
493031.100405455715689.362956837492693.607673705716355.958056718
#Sta/Elev= 30
5238.634191.37555368.514137.67925545.086102.72345629.81388.339195676.76491.16946
 5794.7268.297946017.70752.009916636.07836.725167295.98240.307827835.55630.79064
9584.66631.695399917.70133.704619943.51739.09824    999924.7126710111.6253.99611
10244.83 97.589910306.47123.5516 10392.7173.955210431.44187.923510502.28190.5051
10621.86165.254110822.68136.206810943.8998.0153510984.8492.1666911027.83104.2279
11140.52154.535911264.23 197.73111356.15237.287511450.85254.116211596.96265.1823
#Mann= 3 , 0 , 0
5238.634   0.041       05238.634   0.041       011596.96   0.041       0
#XS Ineff= 2 , 0
       07565.219                       0
Bank Sta=5238.634,11596.96
Exp/Cntr=0.3,0.1

Type RM Length L Ch R = 1 ,19812.58,241.709900,241.709900,241.709900
XS GIS Cut Line= 6
  496316.6587421711088.219252676494974.088701934 712685.20007202
493745.014849573714316.788071886493158.330130577715055.607758373
492857.394904345 715510.78968516492542.145563185716139.583613157
#Sta/Elev= 30
5227.577184.49265316.409146.95175369.618140.19445436.129 143.5655472.723 134.185
5529.244105.20125624.36778.353455822.72955.857736083.88545.031736456.354 35.3655
6878.165 32.48396903.79937.990537275.49241.306777970.32729.555159519.64430.01071
9942.79336.079259993.39723.4236610018.6335.2577410171.69  37.83110448.2581.56786
10566.6680.5966710715.1664.5129810753.2167.6691310954.27127.221311191.47153.2286
11258.41176.949211324.76210.7588 11391.1229.289711479.52245.474111550.19249.3273
#Mann= 3 , 0 , 0
5227.577  0.0412       05227.577  0.0412       011550.19  0.0412       0
#XS Ineff= 2 , 0
       07277.756                       0
Bank Sta=5227.577,11550.19
Exp/Cntr=0.3,0.1

Type RM Length L Ch R = 1 ,19570.87,241.709900,241.709900,241.709900
XS GIS Cut Line= 6
496162.011020571710974.790750369495405.537827879711827.622282922
494631.490043998712753.580336049493243.806949824714551.412430555
492755.739035904715262.475742295492436.542144209715898.546196744
#Sta/Elev= 30
 5227.15102.45125321.504100.36255415.57876.935235603.72456.874586201.16335.86784
6416.29233.81473 7045.88 34.78117110.99935.821147157.35541.903097214.49542.33846
7315.50338.264377442.021 40.39477563.01432.826298035.87128.433629949.42630.80219
9961.89136.129549974.35534.145819999.28321.7679510010.8825.6655510024.0633.84905
10373.4744.6080410640.7865.4672110699.38 76.054110745.5490.8271410814.51117.8646
10928.56178.296311018.35201.147111218.67222.160611328.92228.481611420.25228.6825
#Mann= 3 , 0 , 0
 5227.15  0.0412       0 5227.15  0.0412       011420.25  0.0412       0
#XS Ineff= 2 , 0
       07214.456                       0
Bank Sta=5227.15,11420.25
Exp/Cntr=0.3,0.1

Type RM Length L Ch R = 1 ,19329.16,241.709900,241.709900,241.709900
XS GIS Cut Line= 6
496004.952396631710860.131695554494712.947243989712299.641640007
493552.688417673713739.494423002492732.912734598714864.514654145
492544.787400186715193.093050316 492333.90125221715641.943966731
#Sta/Elev= 30
5223.84584.611055238.53975.272565415.70958.849995622.40748.970496105.48135.71558
6957.07333.993657152.09142.757057414.55438.619517440.58831.751387505.67330.15487
7972.22527.796638142.08530.803578177.78824.262888228.73331.75049  8534.428.05509
9951.84329.748149965.58836.01397 9985.5821.8388610002.8324.0388410019.5433.70962
10088.8331.5487610285.36 36.418210435.6848.30469 10814.6138.388310859.42151.5129
10893.04167.816411048.55204.818511114.29224.413211201.95238.817111274.91255.7474
#Mann= 3 , 0 , 0
5223.845  0.0412       05223.845  0.0412       011274.91  0.0412       0
#XS Ineff= 2 , 0
       07147.775                       0
Bank Sta=5223.845,11274.91
Exp/Cntr=0.3,0.1

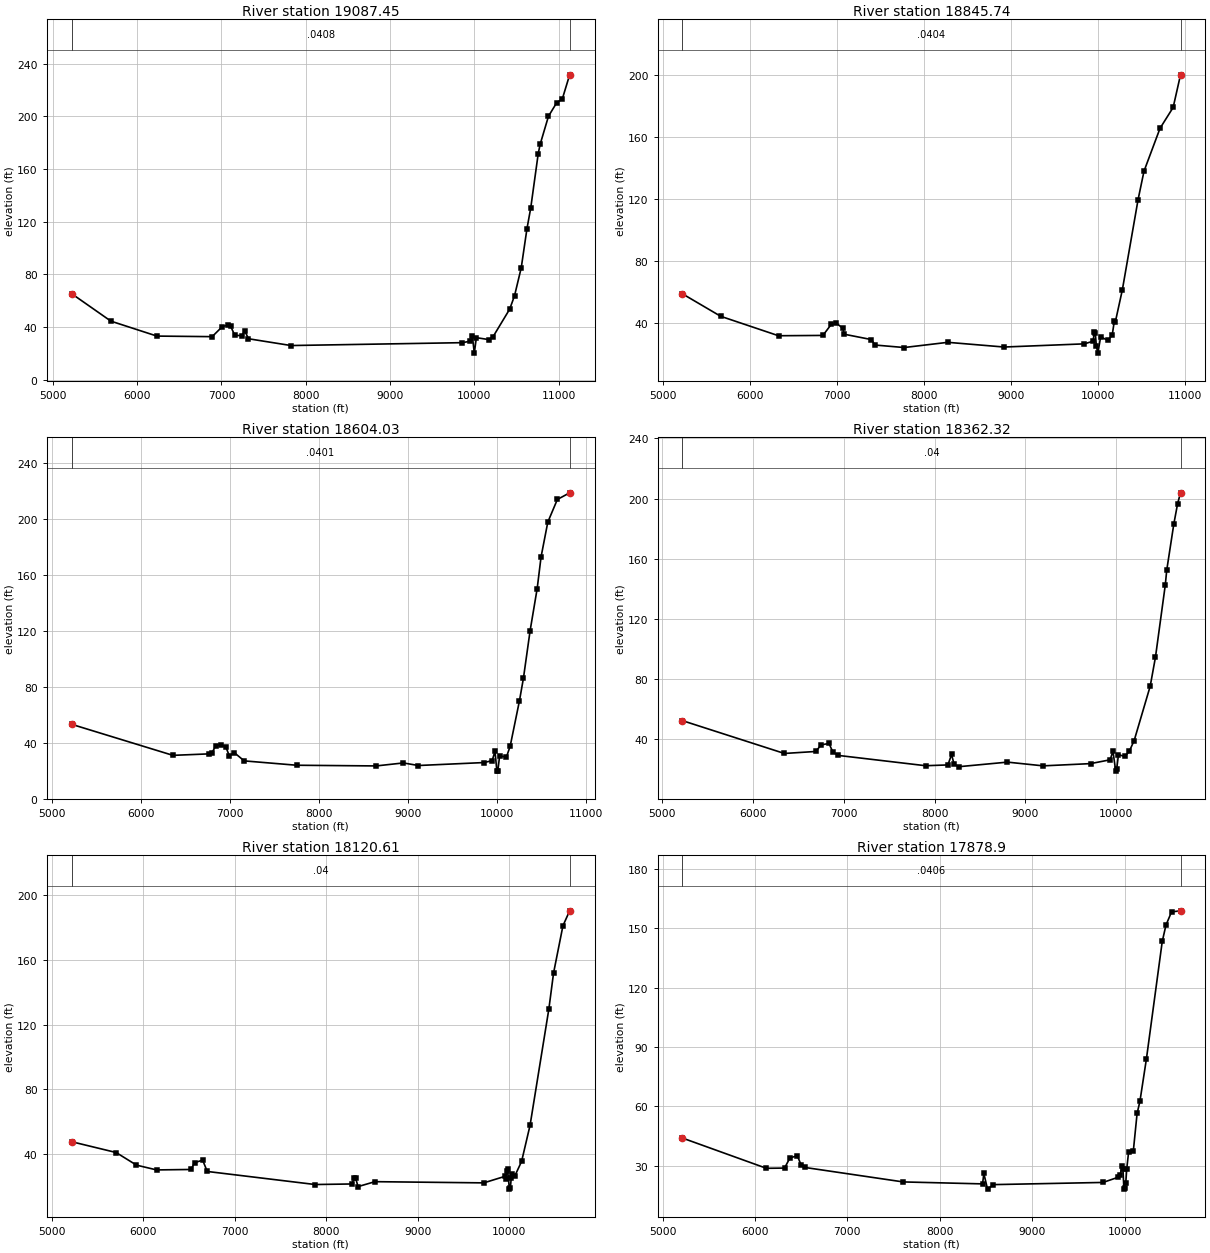
Type RM Length L Ch R = 1 ,19087.45,241.710000,241.710000,241.710000
XS GIS Cut Line= 6
495828.661526442710745.965152442494345.424866587712353.273023054
493385.807250082713523.826571718492756.544885248714397.061138377
492435.381158024714953.726251081492235.433039933715395.773436055
#Sta/Elev= 30
5223.16265.322865689.89744.420446235.27533.089736889.98232.653177011.03140.31744
7077.97941.446027110.28640.409467158.31633.727667238.65333.372467278.82136.80387
7320.81631.059177825.23225.908619856.78428.088649951.398 29.21289974.98733.29433
9998.57620.1452410023.1231.8927710174.2730.38284 10220.832.6031810418.2353.57299
10475.37 63.674310555.0684.9555910622.74114.544310667.56130.335410756.67171.7254
10778.95178.625510878.02200.041410976.31210.401311041.76213.093711129.16231.5014
#Mann= 3 , 0 , 0
5223.162  0.0408       05223.162  0.0408       011129.16  0.0408       0
#XS Ineff= 2 , 0
       07068.571                       0
Bank Sta=5223.162,11129.16
Exp/Cntr=0.3,0.1

Type RM Length L Ch R = 1 ,18845.74,241.709900,241.709900,241.709900
XS GIS Cut Line= 6
495661.428541243710650.339571729494210.537915617 712171.30271548
493419.210238308713091.362772778492478.479741782714372.707131982
492305.364039302 714683.32137084492122.642986327715113.798302025
#Sta/Elev= 30
5222.50459.077995662.653 44.62066327.67132.109976838.36532.308016934.00539.38937
6994.588 40.21427068.09636.812727082.79833.090577397.07629.62744 7437.0226.12656
7772.753 24.51698275.315 27.86658922.04524.841299846.75926.886099945.30728.58278
 9962.0734.643039971.35733.957289983.817 25.4418   1000120.9160410033.4931.43411
10116.6129.0591410166.2732.5976610189.8541.2950910201.6540.8905610282.5561.59471
10463.48119.6515 10531.7137.991410716.04165.585610867.25179.060810951.79200.0233
#Mann= 3 , 0 , 0
5222.504  0.0404       05222.504  0.0404       010951.79  0.0404       0
#XS Ineff= 2 , 0
       06985.642                       0
Bank Sta=5222.504,10951.79
Exp/Cntr=0.3,0.1

Type RM Length L Ch R = 1 ,18604.03,241.709900,241.709900,241.709900
XS GIS Cut Line= 6
495457.715740114710530.712678507493869.876468748712134.314810276
493111.650920391713001.765190527492773.897324413713466.773189396
492382.253134966714063.735226944492031.197228134 714885.18390651
#Sta/Elev= 30
5221.93453.252876360.32331.028256767.65732.093076796.08132.52336 6839.2837.70296
6896.00938.638486953.11137.223576993.41730.68465 7049.31 32.95837160.37127.07051
7749.78823.947368642.26723.455248947.49125.598499116.02523.761919850.53625.86616
9944.17727.192989976.541 33.88999997.44919.9416210007.8519.7394610028.6630.61951
10104.8729.7730610147.3637.6811310250.8769.9487610295.7986.1652410370.71120.1747
10450.34150.407810494.09173.116610569.52197.909510676.77214.143110814.95218.8915
#Mann= 3 , 0 , 0
5221.934  0.0401       05221.934  0.0401       010814.95  0.0401       0
#XS Ineff= 2 , 0
       06885.967                       0
Bank Sta=5221.934,10814.95
Exp/Cntr=0.3,0.1

Type RM Length L Ch R = 1 ,18362.32,241.709900,241.709900,241.709900
XS GIS Cut Line= 6
 495243.64762032710397.069797933493561.670872092712019.897068724
 492801.85821119712861.243992776492562.793557584713198.907205552
492309.397828579713646.035368875491930.216988206714665.468764424
#Sta/Elev= 30
5220.494 52.24026344.29330.407776690.99731.738646748.78136.110146835.457 37.0769
6878.79531.397586937.17329.114577900.39922.254728146.69922.774838187.08229.72202
8214.005 23.4327 8264.9121.589288803.15224.643629196.71322.162019718.79623.64862
9934.91426.19476 9965.92 31.95059996.43718.6540910006.5619.8184810026.8429.62409
10096.5228.4115810144.9831.7209710199.81 39.005710376.6575.2086710434.62 94.5186
10542.55142.399810558.97152.442510637.09183.182610678.83196.663110710.63203.8368
#Mann= 3 , 0 , 0
5220.494    0.04       05220.494    0.04       010710.63    0.04       0
#XS Ineff= 2 , 0
       0 6786.43                       0
Bank Sta=5220.494,10710.63
Exp/Cntr=0.3,0.1

Type RM Length L Ch R = 1 ,18120.61,241.709900,241.709900,241.709900
XS GIS Cut Line= 6
 494985.01825434710353.579300433493119.664161861712082.256677151
492498.681791157712759.354255661492265.411680192713103.749884546
492074.023687482713497.199863449491788.574185908714586.641465753
#Sta/Elev= 30
 5215.6347.668395702.71140.992015925.01933.207926145.31430.245956522.09530.52512
6559.53134.698496648.29136.294636698.50429.301687877.84821.231188279.76821.57564
  8306.625.389878320.01625.272848346.849 19.94938531.782 22.99339721.32222.25202
9949.796 26.23249960.08224.354089970.36829.705789980.65530.7472710001.2218.39067
 10011.519.0314810021.7725.4619610032.0527.8867710062.8826.7979910134.8135.53222
 10227.357.8598110432.76129.654410484.04151.837410586.61180.976710659.88190.1906
#Mann= 3 , 0 , 0
 5215.63    0.04       0 5215.63    0.04       010659.88    0.04       0
#XS Ineff= 2 , 0
       06595.106                       0
Bank Sta=5215.63,10659.88
Exp/Cntr=0.3,0.1

Type RM Length L Ch R = 1 , 17878.9,196.543600,196.543600,196.543600
XS GIS Cut Line= 6
494752.028049916710338.634923965492733.221835613712136.795667782
492154.338152617712766.966206655 491950.72037378713096.545531139
491814.392613351713433.544647276  491617.1153979714491.220922872
#Sta/Elev= 30
5215.13443.986276123.82828.688386320.171 28.80276377.68733.87906 6457.7535.08688
6501.54930.17017 6537.5829.134577603.99821.797568463.19320.80493 8476.5926.09225
8516.77918.154268580.71520.435749766.78521.538229930.88624.171289951.39925.09168
9971.91129.633869982.16828.275539992.424 18.168610002.6818.5852410012.9321.50438
10023.1828.4128610043.68 37.050710094.5937.5094210135.2356.4389810165.5562.48289
10236.2584.0672410407.46143.439810447.74 151.69310508.17158.395610605.07158.9144
#Mann= 3 , 0 , 0
5215.134  0.0406       05215.134  0.0406       010605.07  0.0406       0
#XS Ineff= 2 , 0
       06413.373                       0
Bank Sta=5215.134,10605.07
Exp/Cntr=0.3,0.1

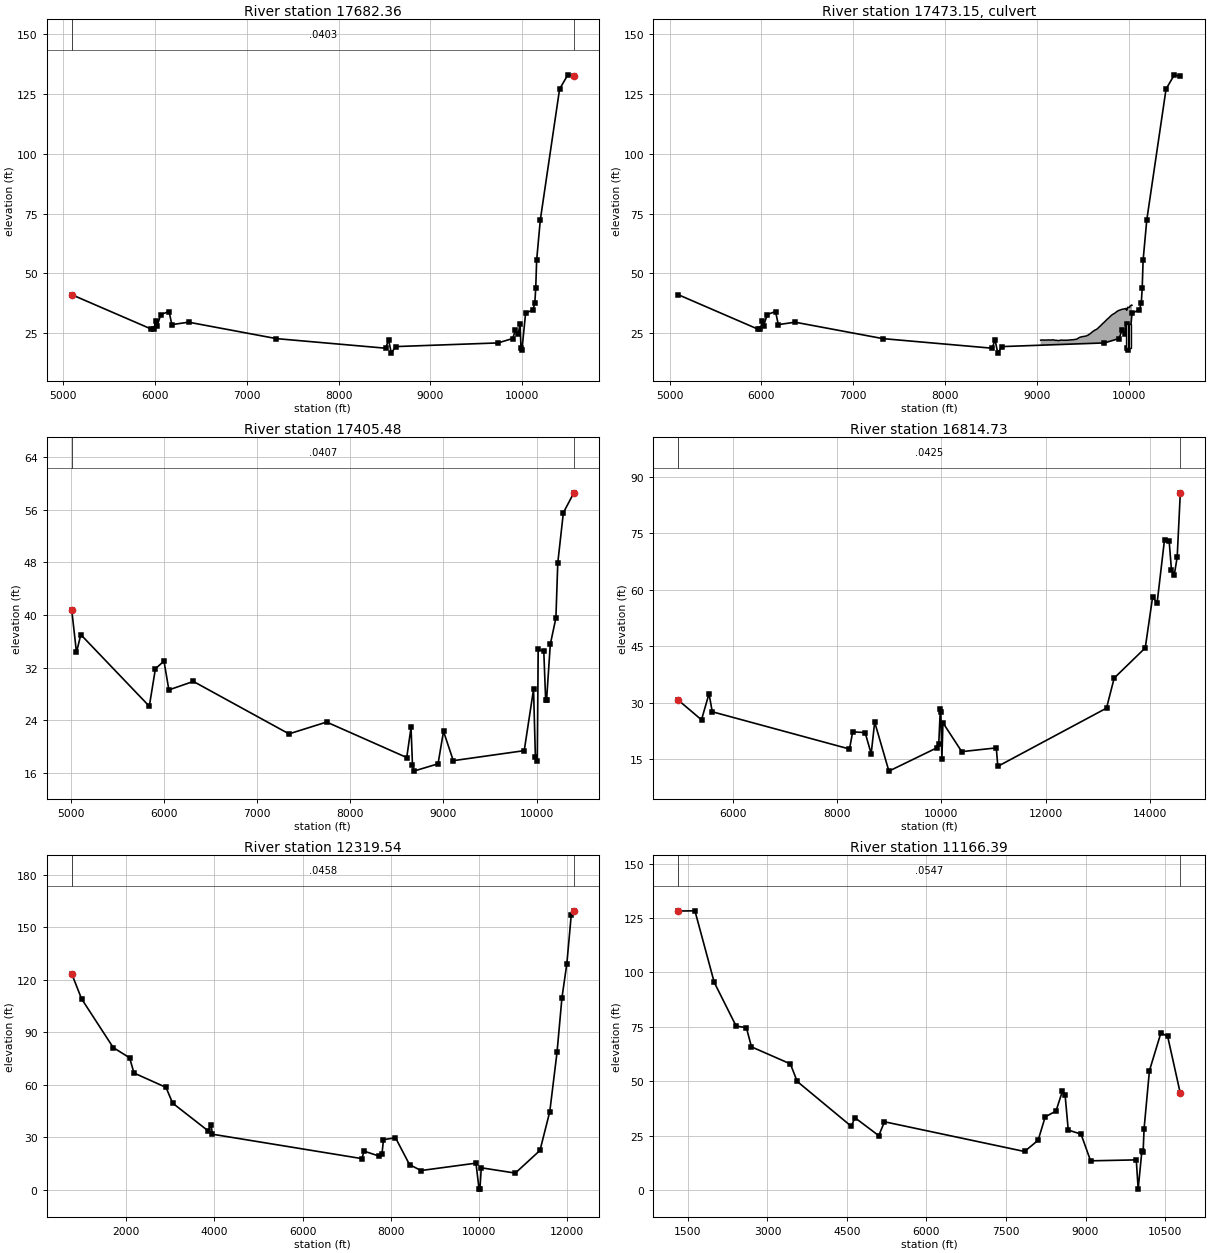
Type RM Length L Ch R = 1 ,17682.36,276.876100,276.876100,276.876100
XS GIS Cut Line= 6
494526.513557822710339.081390649491500.952097207712973.098607183
491491.330642253 713355.40727073491497.116162896713728.437531158
491517.176064432714093.076113537491507.284009963714430.097367838
#Sta/Elev= 30
5093.98241.118155957.80226.79017 5986.3126.690516010.83730.064636024.09528.11093
6063.87132.818466153.83534.086276184.29428.612936367.04929.618027323.44522.75329
8514.41718.739518544.87622.268168575.33516.688688621.02419.422139737.52620.95649
9897.56422.801979927.58226.304249957.74724.816549977.86228.852229987.92918.82984
9997.99317.96476 10038.233.4420110118.3334.7523210138.33 37.668510148.3343.72447
10158.3355.5306910198.3472.3805410408.38127.115810498.43133.040110563.62132.3739
#Mann= 3 , 0 , 0
5093.982  0.0403       05093.982  0.0403       010563.62  0.0403       0
#XS Ineff= 2 , 0
       0 6108.95        10057.92       0
Bank Sta=5093.982,10563.62
Exp/Cntr=0.3,0.1

Type RM Length L Ch R = 2 ,17473.15,,,
Bridge Culvert--1,0,-1,-1, 0
Deck Dist Width WeirC Skew NumUp NumDn MinLoCord MaxHiCord MaxSubmerge Is_Ogee
103.438,70,2.6,0,115,115, , , 0.95, 0, 0,0,,
 9042.06 9048.85 9058.85 9068.85 9078.86 9088.86 9098.86 9108.86 9118.86 9128.86
 9138.86 9148.86 9158.86 9168.86 9178.86 9188.86 9198.86 9208.86 9218.86 9228.86
 9238.86 9248.86 9258.87 9268.87 9278.87 9288.87 9298.87 9308.87 9318.87 9328.87
 9338.87 9348.87 9358.87 9368.87 9378.87 9388.87 9398.87 9408.87 9418.87 9428.87
 9438.88 9448.88 9458.88 9468.88 9478.88 9488.88 9498.88 9508.88 9518.88 9528.88
 9538.88 9548.88 9558.88 9568.88 9578.88 9588.88 9598.88 9608.88 9618.89 9628.89
 9638.89 9648.89 9658.89 9668.89 9678.89 9688.89 9698.89 9708.89 9718.89 9728.89
 9738.89 9748.89 9758.89 9762.66 9769.11 9779.47 9789.82 9800.18 9800.96 9810.53
 9818.15 9821.85 9826.06 9835.85 9840.36 9849.84 9854.65 9863.84 9868.95 9877.83
 9883.24 9891.82 9894.75 9896.98 9908.40 9911.13 9919.82 9931.24 9931.84 9942.66
 9952.55 9954.08 9965.16 9966.02 9969.32 9979.98 9983.57 9990.2010000.2010010.20
10016.4210020.9610024.5910032.9810037.20
   22.10   22.15   22.20   22.18   22.12   22.17   22.13   22.16   22.18   22.21
   22.17   22.17   22.19   22.25   22.22   22.20   22.06   22.03   22.03   21.97
   21.91   21.99   22.13   22.14   22.10   22.09   22.09   22.06   22.11   22.07
   22.12   22.16   22.18   22.22   22.28   22.27   22.32   22.37   22.45   22.48
   22.61   22.85   23.14   23.29   23.41   23.55   23.60   23.63   23.74   23.79
   23.85   24.07   24.19   24.50   24.75   25.03   25.40   25.68   25.93   26.24
   26.41   26.58   26.85   27.22   27.59   27.92   28.32   28.69   29.10   29.38
   29.79   30.15   30.54   30.70   30.95   31.27   31.62   32.03   32.06   32.40
   32.65   32.76   32.88   33.08   33.19   33.41   33.53   33.83   33.98   34.21
   34.34   34.50   34.57   34.60   34.72   34.74   34.90   35.03   35.04   35.10
   35.19   35.20   35.30   35.31   35.38   34.61   35.17   35.85   35.80   35.75
   36.35   36.54   36.57   36.82   36.69
                                                                                
                                                                                
                                                                                
                                                                                
                                                                                
                                                                                
                                                                                
                                                                                
                                                                                
                                                                                
                                                                                
                                        
 9042.06 9048.85 9058.85 9068.85 9078.86 9088.86 9098.86 9108.86 9118.86 9128.86
 9138.86 9148.86 9158.86 9168.86 9178.86 9188.86 9198.86 9208.86 9218.86 9228.86
 9238.86 9248.86 9258.87 9268.87 9278.87 9288.87 9298.87 9308.87 9318.87 9328.87
 9338.87 9348.87 9358.87 9368.87 9378.87 9388.87 9398.87 9408.87 9418.87 9428.87
 9438.88 9448.88 9458.88 9468.88 9478.88 9488.88 9498.88 9508.88 9518.88 9528.88
 9538.88 9548.88 9558.88 9568.88 9578.88 9588.88 9598.88 9608.88 9618.89 9628.89
 9638.89 9648.89 9658.89 9668.89 9678.89 9688.89 9698.89 9708.89 9718.89 9728.89
 9738.89 9748.89 9758.89 9762.66 9769.11 9779.47 9789.82 9800.18 9800.96 9810.53
 9818.15 9821.85 9826.06 9835.85 9840.36 9849.84 9854.65 9863.84 9868.95 9877.83
 9883.24 9891.82 9894.75 9896.98 9908.40 9911.13 9919.82 9931.24 9931.84 9942.66
 9952.55 9954.08 9965.16 9966.02 9969.32 9979.98 9983.57 9990.2010000.2010010.20
10016.4210020.9610024.5910032.9810037.20
   22.10   22.15   22.20   22.18   22.12   22.17   22.13   22.16   22.18   22.21
   22.17   22.17   22.19   22.25   22.22   22.20   22.06   22.03   22.03   21.97
   21.91   21.99   22.13   22.14   22.10   22.09   22.09   22.06   22.11   22.07
   22.12   22.16   22.18   22.22   22.28   22.27   22.32   22.37   22.45   22.48
   22.61   22.85   23.14   23.29   23.41   23.55   23.60   23.63   23.74   23.79
   23.85   24.07   24.19   24.50   24.75   25.03   25.40   25.68   25.93   26.24
   26.41   26.58   26.85   27.22   27.59   27.92   28.32   28.69   29.10   29.38
   29.79   30.15   30.54   30.70   30.95   31.27   31.62   32.03   32.06   32.40
   32.65   32.76   32.88   33.08   33.19   33.41   33.53   33.83   33.98   34.21
   34.34   34.50   34.57   34.60   34.72   34.74   34.90   35.03   35.04   35.10
   35.19   35.20   35.30   35.31   35.38   34.61   35.17   35.85   35.80   35.75
   36.35   36.54   36.57   36.82   36.69
                                                                                
                                                                                
                                                                                
                                                                                
                                                                                
                                                                                
                                                                                
                                                                                
                                                                                
                                                                                
                                                                                
                                        
BR Coef=-1 , 0 , 0 ,, 0 ,,,0.8,-1,,0,
WSPro=,,,, 1 ,,,, 0 ,,,, 0 ,,,,-1 ,-1 ,-1 , 0 , 0 , 0 , 0 , 0
Multiple Barrel Culv=2,10,17,70,0.013,0.5,1,10,2,18.9,17.8,2,Culvert #1, 0, 103.438
 9983.00 9983.0010017.0010017.00
Culvert Bottom n=0.013
BC Design=,, 0 ,, 0 ,,,,,,

Type RM Length L Ch R = 1 ,17405.48,590.755300,590.755300,590.755300
XS GIS Cut Line= 6
494408.938208312710282.126384944491620.498599887712657.185458481
491514.082341403712786.451829195491336.605430216713099.768940523
491249.208397418713426.296389982491250.912715584714287.421169236
#Sta/Elev= 30
5008.04340.695395058.74134.307065105.00737.013065840.76926.113565906.44731.81885
5998.39832.989446050.94128.599116313.65629.892987341.20321.910557745.45423.70966
8605.81118.310758652.07722.883178667.49917.20345 8681.35 16.2429 8942.2717.35613
9000.73122.302219105.878 17.8348 9867.8219.358139967.84528.681189987.85818.33131
10007.88 17.709410017.8934.7813710077.9534.4637310097.9827.0450410107.9927.09679
10148.03 35.548210208.1139.5471810228.1347.92372 10288.255.5612410400.7658.58717
#Mann= 3 , 0 , 0
5008.043  0.0407       05008.043  0.0407       010400.76  0.0407       0
#XS Ineff= 2 , 0
       05961.541        10048.52       0
Bank Sta=5008.043,10400.76
Exp/Cntr=0.3,0.1

Type RM Length L Ch R = 1 ,16814.73,4495.185400,4495.185400,4495.185400
XS GIS Cut Line= 6
494068.244066558710469.969642797491150.026479512712681.127872747
490765.394064031 713136.25831981490641.864587169713647.851156642
490606.550016827716088.111857781489868.101662164 718339.16700326
#Sta/Elev= 30
4958.15730.651975403.97425.412095547.59732.366215610.09927.554128238.579 17.6409
8300.01722.209748537.71822.013368654.28816.369918720.83324.821928993.58111.75839
9908.37117.934269948.37719.047029978.38128.195629988.38327.4324510008.4115.11711
10028.4424.6240510389.1816.9410711050.1217.9443411080.1313.03311 13161.828.52285
13308.6636.5183313903.8344.5502514044.4758.0428614131.3756.5495614272.9673.39117
14361.2273.0788614405.35 65.352514460.5164.0158714515.67 68.737814575.4385.81442
#Mann= 3 , 0 , 0
4958.157  0.0425       04958.157  0.0425       014575.43  0.0425       0
#XS Ineff= 2 , 0
       05524.702        10640.55       0
Bank Sta=4958.157,14575.43
Exp/Cntr=0.3,0.1

Type RM Length L Ch R = 1 ,12319.54,1153.149500,1153.149500,1153.149500
XS GIS Cut Line= 6
496722.642632931708431.180344597491292.916896909712475.447876677
489830.466225147713155.493407682488898.671455801713245.504601762
487910.782520622712594.237846792487086.776082188 712409.77902551
#Sta/Elev= 30
769.6991 123.401991.8193109.12721708.89681.254712079.64775.383472179.67766.67253
2904.89558.46124 3054.9449.445973857.74733.616243924.37837.147043957.69331.64805
7342.40717.695017393.78821.991167736.43519.088967799.21720.473317833.03128.53526
8104.917 29.64228423.524 14.24028682.68210.872829928.61315.100169998.7120.235665
10018.740.56116410048.93 12.441910820.37 9.4162811378.9922.3756811601.0744.56936
11765.4678.5741311876.99109.784111987.78 129.21912088.08157.2799 12146.4159.4863
#Mann= 3 , 0 , 0
769.6991  0.0458       0769.6991  0.0458       0 12146.4  0.0458       0
#XS Ineff= 2 , 0
       04682.065        10410.48       0
Bank Sta=769.6991,12146.4
Exp/Cntr=0.3,0.1

Type RM Length L Ch R = 1 ,11166.39,78.387500,78.387500,78.387500
XS GIS Cut Line= 6
496518.527067602708178.587332487495137.790954053709484.750823647
491213.407400906712397.399415478490541.453486741712489.728960916
489754.942544013712358.073868349488677.352314562711858.004704773
#Sta/Elev= 30
1317.975128.23921632.887128.32991997.34195.388792410.307 75.31522603.02574.60109
2699.38365.76732  3432.757.938693562.37349.854144583.16929.21501 4648.9133.21569
5099.68324.938775207.70931.32301 7848.9217.653548104.96922.81337 8239.3933.58922
8442.70536.254948563.08745.362538613.24643.848568673.43727.519248914.43625.64585
9094.94413.363229956.70513.798339991.9980.348439   1006217.7776410085.4717.45235
10103.9428.2019610204.6554.8292910420.6172.1351510547.9270.6344410787.0344.37521
#Mann= 3 , 0 , 0
1317.975  0.0547       01317.975  0.0547       010787.03  0.0547       0
#XS Ineff= 2 , 0
       05230.598                       0
Bank Sta=1317.975,10787.03
Exp/Cntr=0.3,0.1

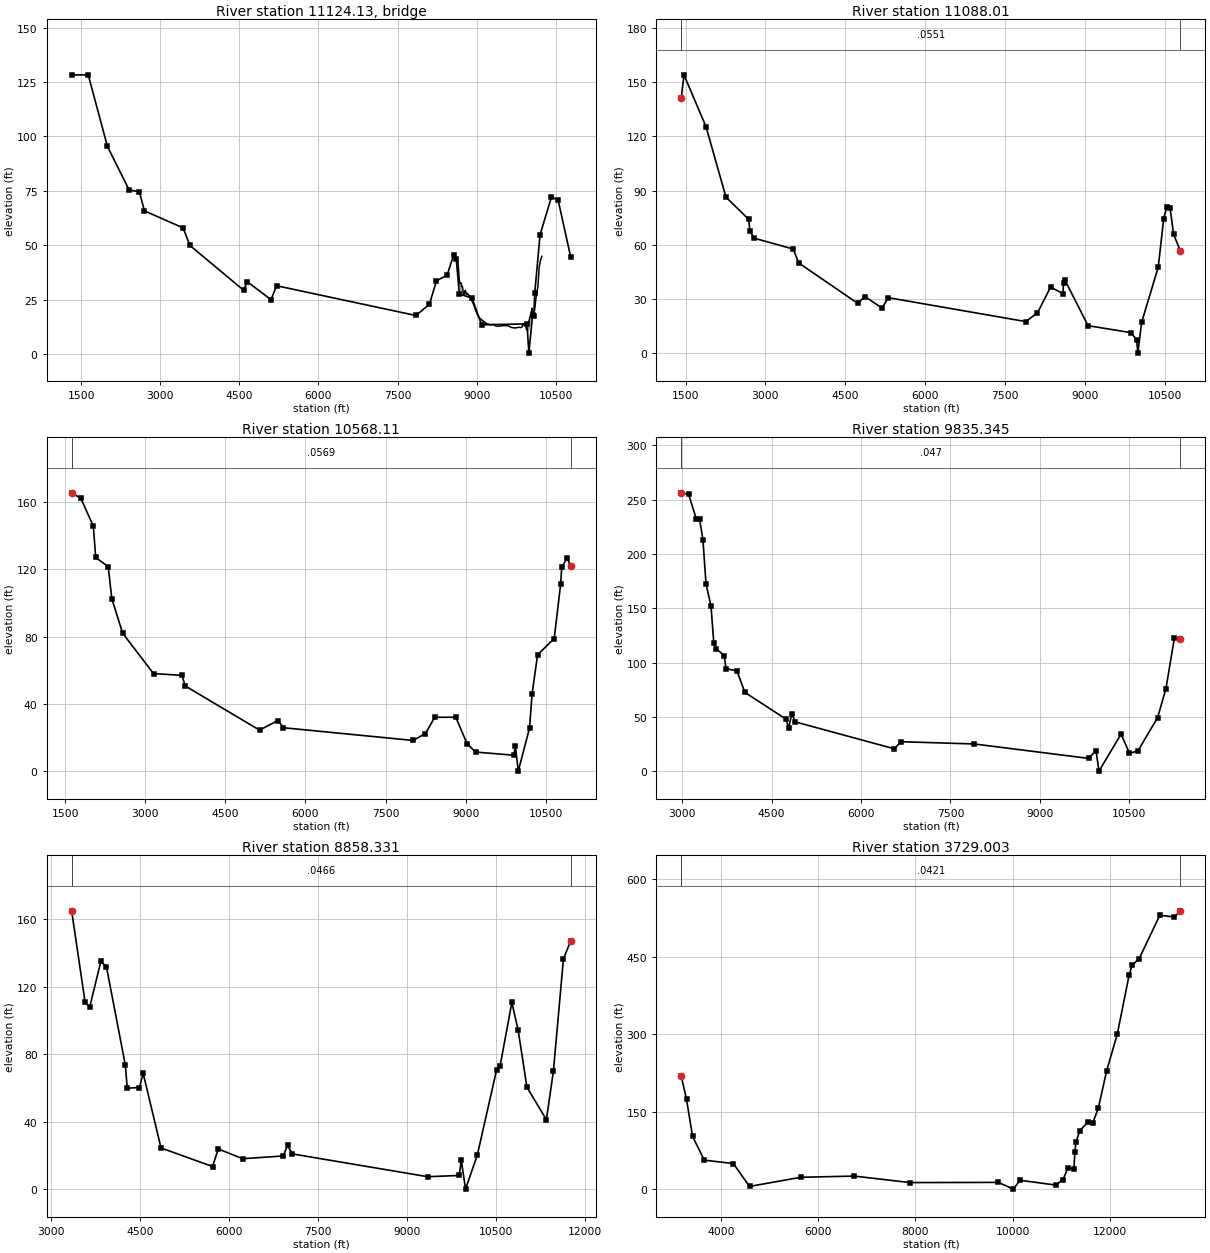
Type RM Length L Ch R = 3 ,11124.13,,,
BEGIN DESCRIPTION:
END DESCRIPTION:
Bridge Culvert--1,0,-1,-1, 0
Deck Dist Width WeirC Skew NumUp NumDn MinLoCord MaxHiCord MaxSubmerge Is_Ogee
22.943750,32.500000,2.6,0, 60, 60, , , 0.95, 0, 0,0,,
 8608.97 8627.59 8647.60 8667.61 8677.62 8687.63 8697.64 8707.64 8717.65 8727.66
 8737.66 8747.67 8757.68 8777.69 8787.70 8797.71 8807.71 8827.73 8837.73 8867.76
 8887.77 8907.82 8927.87 8957.95 8978.01 9028.14 9068.68 9201.51 9221.89 9242.28
 9323.82 9354.40 9405.37 9530.15 9599.03 9659.96 9720.85 9822.33 9832.47 9852.79
 9863.00 9883.44 9893.65 9903.87 9924.65 9951.06 9962.37 9962.3710045.3710045.37
10054.9810079.2310091.3610103.4910127.7410139.8710164.1210188.3710210.1610237.78
   44.03   43.56   42.47   35.34   33.04   32.42   32.72   32.44   30.97   31.15
   29.96   27.63   27.22   28.93   29.22   28.02   27.35   27.89   27.37   26.64
   25.78   24.41   23.60   21.85   20.31   17.50   16.21   13.72   13.81   13.38
   13.48   12.87   12.68   13.07   12.86   12.17   11.91   12.26   12.08   12.18
   12.54   13.93   13.84   12.96   13.24   10.99   12.07   12.07   19.97   19.97
   21.01   18.85   19.08   20.74   25.91   27.42   31.19   40.03   42.85   44.86
 -955.97 -956.44 -957.53 -964.66 -966.96 -967.58 -967.28 -967.56 -969.03 -968.85
 -970.04 -972.37 -972.78 -971.07 -970.78 -971.98 -972.65 -972.11 -972.63 -973.36
 -974.22 -975.59 -976.40 -978.15 -979.69 -982.50 -983.79 -986.28 -986.19 -986.62
 -986.52 -987.13 -987.32 -986.93 -987.14 -987.83 -988.09 -987.74 -987.92 -987.82
 -987.46 -986.07 -986.16 -987.04 -986.76 -989.01 -987.93    7.07   14.97 -980.03
 -978.99 -981.15 -980.92 -979.26 -974.09 -972.58 -968.81 -959.97 -957.15 -955.14
 8608.97 8627.59 8647.60 8667.61 8677.62 8687.63 8697.64 8707.64 8717.65 8727.66
 8737.66 8747.67 8757.68 8777.69 8787.70 8797.71 8807.71 8827.73 8837.73 8867.76
 8887.77 8907.82 8927.87 8957.95 8978.01 9028.14 9068.68 9201.51 9221.89 9242.28
 9323.82 9354.40 9405.37 9530.15 9599.03 9659.96 9720.85 9822.33 9832.47 9852.79
 9863.00 9883.44 9893.65 9903.87 9924.65 9951.06 9958.04 9958.0410041.0410041.04
10054.9810079.2310091.3610103.4910127.7410139.8710164.1210188.3710210.1610237.78
   44.03   43.56   42.47   35.34   33.04   32.42   32.72   32.44   30.97   31.15
   29.96   27.63   27.22   28.93   29.22   28.02   27.35   27.89   27.37   26.64
   25.78   24.41   23.60   21.85   20.31   17.50   16.21   13.72   13.81   13.38
   13.48   12.87   12.68   13.07   12.86   12.17   11.91   12.26   12.08   12.18
   12.54   13.93   13.84   12.96   13.24   10.99   11.66   11.66   19.55   19.55
   21.01   18.85   19.08   20.74   25.91   27.42   31.19   40.03   42.85   44.86
 -955.97 -956.44 -957.53 -964.66 -966.96 -967.58 -967.28 -967.56 -969.03 -968.85
 -970.04 -972.37 -972.78 -971.07 -970.78 -971.98 -972.65 -972.11 -972.63 -973.36
 -974.22 -975.59 -976.40 -978.15 -979.69 -982.50 -983.79 -986.28 -986.19 -986.62
 -986.52 -987.13 -987.32 -986.93 -987.14 -987.83 -988.09 -987.74 -987.92 -987.82
 -987.46 -986.07 -986.16 -987.04 -986.76 -989.01 -988.34    6.66   14.55 -980.45
 -978.99 -981.15 -980.92 -979.26 -974.09 -972.58 -968.81 -959.97 -957.15 -955.14
BR Coef=-1 , 0 , 0 ,, 0 ,,,0.8,0,1,0,
WSPro=,,,, 1 ,,,, 0 ,,,, 0 ,,,,-1 ,-1 ,-1 , 0 , 0 , 0 , 0 , 0
BC Design=,, 0 ,, 0 ,,,,,,

Type RM Length L Ch R = 1 ,11088.01,519.900500,519.900500,519.900500
XS GIS Cut Line= 6
496451.261522353708095.346220255494428.106474996709924.756317839
491209.356474966 712305.83270672490272.605640769712378.227770135
489448.284351617712211.249225572 488700.85937506711812.611760363
#Sta/Elev= 30
1420.204141.44961470.363 153.9911885.342 125.2432259.15986.389662687.63574.06624
2707.83467.519062794.67563.63628 3523.3557.678513626.29249.992254734.765 27.6684
4870.63531.443775192.19325.000775307.01330.808857889.93517.598758110.87822.37539
8357.349 36.6138 8590.6233.060738600.65539.168418630.76240.307729061.68315.32537
9867.89911.479459972.6667.5329139997.0680.15144410067.6317.1009510380.3947.71254
10481.4874.2387310537.2780.6573710602.8980.4686110667.3365.9221610797.4856.57428
#Mann= 3 , 0 , 0
1420.204  0.0551       01420.204  0.0551       010797.48  0.0551       0
#XS Ineff= 2 , 0
       05329.782                       0
Bank Sta=1420.204,10797.48
Exp/Cntr=0.3,0.1

Type RM Length L Ch R = 1 ,10568.11,732.761100,732.761100,732.761100
XS GIS Cut Line= 6
496350.832922578707971.065827981493978.870989144710136.513662741
491098.683523864712284.045742169490411.474808455712276.478789136
489409.315097272711562.899128348488815.545433044711494.894452021
#Sta/Elev= 30
 1621.95165.27421792.334162.09532028.244145.57892072.739126.92292306.873121.5044
2374.575102.44182577.68381.982133155.46358.083293688.00357.004673748.73650.73559
5140.01324.534265485.61330.243465587.10325.95627 8013.7618.418518247.32122.52259
8419.41932.15797 8815.1232.170989027.37416.35896 9184.9411.53262 9903.039.639579
9929.548 15.37359984.5570.219329 10194.925.7511910243.2746.1354310346.3369.23043
10657.65 78.875810777.87111.205210797.87121.090110897.94126.540210967.58122.1004
#Mann= 3 , 0 , 0
 1621.95  0.0569       0 1621.95  0.0569       010967.58  0.0569       0
#XS Ineff= 2 , 0
       05526.485                       0
Bank Sta=1621.95,10967.58
Exp/Cntr=0.3,0.1

Type RM Length L Ch R = 1 ,9835.345,977.014800,977.014800,977.014800
XS GIS Cut Line= 6
496064.297966128707733.053823235493686.179495512709720.469041855
 491924.96234488710880.225082977 491352.62576224711139.377273752
490739.092994983711307.100134351488853.562799781711442.160685203
#Sta/Elev= 30
2985.886256.17313108.597254.90443240.202231.6488 3293.75231.68393348.898 212.881
3400.502172.27273484.826   151.93530.135118.43633575.444112.50373707.278106.4895
3733.76894.496093919.19892.443354051.647  72.6134743.41347.972264785.21739.81969
4837.29352.730164900.221  45.4286559.58720.732956668.81527.288257899.94625.18445
9819.35911.898369939.59719.152169989.6610.21288310360.3634.2613410501.0816.63323
10641.7718.7113110972.4349.4145811112.7476.0627411253.57 122.41211356.12121.6533
#Mann= 3 , 0 , 0
2985.886   0.047       02985.886   0.047       011356.12   0.047       0
#XS Ineff= 2 , 0
       07448.211        10354.45       0
Bank Sta=2985.886,11356.12
Exp/Cntr=0.3,0.1

Type RM Length L Ch R = 1 ,8858.331,5129.327800,5129.327800,5129.327800
XS GIS Cut Line= 6
494918.659234703706948.962260872 493031.48771286708414.835718378
490658.636360139709928.350762486489740.192896068710741.923976347
488661.990686864711352.974093303487986.888387889711612.301673442
#Sta/Elev= 30
3350.101164.96093577.107 110.8313654.829107.94613842.697135.03173937.439131.6637
4255.18573.536334287.30859.89044 4492.3660.317444555.61168.67129 4856.3224.50673
5724.14813.523895821.18623.931116230.89418.145796915.73819.769476987.68826.01082
7069.83920.983449348.4497.4865719881.8938.2187959914.35917.45748 9987.260.129141
10186.5620.4748510509.8770.7063610569.0673.05068 10767.4 110.66710873.47 94.2814
11021.5860.4635711349.7141.24001 11467.269.9122111636.38136.537411760.24147.2714
#Mann= 3 , 0 , 0
3350.101  0.0466       03350.101  0.0466       011760.24  0.0466       0
#XS Ineff= 2 , 0
       07659.648                       0
Bank Sta=3350.101,11760.24
Exp/Cntr=0.3,0.1

Type RM Length L Ch R = 1 ,3729.003,211.467600,211.467600,211.467600
XS GIS Cut Line= 6
494505.417917788706681.570820525491823.256349117709052.992149532
490184.367460281708525.214371756488200.046901196707375.251307741
487919.511090428707361.633064508485886.117732853708515.637438402
#Sta/Elev= 30
3189.217 217.8743296.559173.51963420.851101.80273662.40555.863284257.62149.39881
4591.3235.0589495645.82222.768976742.22525.090767891.881 12.49969703.983 12.8754
 10011.8-0.1650510148.8417.0145510881.687.75062111031.8518.2426711134.5141.28318
11256.0738.2104511276.3371.8644311296.5990.1223111377.63113.136211549.55130.2727
11641.54127.668311756.52155.980911928.99228.919312147.52299.862112388.92413.3844
12451.43433.127112595.89 445.84413021.32529.944913320.27526.773413445.47538.5759
#Mann= 3 , 0 , 0
3189.217  0.0421       03189.217  0.0421       013445.47  0.0421       0
#XS Ineff= 2 , 0
       0 7485.38        10087.87       0
Bank Sta=3189.217,13445.47
Exp/Cntr=0.3,0.1

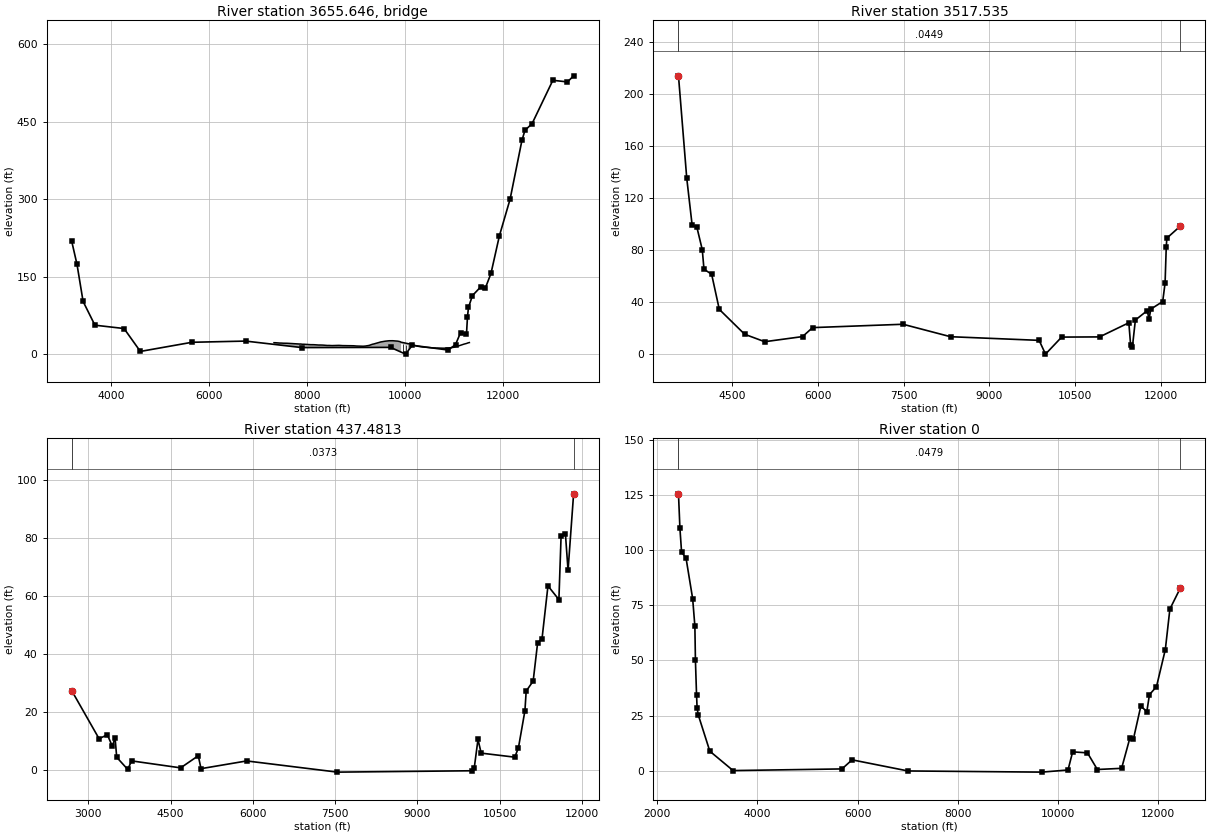
Type RM Length L Ch R = 3 ,3655.646,,,
BEGIN DESCRIPTION:
END DESCRIPTION:
Bridge Culvert--1,0,-1,-1, 0
Deck Dist Width WeirC Skew NumUp NumDn MinLoCord MaxHiCord MaxSubmerge Is_Ogee
86.233800,39.000000,2.6,0, 60, 60, , , 0.95, 0, 0,0,,
 7322.34 7352.81 7449.36 7460.08 7513.72 7599.53 7846.36 7867.90 7900.22 7932.54
 8072.59 8137.22 8244.47 8255.12 8318.97 8414.75 8446.68 8510.53 8648.88 8725.37
 8948.40 9007.91 9143.35 9192.60 9256.41 9278.79 9313.25 9340.60 9353.88 9506.16
 9595.71 9678.13 9750.84 9851.70 9901.18 9908.83 9919.22 9919.2210057.7210057.72
10078.0610079.4310089.3610179.9710256.3210354.4910579.5910611.3410643.0910664.25
10789.8110892.4910994.8411015.1911035.5411106.7511207.5011257.5411287.5611315.19
   21.98   21.92   21.21   21.31   20.98   20.84   19.39   19.44   18.98   18.98
   18.16   18.12   17.40   17.51   17.34   16.60   16.67   16.39   16.81   16.37
   16.05   15.55   15.13   15.52   16.51   17.07   18.33   19.11   19.33   23.45
   24.90   25.75   25.78   24.96   23.95   23.20   22.99   22.99   20.23   20.23
   19.83   20.00   19.98   16.96   15.15   13.68   11.84   11.85   11.55   11.67
   11.31   11.74   13.04   13.54   14.41   16.10   19.26   20.50   21.60   22.21
 -978.02 -978.08 -978.79 -978.69 -979.02 -979.16 -980.61 -980.56 -981.02 -981.02
 -981.84 -981.88 -982.60 -982.49 -982.66 -983.40 -983.33 -983.61 -983.19 -983.63
 -983.95 -984.45 -984.87 -984.48 -983.49 -982.93 -981.67 -980.89 -980.67 -976.55
 -975.10 -974.25 -974.22 -975.04 -976.05 -976.80 -977.01   19.99   17.23 -979.77
 -980.17 -980.00 -980.02 -983.04 -984.85 -986.32 -988.16 -988.15 -988.45 -988.33
 -988.69 -988.26 -986.96 -986.46 -985.59 -983.90 -980.74 -979.50 -978.40 -977.79
 7322.34 7352.81 7449.36 7460.08 7513.72 7599.53 7846.36 7867.90 7900.22 7932.54
 8072.59 8137.22 8244.47 8255.12 8318.97 8414.75 8446.68 8510.53 8648.88 8725.37
 8948.40 9007.91 9143.35 9192.60 9256.41 9278.79 9313.25 9340.60 9353.88 9506.16
 9595.71 9678.13 9750.84 9851.70 9901.18 9908.83 9922.26 9922.2610060.7610060.76
10078.0610079.4310089.3610179.9710256.3210354.4910579.5910611.3410643.0910664.25
10789.8110892.4910994.8411015.1911035.5411106.7511207.5011257.5411287.5611315.19
   21.98   21.92   21.21   21.31   20.98   20.84   19.39   19.44   18.98   18.98
   18.16   18.12   17.40   17.51   17.34   16.60   16.67   16.39   16.81   16.37
   16.05   15.55   15.13   15.52   16.51   17.07   18.33   19.11   19.33   23.45
   24.90   25.75   25.78   24.96   23.95   23.20   22.93   22.93   20.17   20.17
   19.83   20.00   19.98   16.96   15.15   13.68   11.84   11.85   11.55   11.67
   11.31   11.74   13.04   13.54   14.41   16.10   19.26   20.50   21.60   22.21
 -978.02 -978.08 -978.79 -978.69 -979.02 -979.16 -980.61 -980.56 -981.02 -981.02
 -981.84 -981.88 -982.60 -982.49 -982.66 -983.40 -983.33 -983.61 -983.19 -983.63
 -983.95 -984.45 -984.87 -984.48 -983.49 -982.93 -981.67 -980.89 -980.67 -976.55
 -975.10 -974.25 -974.22 -975.04 -976.05 -976.80 -977.07   19.93   17.17 -979.83
 -980.17 -980.00 -980.02 -983.04 -984.85 -986.32 -988.16 -988.15 -988.45 -988.33
 -988.69 -988.26 -986.96 -986.46 -985.59 -983.90 -980.74 -979.50 -978.40 -977.79
Pier Skew, UpSta & Num, DnSta & Num=  ,9964.88, 2 ,9967.93, 2 , 0 , 0 , 0 ,,
    3.00    3.00
 -977.92   22.08
    3.00    3.00
 -977.98   22.02
Pier Skew, UpSta & Num, DnSta & Num=  ,10012.05, 2 ,10015.10, 2 , 0 , 0 , 0 ,,
    3.00    3.00
 -978.86   21.14
    3.00    3.00
 -978.92   21.08
BR Coef=-1 , 0 , 0 ,, 0 ,,,0.8,0,1,0,
WSPro=,,,, 1 ,,,, 0 ,,,, 0 ,,,,-1 ,-1 ,-1 , 0 , 0 , 0 , 0 , 0
BC Design=,, 0 ,, 0 ,,,,,,

Type RM Length L Ch R = 1 ,3517.535,3080.053800,3080.053800,3080.053800
XS GIS Cut Line= 6
494202.282182068706485.424168006491743.513792276708865.087118223
489932.287441462708126.978334606488760.740161628 707365.94539997
487740.986350656 707237.92447941486838.308974564707491.919628486
#Sta/Elev= 30
3562.668214.0797  3707.5135.09623802.00198.932793883.00297.728933978.82980.14753
4008.59965.131544142.56861.222524276.537 34.16444720.00915.001135071.0129.256815
5732.518 13.2069 5908.0220.12165 7489.4422.70229 8320.4713.11188 9870.0310.29836
9981.051-0.3041610263.4612.8205710926.3512.9590111438.5423.8522811469.716.689049
11500.875.19849511552.8225.9591911760.5833.2195411791.7526.6417111822.9134.36978
12030.6840.2016112072.2354.4031912093.0182.47169 12103.489.0447512338.8998.31009
#Mann= 3 , 0 , 0
3562.668  0.0449       03562.668  0.0449       012338.89  0.0449       0
#XS Ineff= 2 , 0
       07649.245        10086.08       0
Bank Sta=3562.668,12338.89
Exp/Cntr=0.3,0.1

Type RM Length L Ch R = 1 ,437.4813,437.481300,437.481300,437.481300
XS GIS Cut Line= 6
493220.960537106704430.924466997489634.482573509704728.035736606
488923.738047391704929.099090427488466.463286549705186.808974639
487288.936007351706376.200036079485057.337216258707729.544273838
#Sta/Elev= 30
2699.22427.323423197.34510.801893347.99912.170763438.3918.2283293488.60811.08359
3518.7394.411043 3719.610.2347663789.9153.1732074683.7920.7745745005.1864.939114
5055.4030.4949135887.0463.1543257540.622-0.696719998.985-0.2255710034.610.603076
10103.9110.5639610161.665.84718610774.284.45152310841.247.69761610959.2620.42315
10982.3827.2088711109.5530.6391811190.4743.78137 11271.4 45.275611379.3263.41488
11578.6158.6849511618.4780.5781211698.1881.1330411745.3968.7569411846.7495.10088
#Mann= 3 , 0 , 0
2699.224  0.0373       02699.224  0.0373       011846.74  0.0373       0
#XS Ineff= 2 , 0
       06373.809        10240.89       0
Bank Sta=2699.224,11846.74
Exp/Cntr=0.3,0.1

Type RM Length L Ch R = 1 ,       0,0.000000,0.000000,0.000000
XS GIS Cut Line= 6
493181.137175525 703656.94759634491881.933292893704270.681945804
490235.617471695704172.931856424 488337.52897948704956.123709992
485950.098755685706762.512824571484323.916692542707695.601808796
#Sta/Elev= 30
2422.225 125.7112451.132110.04492484.31199.183782572.78896.577662705.50478.07666
2749.74265.622432760.80250.041152782.92134.470732793.98128.51043  2816.125.37084
3048.3528.7773973512.857-0.019955686.7490.726231 5888.994.8549717003.655-0.18903
9676.902-0.7261910200.960.24511510293.548.48230910589.118.029377 10786.80.467366
11271.071.00308711437.8214.8742411507.4914.3591111654.79  29.26311775.2126.79055
11827.3634.46793 11967.738.0964212144.3554.9757112235.11 73.337212443.7382.90209
#Mann= 3 , 0 , 0
2422.225  0.0479       02422.225  0.0479       012443.73  0.0479       0
#XS Ineff= 2 , 0
       0                10270.03       0
Bank Sta=2422.225,12443.73
Exp/Cntr=0.3,0.1